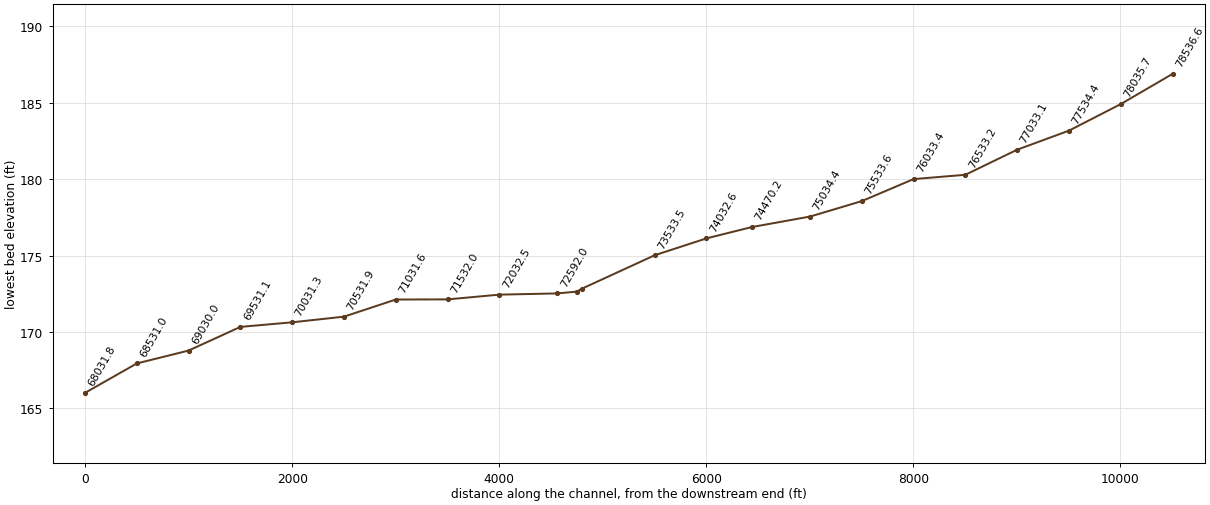
--- 021209_rocky_swamp.prj (project) ---

Proj Title=Rocky Swamp
Current Plan=p01
Default Exp/Contr=.3,.1
English Units
Geom File=g01
Flow File=f01
Plan File=p01
Y Axis Title=Elevation
X Axis Title(PF)=Main Channel Distance
X Axis Title(XS)=Station
BEGIN DESCRIPTION:
NCFPM - Tar-Pamlico River Basin
END DESCRIPTION:
DSS Export Rating Curves= 0
DSS Export Rating Curve Sorted= 0
DSS Export Volume Flow Curves= 0
DXF OffsetX= 0
DXF OffsetY= 0
DXF ScaleX= 1
DXF ScaleY= 10

--- 021209_rocky_swamp.p01 (plan) ---

Plan Title=ROCKY SWAMP
Version=Version 3.0.1  Mar 2001
Short Identifier=Base Plan
Geom File=g01
Flow File=f01
Subcritical Flow
K Sum by GR= 0
Std Step Tol= 0.01
Critical Tol= 0.01
Num of Std Step Trials= 20
Max Error Tol= 0.3
Flow Tol Ratio= 0.001
Split Flow NTrial= 30
Split Flow Tol= 0.02
Split Flow Ratio= 0.02
Log Output Level= 0
Friction Slope Method= 1
Unsteady Friction Slope Method= 2
Parabolic Critical Depth
Global Vel Dist= 0 , 0 , 0
Global Log Level= 0
CheckData=True
Encroach Param= 0 ,0,0, 2
Encroach River=Main Stem
Encroach Reach=Reach - 1
Encroach Node=78536.6
       1  4929.7 5284.73
Encroach Node=78035.7
       1 4860.58 5120.93
Encroach Node=77534.4
       1    4586    5027
Encroach Node=77033.1
       1 4730.51 5053.26
Encroach Node=76533.2
       1 4827.45 5040.32
Encroach Node=76033.4
       1 4718.37 5045.57
Encroach Node=75533.6
       1 4798.86 5183.53
Encroach Node=75034.4
       1 4918.55    5265
Encroach Node=74470.2
       1 4972.85  5344.5
Encroach Node=74032.6
       1 4821.02 5182.46
Encroach Node=73533.5
       1 4957.87 5288.71
Encroach Node=72826.5
       1    4965    5034
Encroach Node=72804.0
       1    4965    5034
Encroach Node=72781.5
       1    4965    5034
Encroach Node=72592.0
       1 4668.05 5080.04
Encroach Node=72032.5
       1  4720.6  5125.6
Encroach Node=71532.0
       1 4968.02 5181.63
Encroach Node=71031.6
       1 4757.58  5074.1
Encroach Node=70531.9
       1 4782.69 5226.49
Encroach Node=70031.3
       1    4845 5269.27
Encroach Node=69531.1
       1 4975.88 5176.94
Encroach Node=69030.0
       1    4969    5426
Encroach Node=68531.0
       1  4952.4 5310.72
Encroach Node=68031.8
       1 4772.69 5261.24
Encroach Node=67531.1
       1 4818.67 5296.94
Encroach Node=67031.5
       1 4883.45 5297.83
Encroach Node=66530.7
       1    4967    5355
Encroach Node=65947.8
       1 4847.74 5125.32
Encroach Node=65570.9
       1 4888.66 5294.51
Encroach Node=65153.8
       1 4886.36 5397.92
Encroach Node=64527.9
       1 4626.41 5211.25
Encroach Node=63766.5
       1    4700    5028
Encroach Node=63731.5
       1    4700    5028
Encroach Node=63696.5
       1    4700    5028
Encroach Node=63524.6
       1 4893.99  5179.2
Encroach Node=63024.1
       1 4923.34 5112.89
Encroach Node=62523.7
       1 4828.26 5082.51
Encroach Node=62022.4
       1 4899.03 5070.99
Encroach Node=61522.7
       1 4721.52 5110.77
Encroach Node=61022.9
       1  4782.5 5344.41
Encroach Node=60521.4
       1 4696.14 5243.71
Encroach Node=60021.5
       1 4505.87 5161.57
Encroach Node=59521.2
       1 4671.04 5126.41
Encroach Node=59021.0
       1    4967    5757
Encroach Node=58521.8
       1    4967    5544
Encroach Node=58020.8
       1 4741.82 5436.87
Encroach Node=57520.2
       1 4852.94 5174.81
Encroach Node=57019.4
       1 4842.83 5090.96
Encroach Node=56563.7
       1    4967    5132
Encroach Node=56017.6
       1 4963.18 5072.19
Encroach Node=55516.1
       1 4918.85 5085.91
Encroach Node=55016.2
       1 4950.83 5145.13
Encroach Node=54451.5
       1 4793.63  5085.2
Encroach Node=54083.4
       1 4827.91 5265.16
Encroach Node=53512.2
       1    4967    5314
Encroach Node=53012.7
       1    4965    5539
Encroach Node=52512.8
       1    4965    5748
Encroach Node=52011.9
       1    4965    5536
Encroach Node=51010.6
       1 4800.37 5548.28
Encroach Node=50510.0
       1 4875.08 5375.08
Encroach Node=50008.6
       1 4593.78 5139.45
Encroach Node=49509.6
       1 4431.63 5254.89
Encroach Node=49011.3
       1 4444.94 5194.72
Encroach Node=48508.9
       1 4577.58 5409.14
Encroach Node=48211.3
       1 4547.75 5358.55
Encroach Node=47393.6
       1    4358    5036
Encroach Node=47006.0
       1 4448.21 5073.82
Encroach Node=46730.5
       1 4668.42 5136.07
Encroach Node=46007.9
       1 4752.53 5414.95
Encroach Node=45653.4
       1    4683    5036
Encroach Node=45003.2
       1 4783.91 5303.84
Encroach Node=44504.9
       1 4552.81 5338.36
Encroach Node=44005.1
       1 4707.77 5571.19
Encroach Node=43504.9
       1  4651.6 5092.48
Encroach Node=43003.1
       1 4565.25 5048.38
Encroach Node=42503.3
       1    4563    5042
Encroach Node=42002.8
       1  4535.4 5136.26
Encroach Node=41502.1
       1 4643.13 5215.19
Encroach Node=41002.2
       1  4594.9 5318.62
Encroach Node=40228.9
       1    4929    5174
Encroach Node=40206.4
       1    4929    5174
Encroach Node=40183.9
       1    4929    5174
Encroach Node=39791.9
       1 4871.39  5059.8
Encroach Node=39502.8
       1 4815.28 5198.23
Encroach Node=39000.0
       1 4802.28 5377.23
Encroach Node=38498.0
       1 4798.18 5748.75
Encroach Node=37997.7
       1 4739.45 5801.25
Encroach Node=37495.9
       1 4834.32 5851.56
Encroach Node=36996.6
       1 4714.31 5572.45
Encroach Node=36412.4
       1 4968.37 5629.52
Encroach Node=35863.9
       1    4962    5800
Encroach Node=35491.9
       1 4851.47 5796.08
Encroach Node=34991.7
       1 4667.68 5849.78
Encroach Node=34490.6
       1  4652.6 6102.18
Encroach Node=33991.7
       1 4954.13 5829.48
Encroach Node=33490.4
       1 4888.63 5951.73
Encroach Node=32990.9
       1 4851.27 5634.09
Encroach Node=32493.5
       1 4788.39  5691.4
Encroach Node=31992.8
       1 4742.87 5507.99
Encroach Node=31490.9
       1 4587.01 5084.06
Encroach Node=30991.5
       1 4666.34 5114.12
Encroach Node=30492.1
       1 4331.42 5224.92
Encroach Node=29991.3
       1 4011.99 5301.31
Encroach Node=29491.0
       1    3959    5040
Encroach Node=28993.5
       1 4342.64 5483.46
Encroach Node=28573.5
       1 4733.89 5448.19
Encroach Node=27993.7
       1    4959    5719
Encroach Node=27629.1
       1  4275.3 5502.96
Encroach Node=26996.9
       1 4123.11 5582.11
Encroach Node=26496.7
       1 4451.58 5083.27
Encroach Node=26129.2
       1  4403.1  5165.6
Encroach Node=25609.7
       1 4626.04 5467.78
Encroach Node=25000.0
       1 4629.12 5787.88
Encroach Node=24500.0
       1 4545.43 5863.65
Encroach Node=24001.6
       1 4292.53 5631.63
Encroach Node=23502.1
       1 4076.28 5339.71
Encroach Node=23001.7
       1  3906.9 5562.14
Encroach Node=22500.0
       1 4361.96 5622.57
Encroach Node=22000.0
       1 4687.16 5846.32
Encroach Node=21697.7
       1 4899.41 5528.66
Encroach Node=20998.0
       1 4234.11  5068.2
Encroach Node=20498.8
       1    4920    5265
Encroach Node=20001.1
       1 4966.06 5533.42
Encroach Node=19503.0
       1    4969    5523
Encroach Node=19005.4
       1    4949    5829
Encroach Node=18605.2
       1    4949    5934
Encroach Node=18006.4
       1 4381.56 6126.01
Encroach Node=17579.6
       1 4206.88 6097.06
Encroach Node=17007.4
       1  4344.5 5140.69
Encroach Node=16709.2
       4      .7
Encroach Node=16435.6
       4      .7
Encroach Node=16126.2
       4      .7
Encroach Node=15478.8
       1    4926    5074
Encroach Node=15453.8
       1    4926    5074
Encroach Node=15428.8
       1    4926    5074
Encroach Node=15097.9
       4      .7
Encroach Node=14569.2
       4      .7
Encroach Node=14000.8
       4      .7
Encroach Node=13285.7
       4      .7
Computation Interval=1HOUR
Output Interval=1HOUR
Run HTab= 0
Run UNet= 0
Run PostProcess= 0
UNET Theta= 1
UNET ZTol= 0.02
UNET ZSATol= 0.1
UNET MxIter= 20
UNET MaxInSteps= 20
UNET DtIC= 0
UNET DtMin= 0
UNET MaxCRTS= 20
UNET WFStab= 2
UNET SFStab= 1
UNET WFX= 1
UNET SFX= 1
UNET Convert EG Bridges=-1
UNET Use Existing IB Tables=-1
Instantaneous Interval=1HOUR
Write IC File= 0
Write Velocity= 0
Write Detailed= 0

--- 021209_rocky_swamp.f01 (steady flow) ---

Flow Title=Rocky Swamp
Version=Version 3.0.1  Mar 2001
Number of Profiles= 2
Profile Names=100-YEAR,AFW
River Rch & RM=Main Stem,Reach - 1       ,78536.6
    2290    2290
River Rch & RM=Main Stem,Reach - 1       ,74032.6
    2840    2840
River Rch & RM=Main Stem,Reach - 1       ,70531.9
    3210    3210
River Rch & RM=Main Stem,Reach - 1       ,65570.9
    3450    3450
River Rch & RM=Main Stem,Reach - 1       ,60021.5
    3750    3750
River Rch & RM=Main Stem,Reach - 1       ,53012.7
    4560    4560
River Rch & RM=Main Stem,Reach - 1       ,47393.6
    4850    4850
River Rch & RM=Main Stem,Reach - 1       ,35863.9
    5110    5110
River Rch & RM=Main Stem,Reach - 1       ,32493.5
    5410    5410
River Rch & RM=Main Stem,Reach - 1       ,29491
    5820    5820
River Rch & RM=Main Stem,Reach - 1       ,25000
    6080    6080
River Rch & RM=Main Stem,Reach - 1       ,17579.6
    6720    6720
Boundary for River Rch & Prof#=Main Stem,Reach - 1       , 1
Up Type= 0
Dn Type= 3
Dn Slope=.0006
DSS Import GetInterval= 0
DSS Import GetPeak= 0
DSS Import FillOption= 0

--- 021209_rocky_swamp.g01 (geometry) ---

Geom Title=Geom 01 by CodeH2 for Windows

River Reach=Main Stem,Reach - 1
Reach XY= 2
              .5             .95              .5             .05

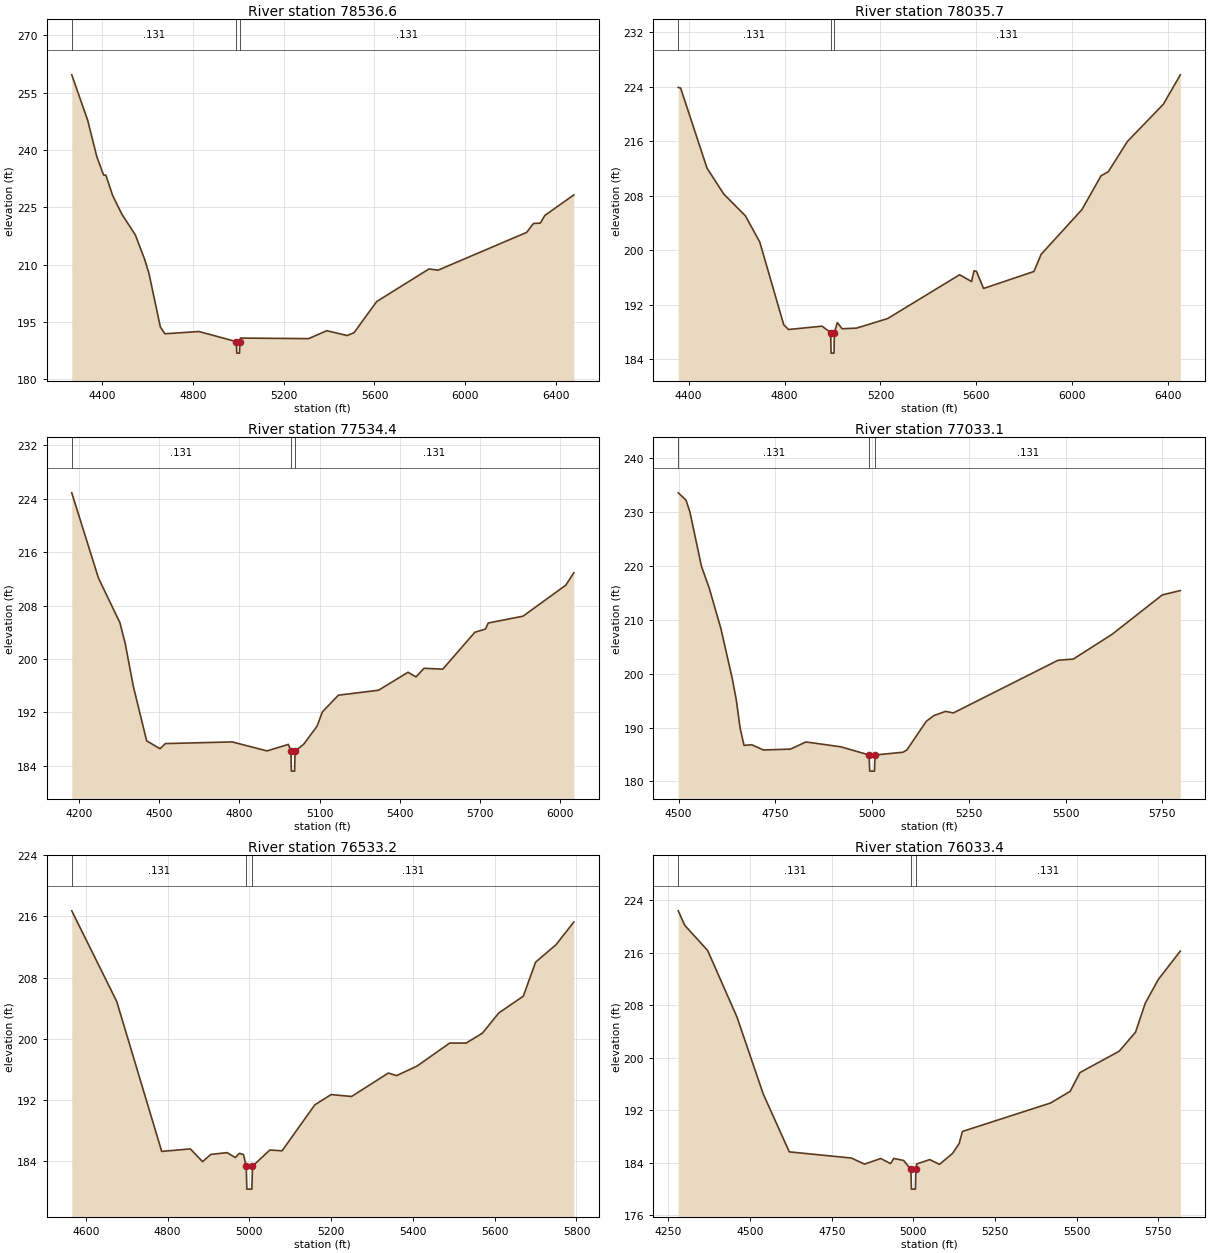
Type RM Length L Ch R = 1 ,78536.6,500.9,500.9,500.9
BEGIN DESCRIPTION:
Rocky Swamp 156.0
END DESCRIPTION:
#Sta/Elev= 30
  4267.6  259.65  4337.6  247.79  4377.6  238.31  4407.6  233.46  4417.6  233.42
  4447.6   228.1  4487.6  223.27  4547.6  217.78  4587.6  211.54  4607.6  207.68
  4657.6  193.72  4677.6  191.95  4827.6  192.54  4992.3  189.89  4993.8  186.89
  5006.1  186.89  5007.6  189.89    5010  190.83    5310  190.68    5390  192.75
    5480  191.49    5510  192.23    5610  200.38    5840  208.89    5880  208.58
    6270  218.46    6300  220.79    6330  220.88    6350  222.88  6477.7  228.26
#Mann= 3 , 1 , 0
 4267.60   0.131       0  4992.3    0.05       0  5007.6   0.131       0
Bank Sta=4992.30,5007.60
Exp/Cntr=0.3,0.1

Type RM Length L Ch R = 1 ,78035.7,501.3,501.3,501.3
BEGIN DESCRIPTION:
Rocky Swamp 155.0
END DESCRIPTION:
#Sta/Elev= 30
  4356.5  223.93  4366.5  223.84  4476.5  212.08  4546.5  208.27  4636.5  205.08
  4696.5  201.23  4796.5  189.08  4816.5  188.38  4956.5  188.87  4992.4  187.91
  4993.9  184.91  5006.2  184.91  5007.7  187.91    5020  189.39    5040  188.49
    5100  188.58    5230  189.99    5530  196.42    5580  195.42    5590     197
    5600  196.93    5630  194.41    5840   196.9    5870  199.42    6040  205.98
    6120  210.96    6150  211.54    6230     216    6380  221.47  6450.5  225.78
#Mann= 3 , 1 , 0
 4356.50   0.131       0  4992.4    0.05       0  5007.7   0.131       0
Bank Sta=4992.40,5007.70
Exp/Cntr=0.3,0.1

Type RM Length L Ch R = 1 ,77534.4,501.3,501.3,501.3
BEGIN DESCRIPTION:
Rocky Swamp 154.0
END DESCRIPTION:
#Sta/Elev= 30
  4172.9   224.9  4272.9   212.1  4352.9  205.43  4372.9  202.28  4402.9  195.92
  4452.9  187.71  4502.9  186.53  4522.9   187.3  4772.9  187.55  4902.9   186.2
  4982.9  187.18  4992.4  186.17  4993.9  183.17  5006.2  183.17  5007.7  186.17
    5040   187.2    5090   189.9    5110  192.06    5170  194.56    5320   195.3
    5430  197.99    5460   197.3    5490  198.59    5560  198.46    5680  203.99
    5720  204.48    5730  205.38    5860   206.4    6020  211.05  6050.2  212.92
#Mann= 3 , 1 , 0
 4172.90   0.131       0  4992.4    0.05       0  5007.7   0.131       0
Bank Sta=4992.40,5007.70
Exp/Cntr=0.3,0.1

Type RM Length L Ch R = 1 ,77033.1,499.9,499.9,499.9
BEGIN DESCRIPTION:
Rocky Swamp 153.0
END DESCRIPTION:
#Sta/Elev= 30
  4499.2  233.62  4519.2  232.28  4529.2  230.12  4559.2  219.97  4579.2  215.93
  4609.2  208.46  4639.2  198.99  4649.2  195.13  4659.2  189.87  4669.2   186.7
  4689.2  186.82  4719.2  185.85  4789.2  186.01  4829.2  187.34  4919.2  186.44
  4992.4  184.92  4993.9  181.92  5006.2  181.92  5007.7  184.92    5080  185.43
    5090  185.86    5140  191.17    5160  192.25    5190  193.02    5210  192.73
    5480   202.5    5520  202.74    5620  207.33    5750  214.66  5796.4  215.46
#Mann= 3 , 1 , 0
 4499.20   0.131       0  4992.4    0.05       0  5007.7   0.131       0
Bank Sta=4992.40,5007.70
Exp/Cntr=0.3,0.1

Type RM Length L Ch R = 1 ,76533.2,499.8,499.8,499.8
BEGIN DESCRIPTION:
Rocky Swamp 152.0
END DESCRIPTION:
#Sta/Elev= 30
  4565.6  216.74  4675.6  204.86  4785.6  185.22  4855.6  185.55  4885.6  183.88
  4905.6  184.83  4945.6  185.06  4965.6  184.42  4975.6  184.97  4985.6  184.81
  4992.3  183.28  4993.8  180.28  5006.1  180.28  5007.6  183.28    5050   185.4
    5080   185.3    5160  191.32    5200  192.67    5250  192.42    5340  195.49
    5360  195.15    5410   196.4    5490  199.42    5530  199.41    5570  200.71
    5610  203.36    5670  205.56    5700  210.01    5750   212.3  5793.6  215.28
#Mann= 3 , 1 , 0
 4565.60   0.131       0  4992.3    0.05       0  5007.6   0.131       0
Bank Sta=4992.30,5007.60
Exp/Cntr=0.3,0.1

Type RM Length L Ch R = 1 ,76033.4,499.8,499.8,499.8
BEGIN DESCRIPTION:
Rocky Swamp 151.0
END DESCRIPTION:
#Sta/Elev= 30
  4280.1  222.42  4300.1  220.21  4370.1  216.38  4460.1  206.21  4540.1  194.53
  4620.1  185.68  4810.1  184.74  4850.1  183.81  4900.1  184.67  4930.1  183.89
  4940.1  184.68  4970.1  184.37  4992.4     183  4993.9     180  5006.2     180
  5007.7     183    5010  183.84    5050   184.5    5080  183.78    5120  185.45
    5140  186.94    5150  188.79    5420  193.13    5480  194.91    5510  197.77
    5630  201.02    5680  203.92    5710  208.36    5750  211.97  5817.1  216.29
#Mann= 3 , 1 , 0
 4280.10   0.131       0  4992.4    0.05       0  5007.7   0.131       0
Bank Sta=4992.40,5007.70
Exp/Cntr=0.3,0.1

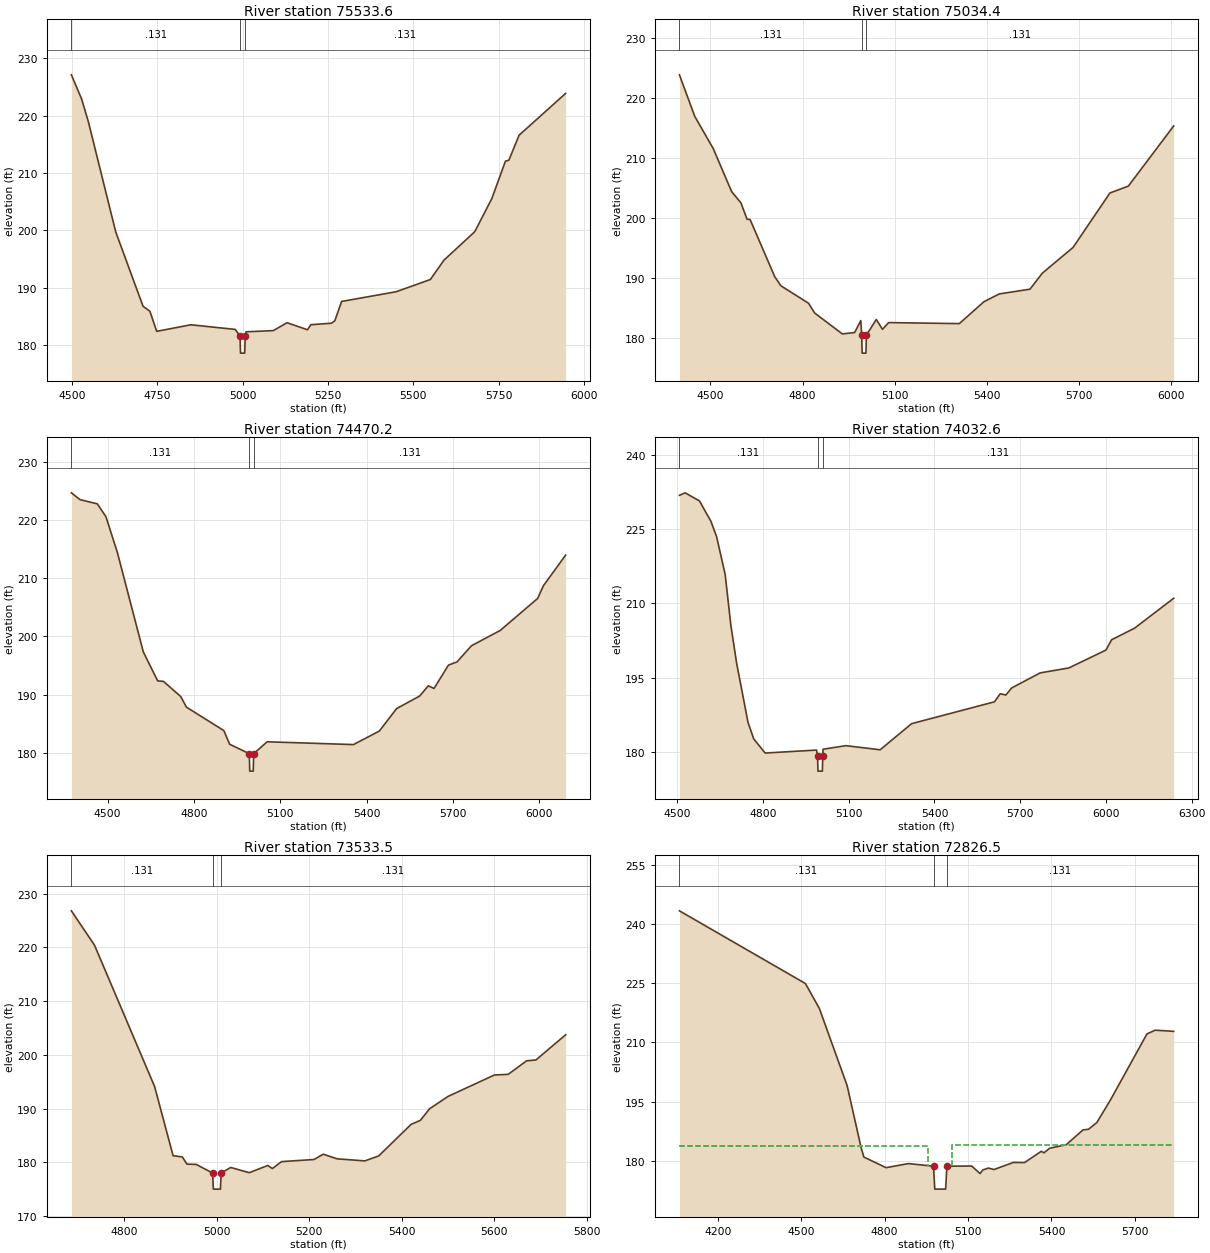
Type RM Length L Ch R = 1 ,75533.6,499.2,499.2,499.2
BEGIN DESCRIPTION:
Rocky Swamp 150.0
END DESCRIPTION:
#Sta/Elev= 30
  4498.2  227.14  4528.2  222.93  4548.2   218.9  4628.2  199.71  4708.2  186.74
  4728.2  185.88  4748.2  182.36  4848.2  183.51  4978.2   182.7  4992.3  181.56
  4993.8  178.56  5006.1  178.56  5007.6  181.56    5010  182.28    5090  182.49
    5130  183.87    5190  182.64    5200  183.52    5260  183.78    5270  184.19
    5290  187.58    5450  189.28    5550  191.41    5590   194.8    5680  199.75
    5730  205.52    5770  212.07    5780  212.23    5810   216.6  5946.4   223.9
#Mann= 3 , 1 , 0
 4498.20   0.131       0  4992.3    0.05       0  5007.6   0.131       0
Bank Sta=4992.30,5007.60
Exp/Cntr=0.3,0.1

Type RM Length L Ch R = 1 ,75034.4,564.2,564.2,564.2
BEGIN DESCRIPTION:
Rocky Swamp 149.0
END DESCRIPTION:
#Sta/Elev= 30
  4399.4  223.85  4449.4  216.93  4509.4  211.58  4569.4  204.41  4599.4  202.56
  4619.4  199.83  4629.4  199.77  4709.4  190.27  4729.4  188.76  4819.4  185.85
  4839.4  184.22  4929.4  180.75  4969.4  180.97  4989.4  182.96  4992.4  180.55
  4993.9  177.55  5006.2  177.55  5007.7  180.55    5040  183.15    5060  181.51
    5080  182.63    5310  182.46    5390   186.1    5440   187.4    5540  188.19
    5580  190.85    5680  195.13    5800  204.19    5860  205.34  6007.5  215.35
#Mann= 3 , 1 , 0
 4399.40   0.131       0  4992.4    0.05       0  5007.7   0.131       0
Bank Sta=4992.40,5007.70
Exp/Cntr=0.3,0.1

Type RM Length L Ch R = 1 ,74470.2,437.6,437.6,437.6
BEGIN DESCRIPTION:
Rocky Swamp 148.0
END DESCRIPTION:
#Sta/Elev= 30
    4374  224.67    4404   223.5    4464  222.78    4494  220.59    4534   214.4
    4624  197.34    4674  192.36    4694  192.28    4754  189.68    4774  187.85
    4904  183.82    4924  181.48  4992.4  179.86  4993.9  176.86  5006.1  176.86
  5007.6  179.86  5054.5   181.9  5354.5  181.42  5444.5  183.75  5504.5  187.61
  5584.5  189.76  5614.5  191.52  5634.5  191.06  5684.5  195.07  5714.5  195.63
  5764.5   198.4  5864.5  201.03  5994.5  206.52  6014.5   208.7  6091.9  213.98
#Mann= 3 , 1 , 0
 4374.00   0.131       0  4992.4    0.05       0  5007.6   0.131       0
Bank Sta=4992.40,5007.60
Exp/Cntr=0.3,0.1

Type RM Length L Ch R = 1 ,74032.6,499.1,499.1,499.1
BEGIN DESCRIPTION:
Rocky Swamp 147.0
END DESCRIPTION:
#Sta/Elev= 30
  4507.5  231.79  4527.5  232.29  4577.5  230.66  4617.5  226.57  4637.5  223.46
  4667.5  215.84  4687.5  205.55  4707.5  197.95  4747.5  185.97  4767.5  182.63
  4807.5  179.77  4987.5  180.37  4990.8  179.12  4992.3  176.12  5007.6  176.12
  5009.1  179.12    5010  180.54    5090  181.26    5210  180.43    5320   185.7
    5610  190.11    5630  191.73    5650  191.49    5670   192.9    5770  195.95
    5870  196.94    6000  200.55    6020  202.64    6100  204.96  6237.2  211.01
#Mann= 3 , 1 , 0
 4507.50   0.131       0  4990.8    0.05       0  5009.1   0.131       0
Bank Sta=4990.80,5009.10
Exp/Cntr=0.3,0.1

Type RM Length L Ch R = 1 ,73533.5,707,707,707
BEGIN DESCRIPTION:
Rocky Swamp 146.0
END DESCRIPTION:
#Sta/Elev= 30
  4685.3   226.8  4735.3  220.41  4865.3  194.11  4905.3  181.24  4925.3  181.01
  4935.3  179.67  4955.3  179.62  4990.8  178.02  4992.3  175.02  5007.7  175.02
  5009.2  178.02    5030  179.05    5070  178.08    5110  179.42    5120  178.85
    5140  180.14    5210  180.53    5230  181.52    5260  180.66    5320  180.27
    5350   181.2    5420  187.07    5440  187.81    5460  189.97    5500  192.27
    5600  196.25    5630  196.38    5670   198.9    5690  199.05  5754.3  203.74
#Mann= 3 , 1 , 0
 4685.30   0.131       0  4990.8    0.05       0  5009.2   0.131       0
Bank Sta=4990.80,5009.20
Exp/Cntr=0.5,0.3

Type RM Length L Ch R = 1 ,72826.5,45,45,45
BEGIN DESCRIPTION:
Upstream Section of Bridge/Culvert/Weir
END DESCRIPTION:
#Sta/Elev= 30
  4062.5  243.28  4515.5  224.87  4565.5  218.57  4665.5     199  4715.5  183.36
  4725.5  180.94  4805.5  178.25  4885.5  179.29    4976  178.62  4980.5  172.82
  5019.5  172.82    5024  178.62  5113.2  178.67  5143.2  176.76  5153.2  177.68
  5173.2  178.15  5193.2  177.78  5263.2  179.58  5303.2  179.54  5363.2  182.39
  5373.2  182.02  5393.2  183.16  5453.2  184.07  5513.2  187.81  5533.2  187.98
  5563.2  189.69  5613.2  195.54  5743.2  212.11  5772.7  213.06  5839.4  212.77
#Mann= 3 , 1 , 0
 4062.50   0.131       0    4976    0.05       0    5024   0.131       0
#XS Ineff= 2 , 0
       0    4955  183.67    5044       0   184.1
Bank Sta=4976.00,5024.00
Exp/Cntr=0.5,0.3

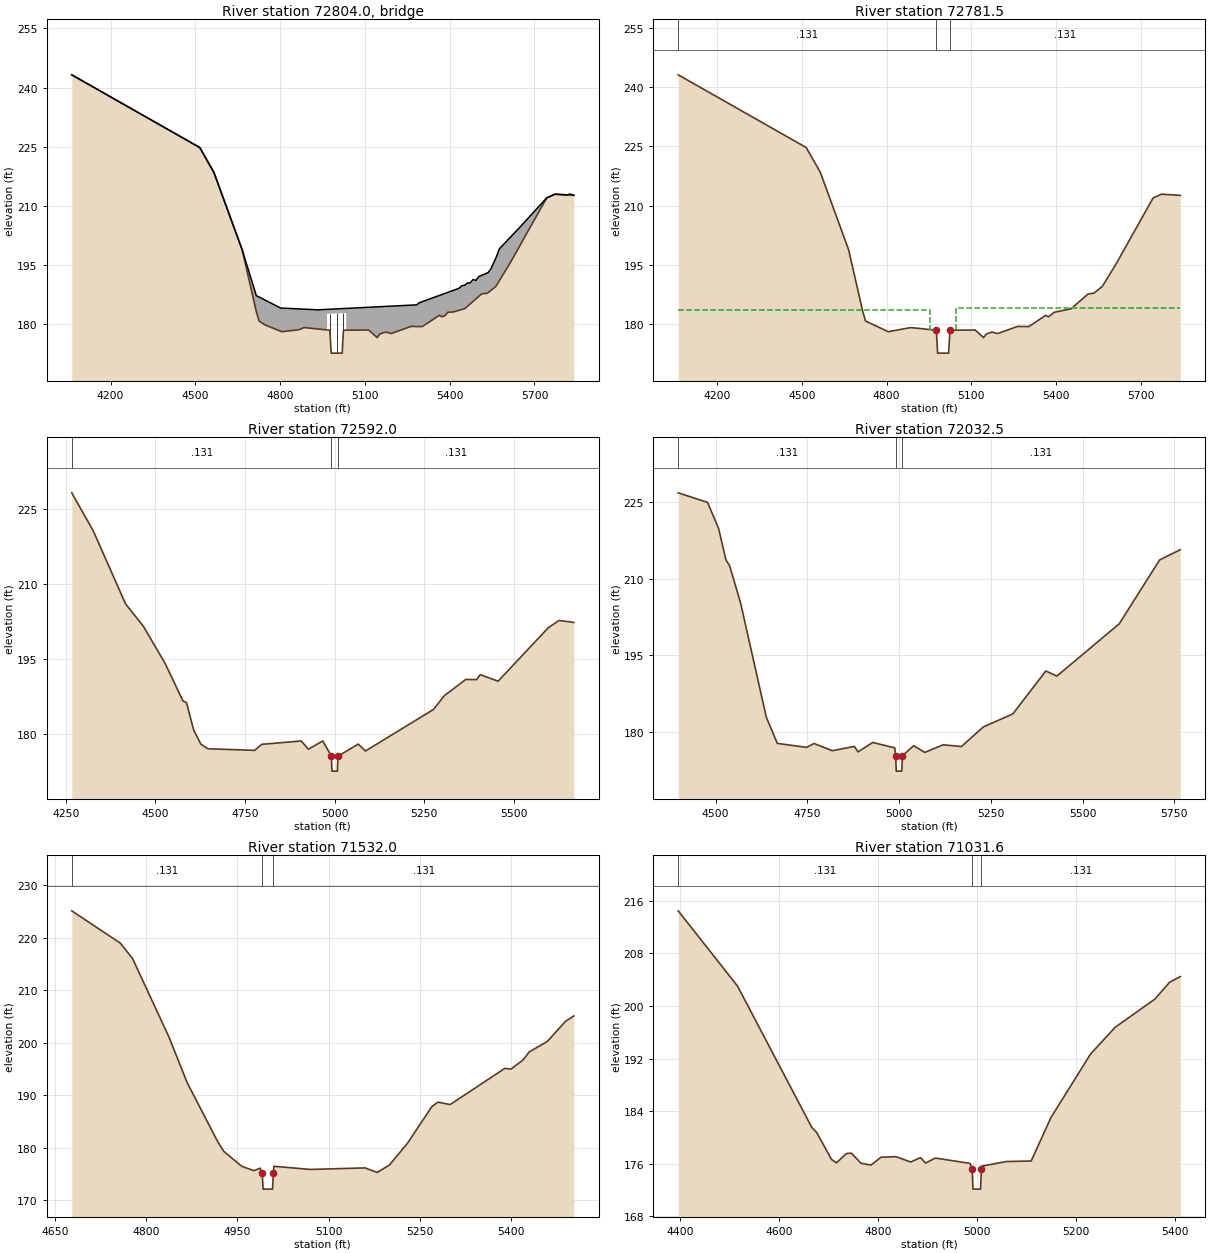
Type RM Length L Ch R = 3 ,72804.0,,,
BEGIN DESCRIPTION:
Sledge Road
Structure ID: Sledge Road
Approximate Survey Structure
END DESCRIPTION:
Bridge Culvert--1,0,-1,-1, 0
Deck Dist Width WeirC Skew NumUp NumDn MinLoCord MaxHiCord MaxSubmerge Is_Ogee
10,25,2.6,, 52, 52,,,0.95,0,1,1,,
  4062.5  4515.5  4565.5  4665.5  4715.5  4725.5  4745.5  4801.9  4805.5  4865.5
  4885.5  4932.9 4965.91    4966 5033.89    5034  5113.2  5143.2  5153.2  5173.2
  5193.2  5263.2  5282.9  5292.9  5303.2  5363.2  5373.2  5383.2  5393.2  5413.2
  5432.9  5442.9  5453.2  5462.9  5472.9  5482.9  5492.9  5502.9  5513.2  5533.2
  5535.5  5545.5  5563.2  5565.5  5575.5  5613.2  5645.5  5743.2  5772.7  5815.5
  5825.5  5839.4
  243.21   224.8   218.5  198.93  187.32  186.95  186.22  184.17  184.16  183.95
  183.88  183.71  183.83  183.83  184.07  184.07  184.36  184.47   184.5  184.58
  184.65   184.9  184.97  185.52  185.79  187.35  187.61  187.87  188.13  188.65
  189.16  189.82  189.93  190.51  190.56  191.41  191.15  192.13  192.45  193.05
  193.12  194.04   196.8  197.16  199.14  201.98  204.41  212.04  212.99   212.8
  213.03   212.7
  243.21   224.8   218.5  198.93  183.29  180.87  179.92  178.28  178.18  178.66
  179.22  178.87  178.62  182.68  182.92  178.56   178.6  176.69  177.61  178.08
  177.71  179.51  179.49  179.48  179.47  182.32  181.95   182.2  183.09  183.18
  183.58  183.79     184   184.6  185.23  185.85  186.47   187.1  187.74  187.91
  188.04  188.61  189.62  189.89  191.06  195.47  199.59  212.04  212.99   212.8
  212.76   212.7
  4062.5  4515.5  4565.5  4665.5  4715.5  4725.5  4745.5  4801.9  4805.5  4865.5
  4885.5  4932.9 4965.91    4966 5033.89    5034  5113.2  5143.2  5153.2  5173.2
  5193.2  5263.2  5282.9  5292.9  5303.2  5363.2  5373.2  5383.2  5393.2  5413.2
  5432.9  5442.9  5453.2  5462.9  5472.9  5482.9  5492.9  5502.9  5513.2  5533.2
  5535.5  5545.5  5563.2  5565.5  5575.5  5613.2  5645.5  5743.2  5772.7  5815.5
  5825.5  5839.4
  243.16  224.76  218.46  198.89  187.32  186.95  186.22  184.17  184.16  183.95
  183.88  183.71  183.83  183.83  184.07  184.07  184.36  184.47   184.5  184.58
  184.65   184.9  184.97  185.52  185.79  187.35  187.61  187.87  188.13  188.65
  189.16  189.82  189.93  190.51  190.56  191.41  191.15  192.13  192.45  193.05
  193.12  194.04   196.8  197.16  199.14  201.98  204.41     212  212.95  212.76
  213.03  212.65
  243.11   224.7   218.4  198.83  183.19  180.77  179.82  178.18  178.08  178.56
  179.12  178.77  178.52  182.58  182.82  178.46   178.5  176.59  177.51  177.98
  177.61  179.41  179.39  179.38  179.37  182.22  181.85   182.1  182.99  183.08
  183.48  183.69   183.9   184.5  185.13  185.75  186.37     187  187.64  187.81
  187.94  188.51  189.52  189.79  190.96  195.37  199.49  211.94  212.89   212.7
  212.66   212.6
Pier Skew, UpSta & Num, DnSta & Num=,4977.4, 2 ,4977.4, 2 , 0 , 0 , 0 ,,
       1       1
   175.1  183.72
       1       1
     175  183.62
Pier Skew, UpSta & Num, DnSta & Num=,5000.0, 2 ,5000.0, 2 , 0 , 0 , 0 ,,
       1       1
  171.75   183.8
       1       1
  171.65   183.7
Pier Skew, UpSta & Num, DnSta & Num=,5022.7, 2 ,5022.7, 2 , 0 , 0 , 0 ,,
       1       1
  175.23  183.89
       1       1
  175.13  183.79
BR Coef= 1 , 1 , 0 ,1.25, 0 ,,,0.8,0,2,0,
Wspro=,,,, 1 ,,,, 0 ,,,, 0 ,,,,-1 ,-1 ,-1 , 0 , 0 , 0 , 0 , 0
BC Design=,, 0 ,, 0 ,,,,,,
BR U #Sta/Elev= 70
  4062.5  243.21  4102.5  241.58  4162.5  239.15  4172.5  238.74  4232.5   236.3
  4392.5   229.8  4412.5  228.99  4462.5  226.95  4481.9  226.17  4515.5   224.8
  4565.5   218.5  4665.5  198.93  4715.5  183.29  4725.5  180.87  4745.5  179.92
  4801.9  178.28  4805.5  178.18  4865.5  178.66  4885.5  179.22  4932.9  178.87
 4965.91  178.62    4966  178.62  4966.1  178.62    4976  178.55  4980.5  172.75
  5019.5  172.75    5024  178.55  5033.8  178.56 5033.89  178.56    5034  178.56
  5113.2   178.6  5143.2  176.69  5153.2  177.61  5173.2  178.08  5193.2  177.71
  5263.2  179.51  5282.9  179.49  5292.9  179.48  5303.2  179.47  5363.2  182.32
  5373.2  181.95  5383.2   182.2  5393.2  183.09  5413.2  183.18  5432.9  183.58
  5442.9  183.79  5452.9  183.99  5453.2     184  5462.9   184.6  5472.9  185.23
  5482.9  185.85  5492.9  186.47  5502.9   187.1  5513.2  187.74  5525.5  187.84
  5533.2  187.91  5535.5  188.04  5545.5  188.61  5563.2  189.62  5565.5  189.89
  5575.5  191.06  5613.2  195.47  5645.5  199.59  5743.2  212.04  5745.5  212.11
  5755.5  212.44  5772.7  212.99  5815.5   212.8  5825.5  212.76  5839.4   212.7
BR U #Mann= 3
 4062.50   0.131    4976    0.05    5024   0.131
BR U Banks=4976.00,5024.00
BR D #Sta/Elev= 70
  4062.5  243.11  4102.5  241.48  4162.5  239.05  4172.5  238.64  4232.5   236.2
  4392.5   229.7  4412.5  228.89  4462.5  226.85  4481.9  226.07  4515.5   224.7
  4565.5   218.4  4665.5  198.83  4715.5  183.19  4725.5  180.77  4745.5  179.82
  4801.9  178.18  4805.5  178.08  4865.5  178.56  4885.5  179.12  4932.9  178.77
 4965.91  178.52    4966  178.52  4966.1  178.52    4976  178.45  4980.5  172.65
  5019.5  172.65    5024  178.45  5033.8  178.46 5033.89  178.46    5034  178.46
  5113.2   178.5  5143.2  176.59  5153.2  177.51  5173.2  177.98  5193.2  177.61
  5263.2  179.41  5282.9  179.39  5292.9  179.38  5303.2  179.37  5363.2  182.22
  5373.2  181.85  5383.2   182.1  5393.2  182.99  5413.2  183.08  5432.9  183.48
  5442.9  183.69  5452.9  183.89  5453.2   183.9  5462.9   184.5  5472.9  185.13
  5482.9  185.75  5492.9  186.37  5502.9     187  5513.2  187.64  5525.5  187.74
  5533.2  187.81  5535.5  187.94  5545.5  188.51  5563.2  189.52  5565.5  189.79
  5575.5  190.96  5613.2  195.37  5645.5  199.49  5743.2  211.94  5745.5  212.01
  5755.5  212.34  5772.7  212.89  5815.5   212.7  5825.5  212.66  5839.4   212.6
BR D #Mann= 3
 4062.50   0.131    4976    0.05    5024   0.131
BR D Banks=4976.00,5024.00

Type RM Length L Ch R = 1 ,72781.5,189.5,189.5,189.5
BEGIN DESCRIPTION:
Downstream Section of Bridge/Culvert/Weir
END DESCRIPTION:
#Sta/Elev= 30
  4062.5   243.1  4515.5  224.69  4565.5  218.39  4665.5  198.82  4715.5  183.18
  4725.5  180.76  4805.5  178.07  4885.5  179.11    4976  178.44  4980.5  172.64
  5019.5  172.64    5024  178.44  5113.2  178.49  5143.2  176.58  5153.2   177.5
  5173.2  177.97  5193.2   177.6  5263.2   179.4  5303.2  179.36  5363.2  182.21
  5373.2  181.84  5393.2  182.98  5453.2  183.89  5513.2  187.63  5533.2   187.8
  5563.2  189.51  5613.2  195.36  5743.2  211.93  5772.7  212.88  5839.4  212.59
#Mann= 3 , 1 , 0
 4062.50   0.131       0    4976    0.05       0    5024   0.131       0
#XS Ineff= 2 , 0
       0    4955  183.67    5044       0   184.1
Bank Sta=4976.00,5024.00
Exp/Cntr=0.5,0.3

Type RM Length L Ch R = 1 ,72592.0,559.5,559.5,559.5
BEGIN DESCRIPTION:
Rocky Swamp 144.0
END DESCRIPTION:
#Sta/Elev= 30
  4266.8  228.29  4326.8  220.66  4416.8  206.04  4466.8  201.52  4526.8  194.15
  4576.8   186.6  4586.8  186.23  4606.8  180.74  4626.8  177.93  4646.8     177
  4776.8  176.68  4796.8  177.89  4906.8  178.56  4926.8  176.91  4966.8  178.57
  4990.8  175.52  4992.3  172.52  5007.6  172.52  5009.1  175.52  5065.8  177.93
  5085.8  176.55  5275.8  184.89  5305.8  187.64  5365.8   190.9  5395.8  190.86
  5405.8  191.85  5455.8  190.54  5595.8  201.27  5625.8  202.71    5667  202.32
#Mann= 3 , 1 , 0
 4266.80   0.131       0  4990.8    0.05       0  5009.1   0.131       0
Bank Sta=4990.80,5009.10
Exp/Cntr=0.3,0.1

Type RM Length L Ch R = 1 ,72032.5,500.5,500.5,500.5
BEGIN DESCRIPTION:
Rocky Swamp 143.0
END DESCRIPTION:
#Sta/Elev= 30
  4398.3  226.71  4478.3  224.84  4508.3  219.76  4528.3  213.64  4538.3   212.5
  4568.3   205.2  4638.3  182.97  4668.3  177.85  4748.3  177.07  4768.3  177.83
  4818.3  176.42  4878.3  177.26  4888.3   176.2  4928.3  178.03  4988.3  176.98
  4990.8  175.44  4992.3  172.44  5007.6  172.44  5009.1  175.44    5040   177.4
    5070  176.09    5120  177.57    5170  177.24    5230  181.08    5310  183.59
    5400  191.97    5430  190.97    5600  201.17    5710  213.62  5766.4  215.62
#Mann= 3 , 1 , 0
 4398.30   0.131       0  4990.8    0.05       0  5009.1   0.131       0
Bank Sta=4990.80,5009.10
Exp/Cntr=0.3,0.1

Type RM Length L Ch R = 1 ,71532.0,500.4,500.4,500.4
BEGIN DESCRIPTION:
Rocky Swamp 142.0
END DESCRIPTION:
#Sta/Elev= 30
  4677.4  225.12  4757.4  218.96  4777.4  216.04  4837.4  201.08  4867.4  192.38
  4917.4   181.2  4927.4  179.34  4957.4  176.45  4977.4  175.65  4987.4  176.12
  4990.8  175.13  4992.3  172.13  5007.7  172.13  5009.2  175.13    5010  176.48
    5070  175.88    5160  176.17    5180  175.31    5200  176.71    5230  180.89
    5270  187.85    5280  188.69    5300  188.23    5390  195.12    5400  194.98
    5420  196.72    5430  198.24    5460  200.25    5490   204.1  5503.6   205.1
#Mann= 3 , 1 , 0
 4677.40   0.131       0  4990.8    0.05       0  5009.2   0.131       0
Bank Sta=4990.80,5009.20
Exp/Cntr=0.3,0.1

Type RM Length L Ch R = 1 ,71031.6,499.7,499.7,499.7
BEGIN DESCRIPTION:
Rocky Swamp 141.0
END DESCRIPTION:
#Sta/Elev= 30
  4396.3  214.49  4516.3  203.02  4666.3  181.53  4676.3  180.74  4706.3  176.64
  4716.3  176.12  4736.3  177.54  4746.3   177.6  4766.3  176.04  4786.3  175.79
  4806.3  176.97  4836.3  177.07  4866.3  176.25  4886.3  176.92  4896.3  176.09
  4916.3  176.85  4986.3  176.04  4990.8  175.12  4992.3  172.12  5007.7  172.12
  5009.2  175.12    5010  175.62    5060  176.32    5110   176.4    5150  183.02
    5230  192.68    5280  196.77    5360  201.04    5390  203.62  5411.6  204.47
#Mann= 3 , 1 , 0
 4396.30   0.131       0  4990.8    0.05       0  5009.2   0.131       0
Bank Sta=4990.80,5009.20
Exp/Cntr=0.3,0.1

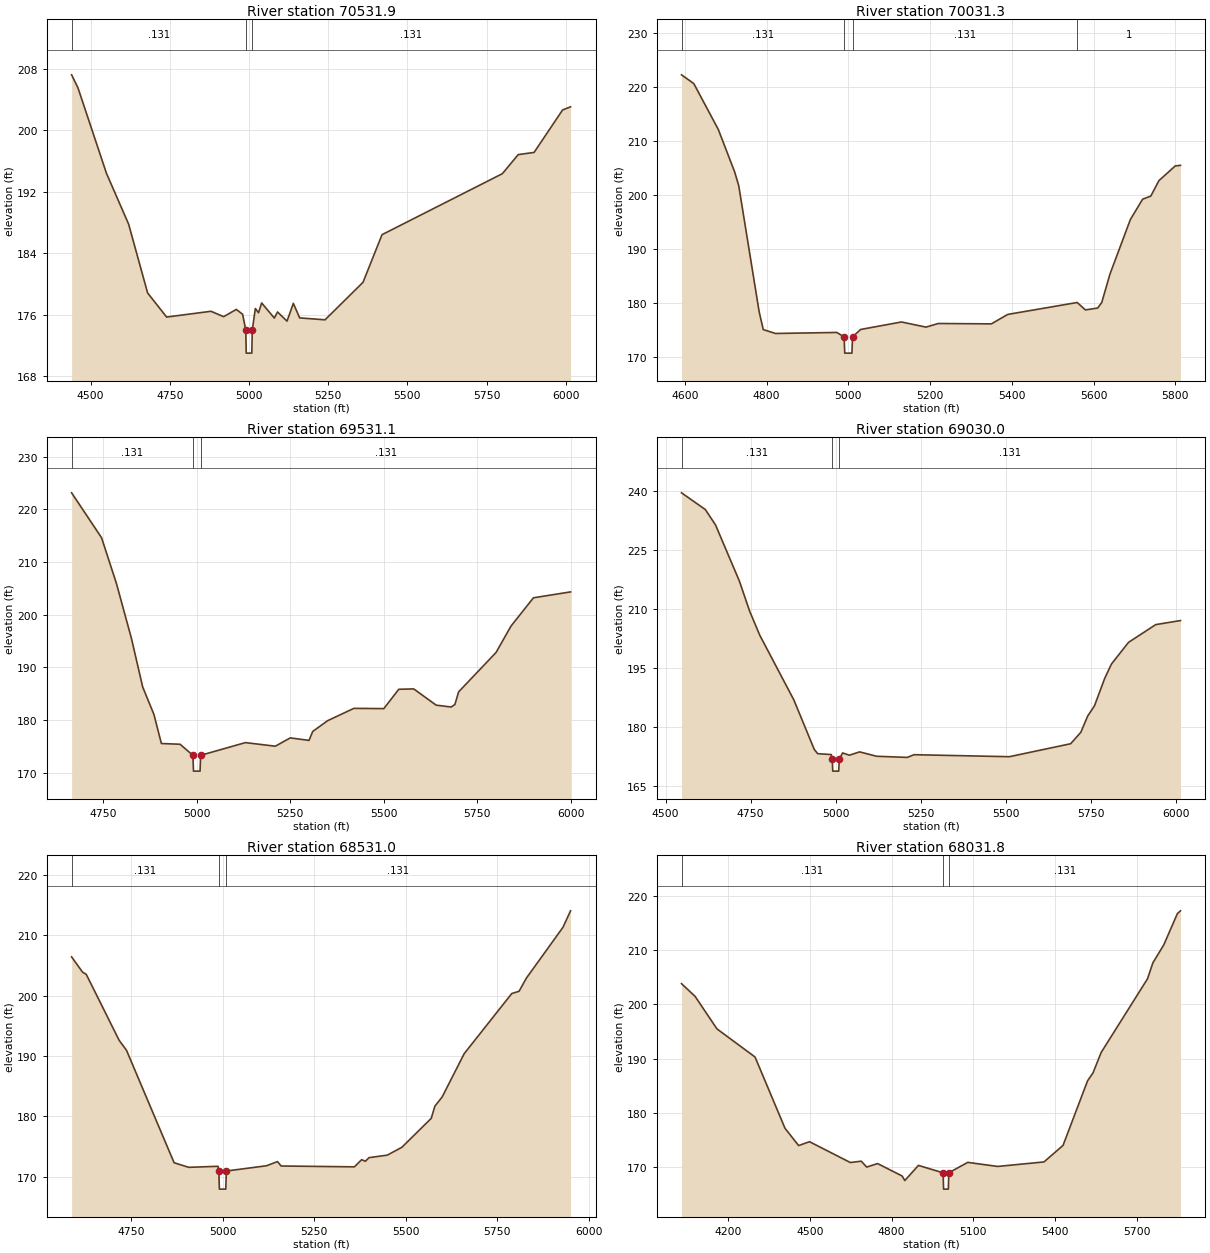
Type RM Length L Ch R = 1 ,70531.9,500.6,500.6,500.6
BEGIN DESCRIPTION:
Rocky Swamp 140.0
END DESCRIPTION:
#Sta/Elev= 30
  4439.9  207.18  4459.9   205.5  4549.9  194.38  4619.9  187.77  4679.9  178.82
  4739.9  175.69  4879.9  176.44  4919.9  175.74  4959.9  176.68  4979.9  176.05
  4989.7     174  4991.2     171  5008.8     171  5010.3     174    5020   176.8
    5030  176.25    5040  177.52    5080  175.56    5090  176.35    5120  175.16
    5140  177.47    5160  175.58    5240  175.33    5360  180.21    5420   186.4
    5800  194.33    5850  196.81    5900  197.09    5990  202.61  6015.2  203.02
#Mann= 3 , 1 , 0
 4439.90   0.131       0  4989.7    0.05       0  5010.3   0.131       0
Bank Sta=4989.70,5010.30
Exp/Cntr=0.3,0.1

Type RM Length L Ch R = 1 ,70031.3,500.2,500.2,500.2
BEGIN DESCRIPTION:
Rocky Swamp 139.0
END DESCRIPTION:
#Sta/Elev= 30
  4591.9  222.19  4621.9  220.57  4681.9  212.07  4721.9   204.2  4731.9  201.64
  4781.9  178.26  4791.9  174.99  4821.9  174.27  4971.9  174.46  4989.7  173.63
  4991.2  170.63  5008.8  170.63  5010.3  173.63    5030  175.01    5130   176.4
    5190  175.45    5220  176.12    5350  176.05    5390   177.8  5559.9  180.01
    5580  178.64    5610  178.98    5620     180    5640  185.25    5690  195.37
    5720  199.15    5740  199.72    5760   202.6    5800  205.32  5812.6  205.42
#Mann= 4 , 1 , 0
 4591.90   0.131       0  4989.7    0.05       0  5010.3   0.131       0
  5559.9       1       0
Bank Sta=4989.70,5010.30
Exp/Cntr=0.3,0.1

Type RM Length L Ch R = 1 ,69531.1,501.1,501.1,501.1
BEGIN DESCRIPTION:
Rocky Swamp 138.0
END DESCRIPTION:
#Sta/Elev= 30
  4665.4  223.14  4745.4  214.63  4785.4   205.9  4825.4   195.5  4855.4   186.3
  4885.4   181.1  4905.4  175.57  4955.4  175.43  4989.7  173.33  4991.2  170.33
  5008.8  170.33  5010.3  173.33    5130  175.74    5210  175.06    5250  176.64
    5300  176.16    5310  177.86    5350  179.91    5420  182.24    5500  182.19
    5540  185.86    5580  185.93    5640  182.85    5680   182.5    5690  182.97
    5700  185.37    5800  192.84    5840  197.85    5900  203.22  5999.2  204.34
#Mann= 3 , 1 , 0
 4665.40   0.131       0  4989.7    0.05       0  5010.3   0.131       0
Bank Sta=4989.70,5010.30
Exp/Cntr=0.3,0.1

Type RM Length L Ch R = 1 ,69030.0,499,499,499
BEGIN DESCRIPTION:
Rocky Swamp 137.0
END DESCRIPTION:
#Sta/Elev= 30
  4546.9  239.59  4616.9  235.34  4646.9   231.4  4716.9  217.13  4746.9  209.51
  4776.9  203.34  4876.9  186.89  4936.9  174.29  4946.9  173.22  4986.9  172.99
  4989.7  171.78  4991.2  168.78  5008.7  168.78  5010.2  171.78    5020  173.41
    5040  172.83    5070  173.68    5120  172.56    5210  172.27    5230  172.96
    5510  172.45    5690  175.75    5720  178.68    5740  182.79    5760   185.4
    5790  192.37    5810  196.05    5860  201.54    5940  206.06  6012.6  207.09
#Mann= 3 , 1 , 0
 4546.90   0.131       0  4989.7    0.05       0  5010.2   0.131       0
Bank Sta=4989.70,5010.20
Exp/Cntr=0.3,0.1

Type RM Length L Ch R = 1 ,68531.0,499.2,499.2,499.2
BEGIN DESCRIPTION:
Rocky Swamp 136.0
END DESCRIPTION:
#Sta/Elev= 30
  4587.6   206.4  4617.6  203.87  4627.6  203.51  4717.6  192.57  4737.6  190.93
  4867.6  172.31  4907.6  171.55  4987.6  171.72  4989.8  170.94  4991.3  167.94
  5008.8  167.94  5010.3  170.94    5120  171.81    5150   172.5    5160  171.77
    5360  171.63    5380  172.82    5390  172.55    5400  173.15    5450  173.57
    5490  174.88    5570  179.66    5580  181.68    5600  183.22    5660  190.37
    5790  200.33    5810  200.71    5830  202.89    5930  211.31  5950.6  214.03
#Mann= 3 , 1 , 0
 4587.60   0.131       0  4989.8    0.05       0  5010.3   0.131       0
Bank Sta=4989.80,5010.30
Exp/Cntr=0.3,0.1

Type RM Length L Ch R = 1 ,68031.8,500.7,500.7,500.7
BEGIN DESCRIPTION:
Rocky Swamp 135.0
END DESCRIPTION:
#Sta/Elev= 30
  4028.9   203.8  4078.9  201.45  4158.9  195.49  4298.9  190.31  4408.9  177.21
  4458.9  174.03  4498.9  174.74  4648.9  170.91  4688.9  171.16  4708.9  170.08
  4748.9  170.72  4838.9  168.44  4848.9   167.6  4898.9  170.38  4989.7  169.02
  4991.2  166.02  5008.8  166.02  5010.3  169.02    5080  170.94    5190  170.19
    5360  171.02    5430  174.06    5520  185.93    5540  187.39    5570  191.15
    5740  204.68    5760  207.63    5800  210.94    5850  216.69  5861.2  217.19
#Mann= 3 , 1 , 0
 4028.90   0.131       0  4989.7    0.05       0  5010.3   0.131       0
Bank Sta=4989.70,5010.30
Exp/Cntr=0.3,0.1