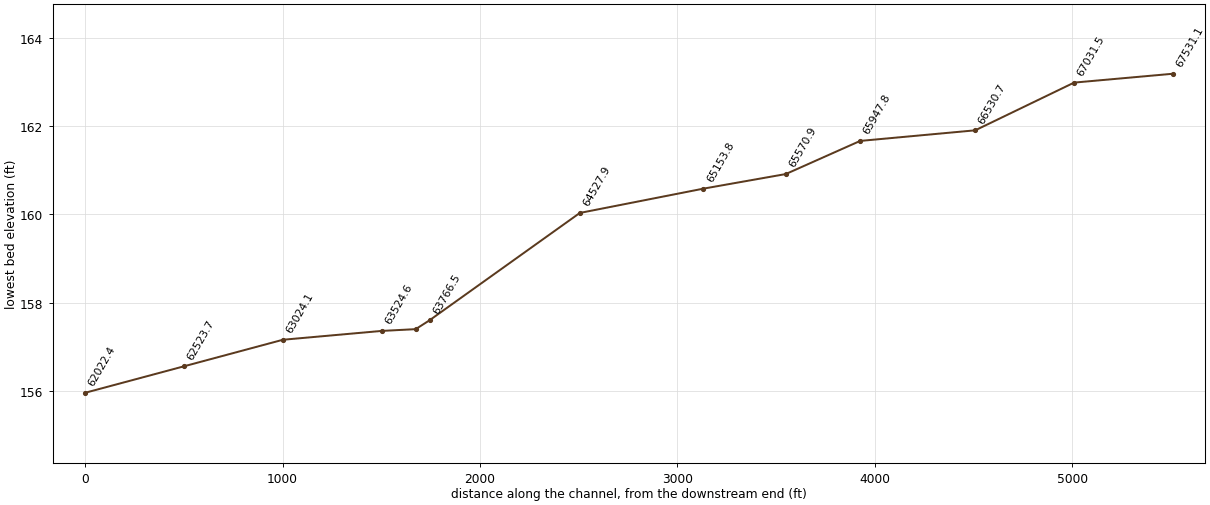
HEC-RAS study 021209_rocky_swamp.prj: Rocky Swamp

--- 021209_rocky_swamp.g01 (geometry) --- (continued)

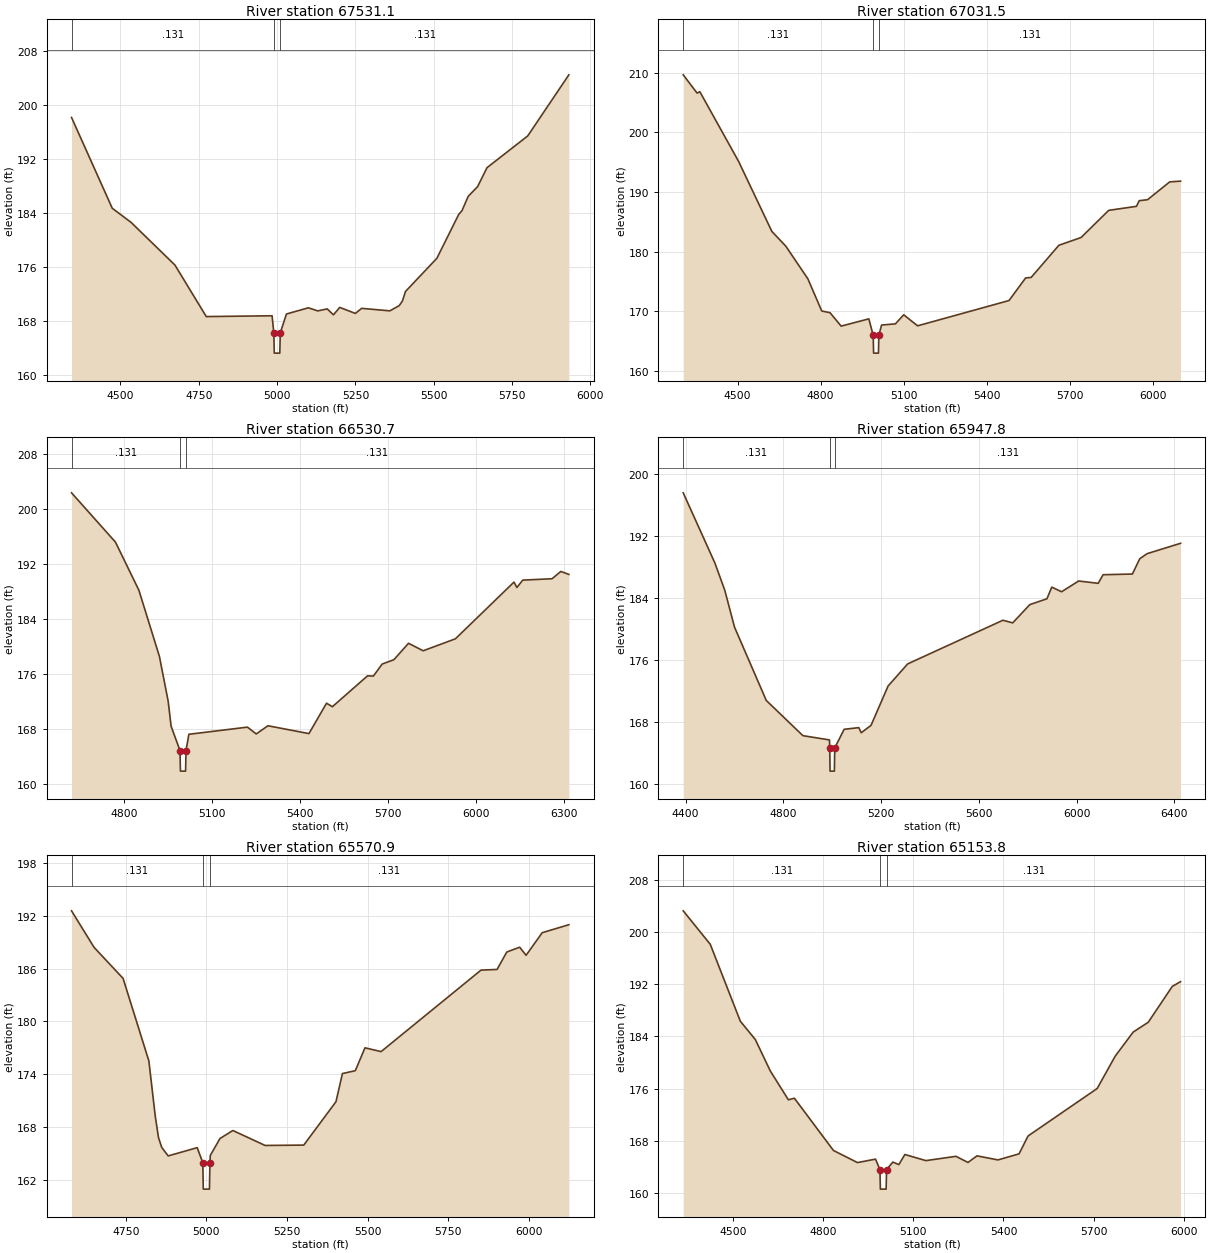
Type RM Length L Ch R = 1 ,67531.1,499.6,499.6,499.6
BEGIN DESCRIPTION:
Rocky Swamp 134.0
END DESCRIPTION:
#Sta/Elev= 30
  4344.2  198.13  4474.2  184.66  4534.2  182.57  4674.2  176.24  4774.2   168.6
  4984.2  168.72  4989.7  166.18  4991.2  163.18  5008.8  163.18  5010.3  166.18
    5030  168.98    5100   169.9    5130  169.44    5160  169.74    5180  168.86
    5200  169.96    5250  169.07    5270  169.82    5360  169.45    5390  170.23
    5400   170.9    5410  172.33    5510  177.24    5580  183.77    5590  184.29
    5610  186.43    5640  187.87    5670  190.68    5800  195.39  5931.2  204.45
#Mann= 3 , 1 , 0
 4344.20   0.131       0  4989.7    0.05       0  5010.3   0.131       0
Bank Sta=4989.70,5010.30
Exp/Cntr=0.3,0.1

Type RM Length L Ch R = 1 ,67031.5,500.8,500.8,500.8
BEGIN DESCRIPTION:
Rocky Swamp 133.0
END DESCRIPTION:
#Sta/Elev= 30
    4304  209.66    4354   206.6    4364  206.83    4504  195.13    4624  183.39
    4674  180.94    4754  175.44    4804  170.05    4834  169.76    4874  167.51
    4974  168.73  4989.7  165.98  4991.2  162.98  5008.7  162.98  5010.2  165.98
    5020  167.69    5070  167.89    5100  169.41    5150  167.56    5480   171.8
    5540  175.59    5560  175.68    5660  181.07    5740  182.37    5840  186.93
    5940   187.6    5950  188.55    5980  188.71    6060   191.7  6099.2  191.83
#Mann= 3 , 1 , 0
 4304.00   0.131       0  4989.7    0.05       0  5010.2   0.131       0
Bank Sta=4989.70,5010.20
Exp/Cntr=0.3,0.1

Type RM Length L Ch R = 1 ,66530.7,582.9,582.9,582.9
BEGIN DESCRIPTION:
Rocky Swamp 132.0
END DESCRIPTION:
#Sta/Elev= 30
  4619.4  202.39  4769.4  195.22  4849.4  188.22  4919.4   178.6  4949.4  172.06
  4959.4  168.43  4989.7   164.9  4991.2   161.9  5008.8   161.9  5010.3   164.9
    5020  167.26    5220   168.3    5250  167.31    5290   168.5    5430  167.36
    5490  171.78    5510  171.27    5630  175.76    5650  175.73    5680  177.48
    5720  178.11    5770   180.5    5820  179.41    5930  181.15    6130   189.4
    6140  188.62    6160  189.69    6260  189.89    6290  190.95  6317.4  190.52
#Mann= 3 , 1 , 0
 4619.40   0.131       0  4989.7    0.05       0  5010.3   0.131       0
Bank Sta=4989.70,5010.30
Exp/Cntr=0.3,0.1

Type RM Length L Ch R = 1 ,65947.8,376.9,376.9,376.9
BEGIN DESCRIPTION:
Rocky Swamp 131.0
END DESCRIPTION:
#Sta/Elev= 30
    4390  197.61    4520  188.52    4560  185.04    4600  180.26    4730  170.79
    4880  166.24  4988.8  165.69  4989.7  164.66  4991.2  161.66  5008.8  161.66
  5010.3  164.66  5048.8  167.06  5108.8  167.28  5118.8  166.62  5158.8  167.57
  5228.8  172.66  5308.8  175.51  5698.8  181.15  5738.8  180.81  5808.8  183.17
  5878.8  183.92  5898.8  185.43  5938.8  184.83  6008.8  186.22  6088.8  185.92
  6108.8  187.03  6228.8  187.12  6258.8  189.09  6288.8  189.75  6425.9  191.09
#Mann= 3 , 1 , 0
 4390.00   0.131       0  4989.7    0.05       0  5010.3   0.131       0
Bank Sta=4989.70,5010.30
Exp/Cntr=0.3,0.1

Type RM Length L Ch R = 1 ,65570.9,417.1,417.1,417.1
BEGIN DESCRIPTION:
Rocky Swamp 130.0
END DESCRIPTION:
#Sta/Elev= 30
  4581.5  192.58  4651.5  188.42  4741.5  184.89  4821.5   175.5  4841.5  169.16
  4851.5  166.76  4861.5  165.65  4881.5  164.69  4971.5  165.63  4988.9  163.91
  4990.4  160.91  5009.5  160.91    5011  163.91  5012.2  164.75  5042.2  166.67
  5082.2  167.58  5182.2  165.88  5302.2  165.92  5402.2  170.86  5422.2  174.06
  5462.2  174.39  5492.2  176.99  5542.2  176.56  5852.2  185.83  5902.2  185.91
  5932.2  187.89  5972.2  188.44  5992.2  187.52  6042.2  190.09  6124.9     191
#Mann= 3 , 1 , 0
 4581.50   0.131       0  4988.9    0.05       0    5011   0.131       0
Bank Sta=4988.90,5011.00
Exp/Cntr=0.3,0.1

Type RM Length L Ch R = 1 ,65153.8,625.9,625.9,625.9
BEGIN DESCRIPTION:
Rocky Swamp 129.0
END DESCRIPTION:
#Sta/Elev= 30
  4334.2  203.26  4424.2  198.13  4524.2  186.34  4574.2  183.52  4624.2  178.69
  4684.2  174.28  4704.2  174.52  4834.2  166.51  4914.2  164.65  4974.2  165.18
  4988.9  163.58  4990.4  160.58  5009.5  160.58    5011  163.58  5031.9  164.73
  5051.9  164.34  5071.9  165.89  5141.9  164.95  5241.9  165.61  5281.9  164.67
  5311.9  165.68  5381.9  165.06  5451.9  165.99  5481.9  168.73  5711.9  176.01
  5771.9  180.97  5831.9  184.67  5881.9  186.17  5961.9  191.67  5989.4   192.4
#Mann= 3 , 1 , 0
 4334.20   0.131       0  4988.9    0.05       0    5011   0.131       0
Bank Sta=4988.90,5011.00
Exp/Cntr=0.3,0.1

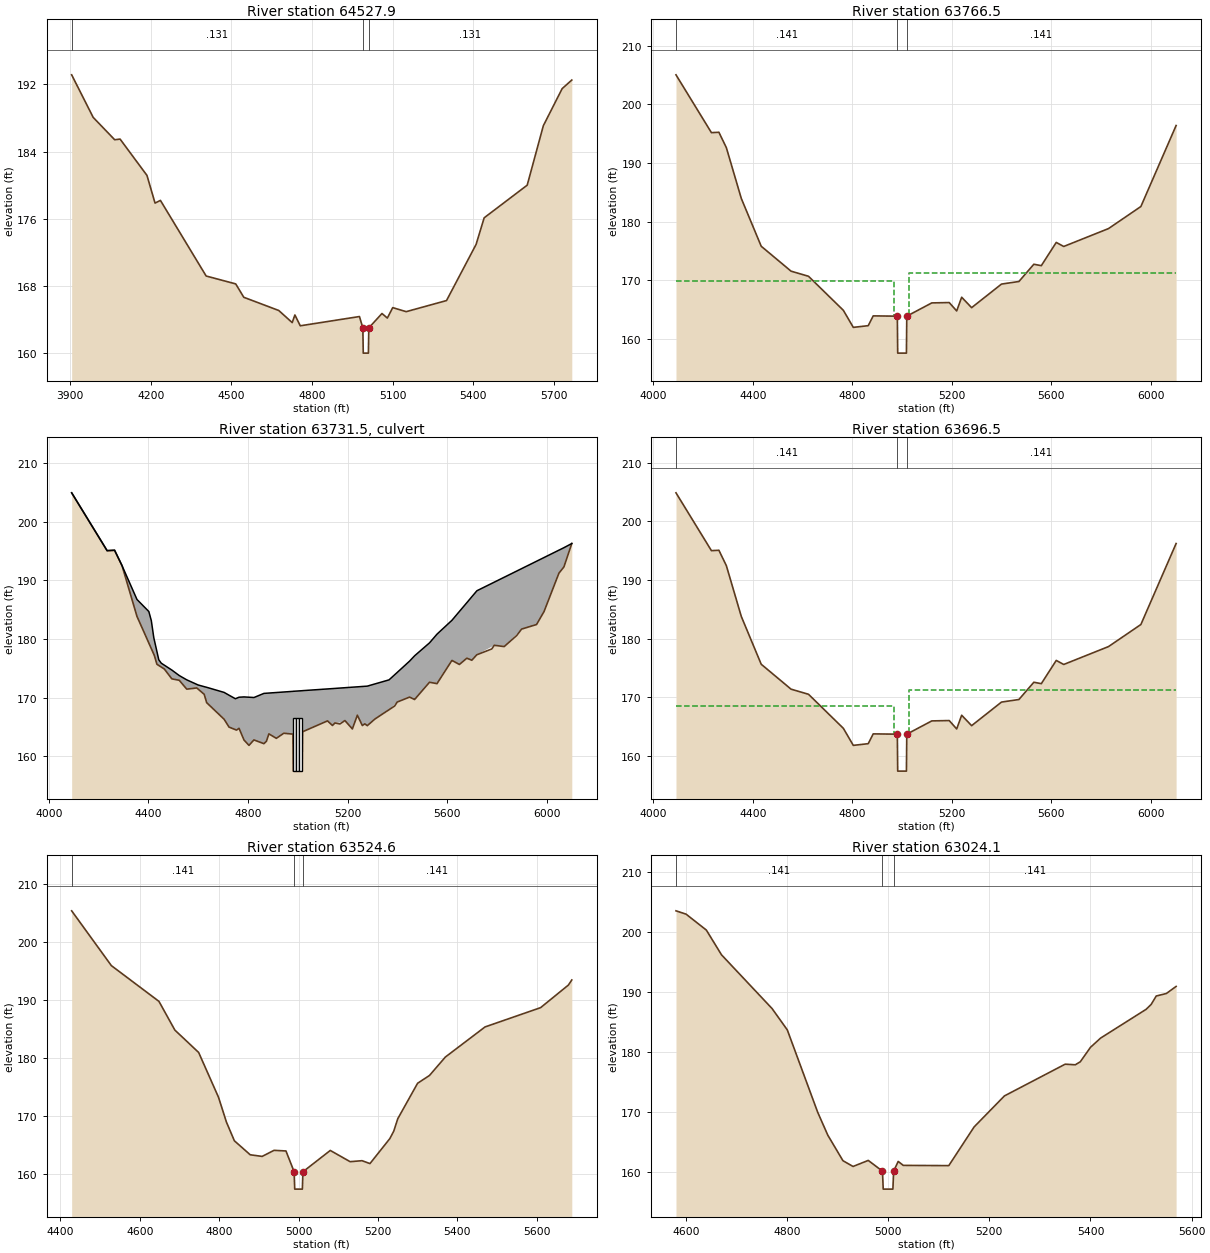
Type RM Length L Ch R = 1 ,64527.9,761.4,761.4,761.4
BEGIN DESCRIPTION:
Rocky Swamp 128.0
END DESCRIPTION:
#Sta/Elev= 30
  3906.2  193.12  3986.2  188.06  4066.2   185.4  4086.2  185.48  4186.2  181.16
  4216.2  177.87  4236.2  178.19  4406.2   169.2  4516.2  168.26  4546.2  166.67
  4676.2   165.1  4726.2  163.66  4736.2  164.57  4756.2  163.28  4976.2  164.38
  4988.9  163.03  4990.4  160.03  5009.5  160.03    5011  163.03    5060  164.74
    5080   164.2    5100  165.44    5150  164.96    5300  166.28    5410  172.96
    5440  176.12    5600     180    5660  187.07    5730  191.48  5765.8   192.5
#Mann= 3 , 1 , 0
 3906.20   0.131       0  4988.9    0.05       0    5011   0.131       0
Bank Sta=4988.90,5011.00
Exp/Cntr=0.5,0.3

Type RM Length L Ch R = 1 ,63766.5,70,70,70
BEGIN DESCRIPTION:
Upstream Section of Bridge/Culvert/Weir
END DESCRIPTION:
#Sta/Elev= 30
  4091.7  205.04  4234.1  195.18  4264.1  195.25  4294.1  192.62  4354.1  183.97
  4434.1  175.82  4554.1  171.57  4624.1   170.7  4764.1   164.9  4804.1  161.99
  4864.1  162.28  4884.1  163.95    4981   163.9  4982.5   157.6  5017.5   157.6
    5019   163.9  5119.5  166.16  5189.5  166.22  5219.5  164.79  5239.5  167.13
  5279.5  165.35  5399.5  169.37  5469.5  169.81  5529.5  172.75  5559.5  172.51
  5619.5  176.47  5649.5  175.78  5829.5  178.83  5959.5  182.59  6101.1   196.4
#Mann= 3 , 1 , 0
 4091.70   0.141       0    4981    0.05       0    5019   0.141       0
#XS Ineff= 2 , 0
       0    4969  169.86    5028       0  171.29
Bank Sta=4981.00,5019.00
Exp/Cntr=0.5,0.3

Type RM Length L Ch R = 2 ,63731.5,,,
BEGIN DESCRIPTION:
NC 561y-TOR
Structure ID: NC 561y
Approximate Survey Structure
END DESCRIPTION:
Bridge Culvert--1,0,-1,-1, 0
Deck Dist Width WeirC Skew NumUp NumDn MinLoCord MaxHiCord MaxSubmerge Is_Ogee
10,50,3,, 60, 60,,,0.95,0,1,1,,
  4091.7  4234.1  4264.1  4294.1  4354.1  4401.7  4411.7  4421.7  4434.1  4441.7
  4451.7  4494.1  4524.1  4554.1  4599.5  4624.1  4634.1  4704.1  4724.1  4749.5
  4764.1  4784.1  4804.1  4824.1  4864.1  4874.1  4884.1  4914.1  4944.1    4981
  4982.5  5017.5    5019  5019.5  5119.5  5139.5  5189.5  5219.5  5239.5  5259.5
  5279.5  5366.9  5399.5  5449.5  5469.5  5529.5  5559.5  5619.5  5649.5  5679.5
  5699.5  5719.9  5789.5  5829.5  5899.5  5959.5  5989.5  6049.5  6069.5  6101.1
  204.94  195.08  195.15  192.52  186.76  184.71  183.16  180.24  177.91  176.48
   175.9  174.73  173.79  173.06  172.19   171.9  171.79  170.92  170.44  169.84
   170.1  170.15   170.1  170.05  170.75  170.78  170.81   170.9  170.99   171.1
  171.11  171.21  171.21  171.22  171.51  171.57  171.72  171.81  171.87  171.93
  171.99  173.06  174.32  176.26  177.16  179.37  180.85  183.21  184.72  186.22
  187.23  188.25  189.71  190.55  192.02  193.28  193.91  195.17  195.59   196.3
  204.94  195.08  195.15  192.52  183.87  179.33  178.38  177.42  175.72  175.51
  175.24  173.23  172.98  171.47  171.49   170.6  169.17  166.34     165  164.57
   164.8   162.8  161.89  162.82  162.18  162.58  163.85  163.09  163.96   163.8
   157.5   157.5   163.8  164.21  166.06  165.28  166.12  164.69  167.03  165.27
  165.25  167.97  169.27  170.12  169.71  172.65  172.41  176.37  175.68  176.75
   176.4  177.34  178.95  178.73  181.71  182.49  184.69  191.25  192.31   196.3
  4091.7  4234.1  4264.1  4294.1  4354.1  4401.7  4411.7  4421.7  4434.1  4441.7
  4451.7  4494.1  4524.1  4554.1  4599.5  4624.1  4634.1  4704.1  4724.1  4749.5
  4764.1  4784.1  4804.1  4824.1  4864.1  4874.1  4884.1  4914.1  4944.1    4981
  4982.5  5017.5    5019  5019.5  5119.5  5139.5  5189.5  5219.5  5239.5  5259.5
  5279.5  5366.9  5399.5  5449.5  5469.5  5529.5  5559.5  5619.5  5649.5  5679.5
  5699.5  5719.9  5789.5  5829.5  5899.5  5959.5  5989.5  6049.5  6069.5  6101.1
  204.89  195.04  195.11  192.48  186.76  184.71  183.16  180.24  177.91  176.48
   175.9  174.73  173.79  173.06  172.19   171.9  171.79  170.92  170.44  169.84
   170.1  170.15   170.1  170.05  170.75  170.78  170.81   170.9  170.99   171.1
  171.11  171.21  171.21  171.22  171.51  171.57  171.72  171.81  171.87  171.93
  171.99  173.06  174.32  176.26  177.16  179.37  180.85  183.21  184.72  186.22
  187.23  188.25  189.71  190.55  192.02  193.28  193.91  195.17  195.59  196.25
  204.84  194.98  195.05  192.42  183.77  179.23  178.28  177.32  175.62  175.41
  175.14  173.13  172.88  171.37  171.39   170.5  169.07  166.24   164.9  164.47
   164.7   162.7  161.79  162.72  162.08  162.48  163.75  162.99  163.86   163.7
   157.4   157.4   163.7  164.11  165.96  165.18  166.02  164.59  166.93  165.17
  165.15  167.87  169.17  170.02  169.61  172.55  172.31  176.27  175.58  176.65
   176.3  177.24  178.85  178.63  181.61  182.39  184.59  191.15  192.21   196.2
BR Coef= 1 , 0 , 0 ,1.25, 0 ,,,0.8,-1,2,0,
Wspro=,,,, 1 ,,,, 0 ,,,, 0 ,,,,-1 ,-1 ,-1 , 0 , 0 , 0 , 0 , 0
Culvert=2,9.0,11.0,50.0,0.015,0.4,1.0,8,1,157.50,4988.04,157.40,4988.04,Culvert #1  ,0,10
Culvert=2,9.0,11.0,50.0,0.015,0.4,1.0,8,1,157.50,5000.04,157.40,5000.04,Culvert #2  ,0,10
Culvert=2,9.0,11.0,50.0,0.015,0.4,1.0,8,1,157.50,5012.04,157.40,5012.04,Culvert #3  ,0,10
BC Design=,, 0 ,, 0 ,,,,,,
BR U #Sta/Elev= 91
  4091.7  204.94  4234.1  195.08  4241.7   195.1  4264.1  195.15  4281.7  193.61
  4294.1  192.52  4354.1  183.87  4384.1  181.02  4401.7  179.33  4411.7  178.38
  4421.7  177.42  4424.1  177.19  4434.1  175.72  4441.7  175.51  4451.7  175.24
  4459.5  175.03  4464.1   174.9  4494.1  173.23  4524.1  172.98  4549.5   171.7
  4554.1  171.47  4559.5   171.5  4579.5   171.6  4594.1  171.68  4599.5  171.49
  4624.1   170.6  4634.1  169.17  4699.5  166.53  4704.1  166.34  4724.1     165
  4749.5  164.57  4754.1  164.49  4764.1   164.8  4769.5  164.26  4784.1   162.8
  4804.1  161.89  4824.1  162.82  4829.5  162.73  4839.5  162.57  4864.1  162.18
  4874.1  162.58  4884.1  163.85  4914.1  163.09  4944.1  163.96    4981   163.8
  4982.5   157.5  5017.5   157.5    5019   163.8  5019.5  164.21  5119.5  166.06
  5139.5  165.28  5149.5  165.71  5169.5  165.54  5189.5  166.12  5219.5  164.69
  5239.5  167.03  5259.5  165.27  5269.5  165.56  5279.5  165.25  5306.9  166.26
  5309.5  166.36  5316.9  166.57  5366.9  167.97  5389.5  168.61  5399.5  169.27
  5449.5  170.12  5466.9  169.76  5469.5  169.71  5476.9  170.07  5499.7  171.19
  5529.5  172.65  5549.7  172.49  5559.5  172.41  5589.7   174.4  5619.5  176.37
  5619.7  176.37  5649.5  175.68  5679.5  176.75  5699.5   176.4  5719.5  177.33
  5719.9  177.34  5779.5  178.33  5789.5  178.95  5829.5  178.73  5879.5  180.61
  5899.5  181.71  5959.5  182.49  5989.5  184.69  6049.5  191.25  6069.5  192.31
  6101.1   196.3
BR U #Mann= 3
 4091.70   0.141    4981    0.05    5019   0.141
BR U Banks=4981.00,5019.00
BR D #Sta/Elev= 91
  4091.7  204.84  4234.1  194.98  4241.7     195  4264.1  195.05  4281.7  193.51
  4294.1  192.42  4354.1  183.77  4384.1  180.92  4401.7  179.23  4411.7  178.28
  4421.7  177.32  4424.1  177.09  4434.1  175.62  4441.7  175.41  4451.7  175.14
  4459.5  174.93  4464.1   174.8  4494.1  173.13  4524.1  172.88  4549.5   171.6
  4554.1  171.37  4559.5   171.4  4579.5   171.5  4594.1  171.58  4599.5  171.39
  4624.1   170.5  4634.1  169.07  4699.5  166.43  4704.1  166.24  4724.1   164.9
  4749.5  164.47  4754.1  164.39  4764.1   164.7  4769.5  164.16  4784.1   162.7
  4804.1  161.79  4824.1  162.72  4829.5  162.63  4839.5  162.47  4864.1  162.08
  4874.1  162.48  4884.1  163.75  4914.1  162.99  4944.1  163.86    4981   163.7
  4982.5   157.4  5017.5   157.4    5019   163.7  5019.5  164.11  5119.5  165.96
  5139.5  165.18  5149.5  165.61  5169.5  165.44  5189.5  166.02  5219.5  164.59
  5239.5  166.93  5259.5  165.17  5269.5  165.46  5279.5  165.15  5306.9  166.16
  5309.5  166.26  5316.9  166.47  5366.9  167.87  5389.5  168.51  5399.5  169.17
  5449.5  170.02  5466.9  169.66  5469.5  169.61  5476.9  169.97  5499.7  171.09
  5529.5  172.55  5549.7  172.39  5559.5  172.31  5589.7   174.3  5619.5  176.27
  5619.7  176.27  5649.5  175.58  5679.5  176.65  5699.5   176.3  5719.5  177.23
  5719.9  177.24  5779.5  178.23  5789.5  178.85  5829.5  178.63  5879.5  180.51
  5899.5  181.61  5959.5  182.39  5989.5  184.59  6049.5  191.15  6069.5  192.21
  6101.1   196.2
BR D #Mann= 3
 4091.70   0.141    4981    0.05    5019   0.141
BR D Banks=4981.00,5019.00

Type RM Length L Ch R = 1 ,63696.5,171.9,171.9,171.9
BEGIN DESCRIPTION:
Downstream Section of Bridge/Culvert/Weir
END DESCRIPTION:
#Sta/Elev= 30
  4091.7  204.84  4234.1  194.98  4264.1  195.05  4294.1  192.42  4354.1  183.77
  4434.1  175.62  4554.1  171.37  4624.1   170.5  4764.1   164.7  4804.1  161.79
  4864.1  162.08  4884.1  163.75    4981   163.7  4982.5   157.4  5017.5   157.4
    5019   163.7  5119.5  165.96  5189.5  166.02  5219.5  164.59  5239.5  166.93
  5279.5  165.15  5399.5  169.17  5469.5  169.61  5529.5  172.55  5559.5  172.31
  5619.5  176.27  5649.5  175.58  5829.5  178.63  5959.5  182.39  6101.1   196.2
#Mann= 3 , 1 , 0
 4091.70   0.141       0    4981    0.05       0    5019   0.141       0
#XS Ineff= 2 , 0
       0    4969  168.42    5028       0  171.29
Bank Sta=4981.00,5019.00
Exp/Cntr=0.5,0.3

Type RM Length L Ch R = 1 ,63524.6,500.5,500.5,500.5
BEGIN DESCRIPTION:
Rocky Swamp 126.0
END DESCRIPTION:
#Sta/Elev= 30
  4428.3  205.42  4528.3  195.96  4648.3  189.78  4688.3  184.83  4748.3  180.96
  4798.3  173.23  4818.3  168.94  4838.3  165.71  4878.3  163.29  4908.3  163.01
  4938.3  164.06  4968.3  163.95  4988.9  160.36  4990.4  157.36  5009.6  157.36
  5011.1  160.36    5080  164.04    5130   162.1    5160  162.27    5180  161.77
    5230  166.08    5240  167.38    5250  169.51    5300  175.64    5330  176.99
    5370  180.17    5470  185.37    5610   188.7    5680   192.6  5688.6  193.48
#Mann= 3 , 1 , 0
 4428.30   0.141       0  4988.9    0.05       0  5011.1   0.141       0
Bank Sta=4988.90,5011.10
Exp/Cntr=0.3,0.1

Type RM Length L Ch R = 1 ,63024.1,500.4,500.4,500.4
BEGIN DESCRIPTION:
Rocky Swamp 125.0
END DESCRIPTION:
#Sta/Elev= 30
  4580.8  203.58  4600.8  203.02  4640.8  200.37  4670.8  196.24  4770.8  187.27
  4800.8  183.72  4860.8     170  4880.8  166.17  4910.8   161.9  4930.8  160.94
  4960.8  161.95  4988.9  160.16  4990.4  157.16  5009.5  157.16    5011  160.16
    5020  161.78    5030  161.12    5120  161.08    5170  167.53    5230  172.71
    5350     178    5370   177.9    5380  178.41    5400  180.81    5420  182.35
    5510  187.15    5520  187.97    5530  189.37    5550  189.79  5569.3  190.97
#Mann= 3 , 1 , 0
 4580.80   0.141       0  4988.9    0.05       0    5011   0.141       0
Bank Sta=4988.90,5011.00
Exp/Cntr=0.3,0.1

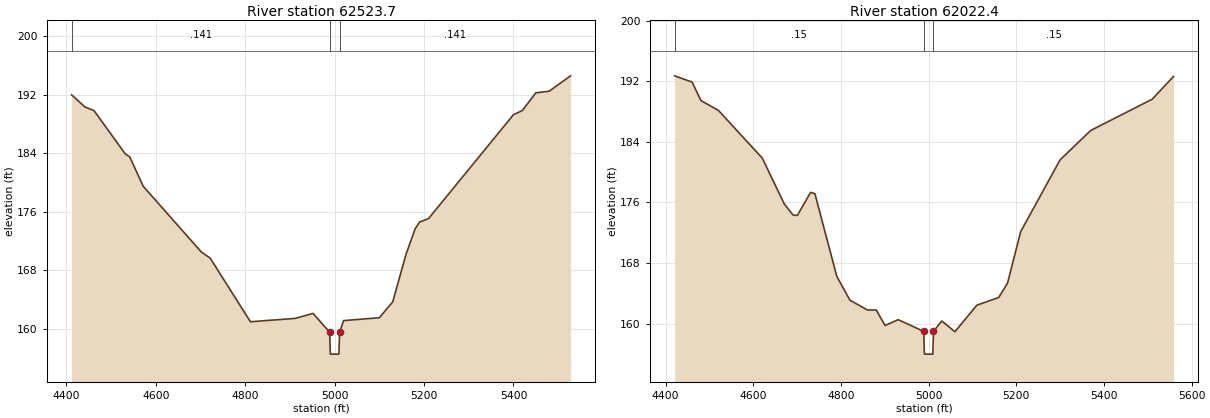
Type RM Length L Ch R = 1 ,62523.7,501.3,501.3,501.3
BEGIN DESCRIPTION:
Rocky Swamp 124.0
END DESCRIPTION:
#Sta/Elev= 27
  4411.7  191.97  4441.7  190.31  4461.7  189.83  4531.7  183.91  4541.7   183.5
  4571.7   179.5  4701.7  170.52  4721.7  169.67  4811.7  160.98  4911.7  161.44
  4951.7  162.12  4988.9  159.56  4990.4  156.56  5009.6  156.56  5011.1  159.56
    5020  161.14    5100  161.53    5130   163.7    5160  170.24    5180  173.66
    5190   174.6    5210  175.07    5400  189.26    5420  189.83    5450  192.25
    5480  192.47  5527.7  194.57
#Mann= 3 , 1 , 0
 4411.70   0.141       0  4988.9    0.05       0  5011.1   0.141       0
Bank Sta=4988.90,5011.10
Exp/Cntr=0.3,0.1

Type RM Length L Ch R = 1 ,62022.4,499.7,499.7,499.7
BEGIN DESCRIPTION:
Rocky Swamp 123.0
END DESCRIPTION:
#Sta/Elev= 30
  4420.6  192.72  4460.6  191.89  4480.6  189.46  4520.6  188.15  4620.6  181.85
  4670.6  175.81  4690.6  174.34  4700.6  174.28  4730.6  177.32  4740.6  177.16
  4790.6  166.22  4820.6  163.08  4860.6  161.79  4880.6  161.79  4900.6  159.74
  4930.6  160.51  4988.9  158.96  4990.4  155.96  5009.6  155.96  5011.1  158.96
    5030  160.34    5060  158.92    5110  162.42    5160  163.45    5180  165.34
    5210  172.14    5300  181.63    5370  185.51    5510  189.63  5558.7  192.64
#Mann= 3 , 1 , 0
 4420.60    0.15       0  4988.9    0.05       0  5011.1    0.15       0
Bank Sta=4988.90,5011.10
Exp/Cntr=0.3,0.1