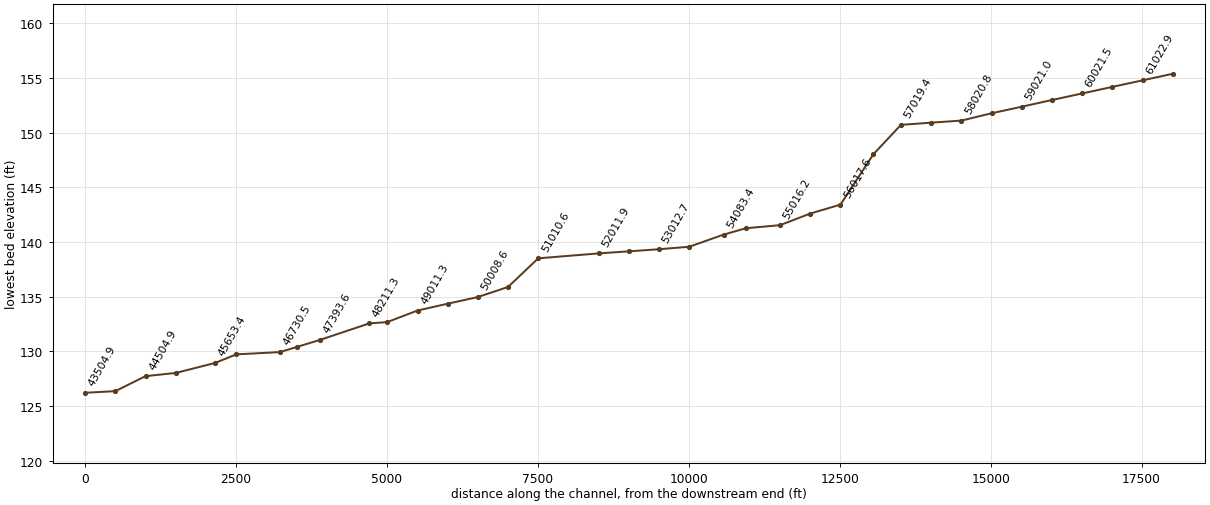
HEC-RAS study 021209_rocky_swamp.prj: Rocky Swamp

--- 021209_rocky_swamp.g01 (geometry) --- (continued)

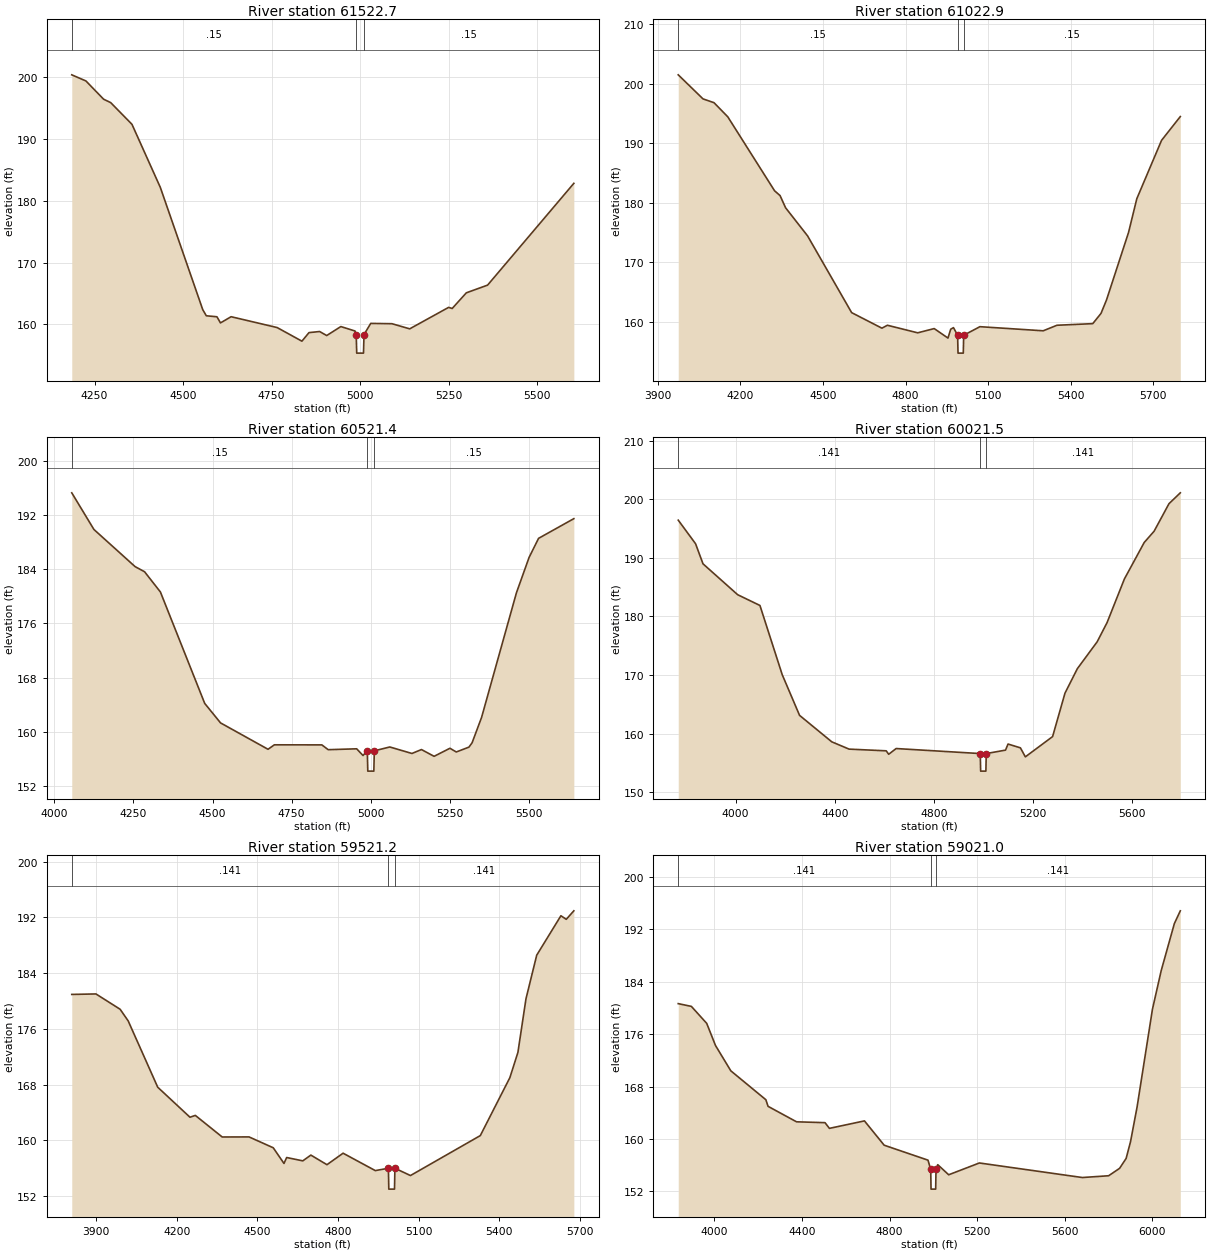
Type RM Length L Ch R = 1 ,61522.7,499.8,499.8,499.8
BEGIN DESCRIPTION:
Rocky Swamp 122.0
END DESCRIPTION:
#Sta/Elev= 30
  4185.6  200.31  4225.6  199.32  4275.6  196.37  4295.6  195.82  4355.6  192.32
  4435.6  182.15  4555.6  162.38  4565.6   161.4  4595.6  161.24  4605.6  160.25
  4635.6  161.25  4765.6   159.5  4835.6   157.3  4855.6  158.68  4885.6  158.86
  4905.6  158.21  4945.6  159.66  4985.6  158.94  4988.9  158.37  4990.4  155.37
  5009.5  155.37    5011  158.37    5030  160.17    5090  160.12    5140  159.29
    5250  162.76    5260  162.58    5300  165.11    5360  166.35  5603.6  182.79
#Mann= 3 , 1 , 0
 4185.60    0.15       0  4988.9    0.05       0    5011    0.15       0
Bank Sta=4988.90,5011.00
Exp/Cntr=0.3,0.1

Type RM Length L Ch R = 1 ,61022.9,501.5,501.5,501.5
BEGIN DESCRIPTION:
Rocky Swamp 121.0
END DESCRIPTION:
#Sta/Elev= 30
    3974   201.5    4064  197.46    4104  196.82    4154  194.45    4324  182.03
    4344  181.22    4364  179.18    4444  174.45    4604  161.57    4714  158.96
    4734  159.45    4844  158.18    4904  158.89    4954   157.3    4964  158.79
    4974  159.05    4989  157.77  4990.5  154.77  5009.6  154.77  5011.1  157.77
    5070  159.21    5300  158.52    5350  159.45    5480  159.72    5510  161.44
    5530   163.7    5610  175.03    5640  180.69    5730   190.5  5798.1  194.49
#Mann= 3 , 1 , 0
 3974.00    0.15       0    4989    0.05       0  5011.1    0.15       0
Bank Sta=4989.00,5011.10
Exp/Cntr=0.3,0.1

Type RM Length L Ch R = 1 ,60521.4,499.9,499.9,499.9
BEGIN DESCRIPTION:
Rocky Swamp 120.0
END DESCRIPTION:
#Sta/Elev= 30
  4055.4  195.32  4125.4   189.9  4255.4  184.41  4285.4  183.65  4335.4  180.66
  4475.4  164.18  4525.4   161.3  4675.4   157.4  4695.4  158.06  4845.4  158.05
  4865.4  157.34  4955.4  157.47  4975.4  156.48    4989  157.17  4990.5  154.17
  5009.6  154.17  5011.1  157.17    5060  157.74    5130  156.78    5160  157.36
    5200  156.36    5250  157.55    5270     157    5310  157.72    5320  158.36
    5350  162.12    5460  180.53    5500  185.77    5530  188.59  5641.4   191.5
#Mann= 3 , 1 , 0
 4055.40    0.15       0    4989    0.05       0  5011.1    0.15       0
Bank Sta=4989.00,5011.10
Exp/Cntr=0.3,0.1

Type RM Length L Ch R = 1 ,60021.5,500.3,500.3,500.3
BEGIN DESCRIPTION:
Rocky Swamp 119.0
END DESCRIPTION:
#Sta/Elev= 30
  3768.1  196.46  3838.1  192.43  3868.1     189  4008.1  183.72  4098.1  181.88
  4188.1  170.05  4258.1   163.1  4388.1  158.58  4458.1  157.33  4608.1  157.04
  4618.1  156.45  4648.1  157.43  4987.9  156.57  4989.4  153.57  5010.6  153.57
  5012.1  156.57    5090  157.16    5100   158.2    5150  157.55    5170  156.01
    5280  159.47    5330  166.89    5380  171.08    5460  175.67    5500  178.95
    5570  186.41    5650  192.64    5690  194.57    5750  199.27  5795.8  201.13
#Mann= 3 , 1 , 0
 3768.10   0.141       0  4987.9    0.05       0  5012.1   0.141       0
Bank Sta=4987.90,5012.10
Exp/Cntr=0.3,0.1

Type RM Length L Ch R = 1 ,59521.2,500.2,500.2,500.2
BEGIN DESCRIPTION:
Rocky Swamp 118.0
END DESCRIPTION:
#Sta/Elev= 30
  3809.2  180.94  3899.2  181.01  3989.2  178.81  4019.2  177.14  4129.2  167.61
  4249.2   163.3  4269.2  163.56  4369.2  160.46  4469.2  160.47  4559.2  158.91
  4599.2  156.66  4609.2  157.51  4669.2  157.03  4699.2  157.86  4759.2  156.48
  4819.2  158.13  4939.2  155.63  4987.9  155.97  4989.4  152.97  5010.6  152.97
  5012.1  155.97    5070  154.92    5330  160.66    5440  168.98    5470  172.61
    5500  180.31    5540  186.58    5630  192.24    5650  191.73  5678.2  192.95
#Mann= 3 , 1 , 0
 3809.20   0.141       0  4987.9    0.05       0  5012.1   0.141       0
Bank Sta=4987.90,5012.10
Exp/Cntr=0.3,0.1

Type RM Length L Ch R = 1 ,59021.0,499.2,499.2,499.2
BEGIN DESCRIPTION:
Rocky Swamp 117.0
END DESCRIPTION:
#Sta/Elev= 30
  3835.5  180.66  3895.5  180.24  3965.5  177.65  4005.5  174.28  4075.5  170.41
  4235.5     166  4245.5  164.99  4375.5  162.63  4505.5   162.5  4525.5  161.63
  4685.5  162.77  4775.5  159.06  4975.5  156.78  4987.9  155.36  4989.4  152.36
  5010.6  152.36  5012.1  155.36    5020  156.09    5070  154.55    5210  156.35
    5680  154.13    5800   154.4    5850  155.53    5880  157.05    5900   159.6
    5930  164.91    6000   179.8    6040   185.7    6100  192.87  6127.2  194.82
#Mann= 3 , 1 , 0
 3835.50   0.141       0  4987.9    0.05       0  5012.1   0.141       0
Bank Sta=4987.90,5012.10
Exp/Cntr=0.3,0.1

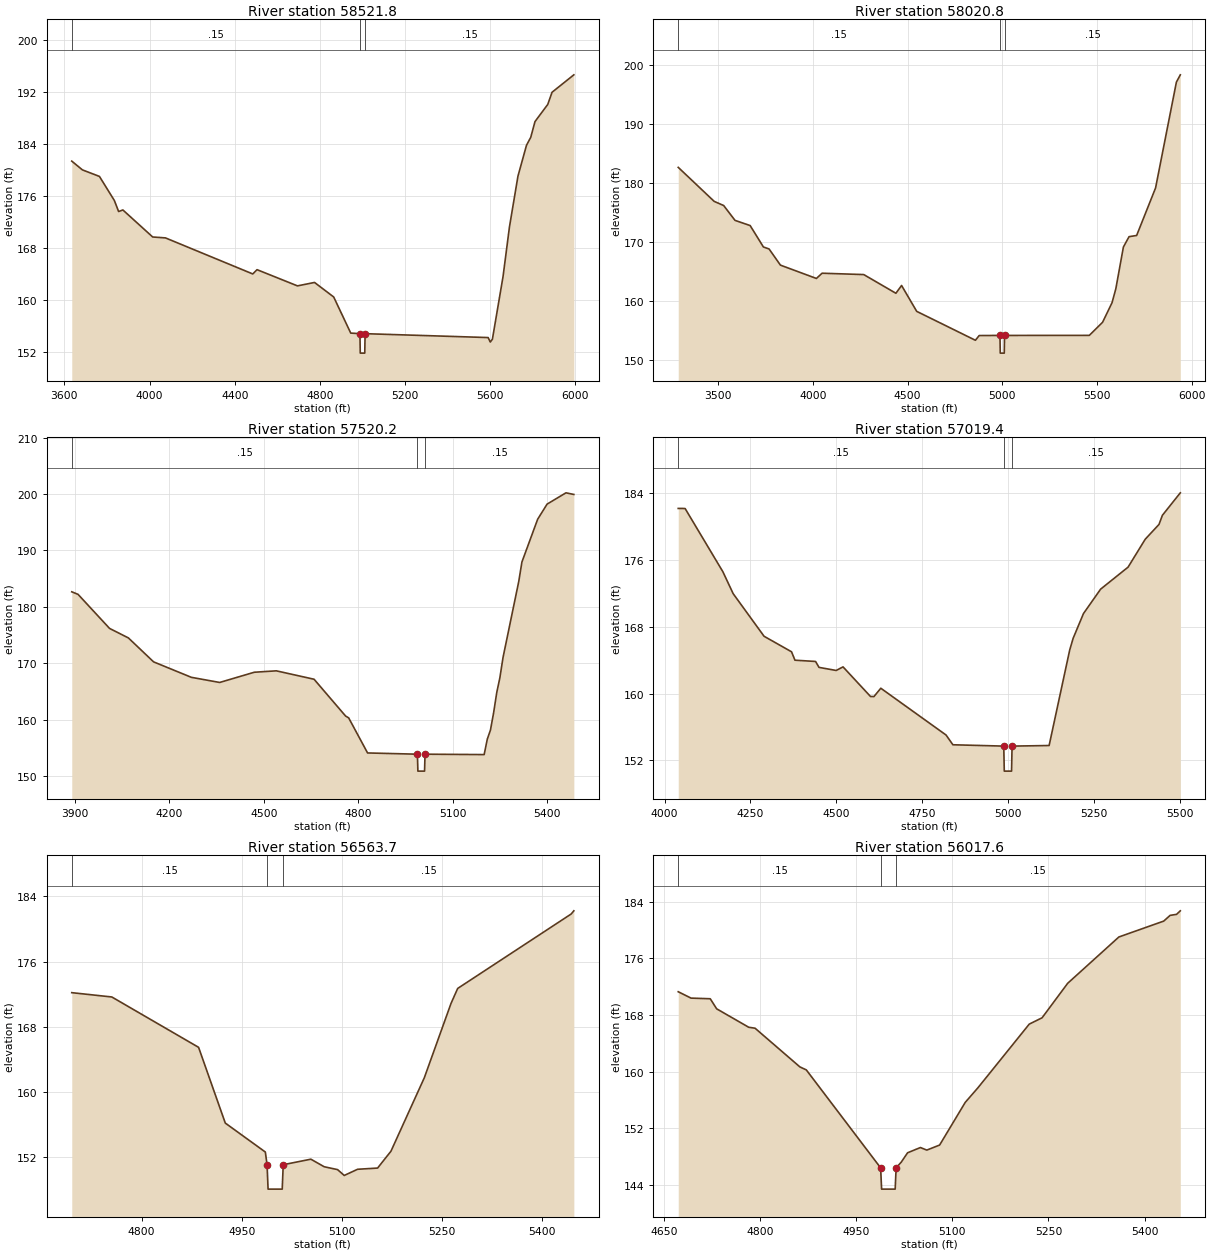
Type RM Length L Ch R = 1 ,58521.8,501,501,501
BEGIN DESCRIPTION:
Rocky Swamp 116.0
END DESCRIPTION:
#Sta/Elev= 30
  3634.7  181.37  3684.7  180.02  3764.7  179.01  3834.7   175.3  3854.7   173.6
  3874.7  173.84  4014.7  169.67  4074.7  169.53  4484.7  163.97  4504.7  164.63
  4694.7  162.13  4774.7  162.66  4864.7  160.42  4944.7  154.85  4987.9  154.76
  4989.4  151.76  5010.6  151.76  5012.1  154.76    5590  154.16    5600  153.47
    5610  153.91    5660  163.58    5690  171.21    5730  179.06    5770  183.81
    5790  185.04    5810  187.47    5870  190.12    5890  191.99  5992.4  194.68
#Mann= 3 , 1 , 0
 3634.70    0.15       0  4987.9    0.05       0  5012.1    0.15       0
Bank Sta=4987.90,5012.10
Exp/Cntr=0.3,0.1

Type RM Length L Ch R = 1 ,58020.8,500.6,500.6,500.6
BEGIN DESCRIPTION:
Rocky Swamp 115.0
END DESCRIPTION:
#Sta/Elev= 30
  3288.1  182.59  3478.1  176.82  3528.1  176.12  3588.1   173.6  3668.1  172.72
  3738.1  169.09  3768.1  168.75  3828.1  166.01  4018.1  163.75  4048.1  164.64
  4268.1  164.41  4438.1  161.24  4468.1  162.56  4548.1  158.17  4858.1  153.27
  4878.1  154.07  4987.9  154.09  4989.4  151.09  5010.6  151.09  5012.1  154.09
    5460   154.1    5530  156.32    5580  159.64    5600     162    5640  169.08
    5670  170.84    5710  171.04    5810   179.1    5920  197.04  5940.7  198.28
#Mann= 3 , 1 , 0
 3288.10    0.15       0  4987.9    0.05       0  5012.1    0.15       0
Bank Sta=4987.90,5012.10
Exp/Cntr=0.3,0.1

Type RM Length L Ch R = 1 ,57520.2,500.8,500.8,500.8
BEGIN DESCRIPTION:
Rocky Swamp 114.0
END DESCRIPTION:
#Sta/Elev= 30
  3889.5  182.67  3909.5  182.22  4009.5  176.19  4069.5   174.5  4149.5  170.26
  4269.5  167.52  4359.5  166.61  4469.5  168.42  4539.5  168.67  4659.5  167.18
  4759.5  160.67  4769.5  160.33  4829.5  154.12  4987.9   153.9  4989.4   150.9
  5010.6   150.9  5012.1   153.9    5200  153.83    5210  156.57    5220  158.17
    5230  161.22    5240  164.82    5250  167.46    5260  171.05    5310  184.52
    5320  187.95    5370  195.53    5400  198.21    5460  200.21    5485  199.92
#Mann= 3 , 1 , 0
 3889.50    0.15       0  4987.9    0.05       0  5012.1    0.15       0
Bank Sta=4987.90,5012.10
Exp/Cntr=0.3,0.1

Type RM Length L Ch R = 1 ,57019.4,455.7,455.7,455.7
BEGIN DESCRIPTION:
Rocky Swamp 113.0
END DESCRIPTION:
#Sta/Elev= 30
  4039.8   182.2  4059.8  182.19  4169.8  174.61  4199.8  171.98  4289.8  166.87
  4369.8  165.01  4379.8     164  4439.8  163.85  4449.8  163.14  4499.8  162.77
  4519.8   163.2  4599.8  159.65  4609.8  159.64  4629.8  160.64  4819.8  155.03
  4839.8  153.86  4987.9   153.7  4989.4   150.7  5010.6   150.7  5012.1   153.7
    5120  153.77    5180  165.23    5190  166.63    5220  169.59    5270  172.52
    5350  175.16    5400  178.51    5440  180.28    5450  181.38  5502.1  184.07
#Mann= 3 , 1 , 0
 4039.80    0.15       0  4987.9    0.05       0  5012.1    0.15       0
Bank Sta=4987.90,5012.10
Exp/Cntr=0.3,0.1

Type RM Length L Ch R = 1 ,56563.7,546.1,546.1,546.1
BEGIN DESCRIPTION:
Rocky Swamp 112.0
END DESCRIPTION:
#Sta/Elev= 21
  4695.3  172.17  4755.3  171.64  4885.3  165.45  4925.3  156.14  4985.3  152.58
  4987.9  151.02  4989.4  148.02  5010.6  148.02  5012.1  151.02  5053.5   151.7
  5073.5  150.77  5093.5  150.42  5103.5   149.7  5123.5  150.46  5153.5  150.61
  5173.5  152.68  5223.5  161.71  5263.5  170.85  5273.5  172.69  5443.5  181.84
  5447.5  182.23
#Mann= 3 , 1 , 0
 4695.30    0.15       0  4987.9    0.05       0  5012.1    0.15       0
Bank Sta=4987.90,5012.10
Exp/Cntr=0.3,0.1

Type RM Length L Ch R = 1 ,56017.6,501.5,501.5,501.5
BEGIN DESCRIPTION:
Rocky Swamp 111.0
END DESCRIPTION:
#Sta/Elev= 27
  4671.8  171.27  4691.8  170.37  4721.8  170.28  4731.8  168.86  4781.8  166.26
  4791.8  166.12  4861.8  160.66  4871.8  160.24  4987.9  146.41  4989.4  143.41
  5010.6  143.41  5012.1  146.41    5020  147.21    5030  148.54    5050  149.28
    5060  148.92    5080  149.63    5120  155.65    5140  157.73    5220   166.7
    5240  167.59    5280  172.46    5360     179    5430  181.24    5440  182.05
    5450  182.19  5455.9  182.69
#Mann= 3 , 1 , 0
 4671.80    0.15       0  4987.9    0.05       0  5012.1    0.15       0
Bank Sta=4987.90,5012.10
Exp/Cntr=0.3,0.1

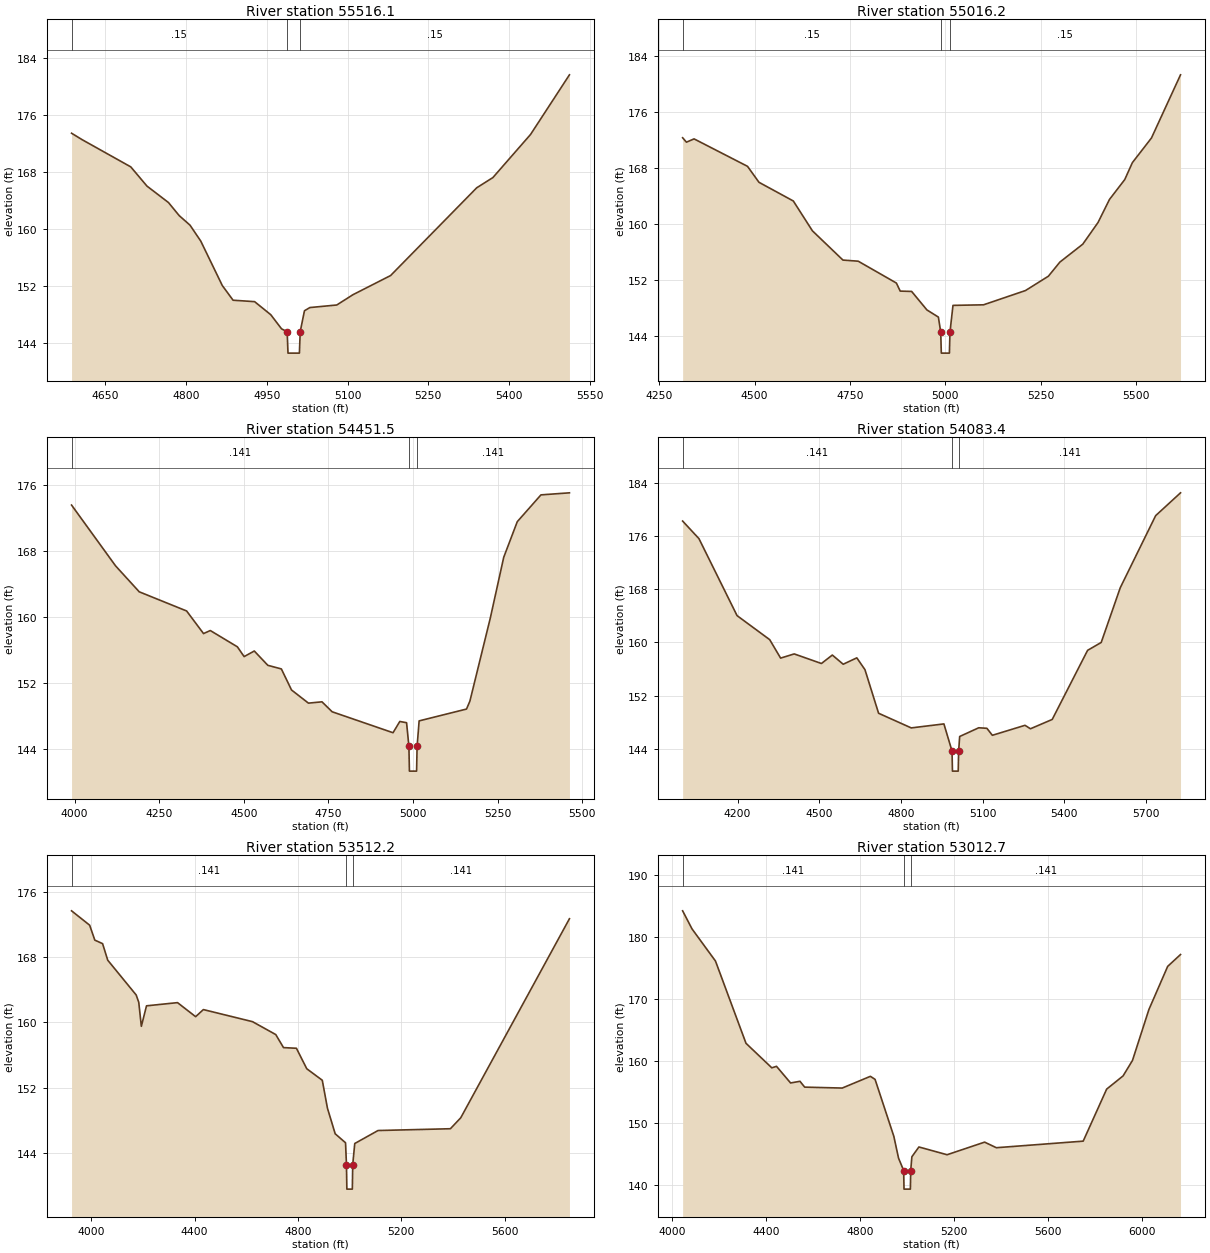
Type RM Length L Ch R = 1 ,55516.1,499.9,499.9,499.9
BEGIN DESCRIPTION:
Rocky Swamp 110.0
END DESCRIPTION:
#Sta/Elev= 26
  4587.4  173.43  4607.4  172.51  4697.4  168.71  4727.4  166.02  4767.4  163.71
  4787.4  161.87  4807.4  160.54  4827.4   158.3  4867.4  152.07  4887.4  150.01
  4927.4  149.81  4957.4  147.98  4977.4     146  4987.9  145.59  4989.4  142.59
  5010.6  142.59  5012.1  145.59    5020  148.53    5030  148.98    5080  149.34
    5110  150.78    5180  153.47    5340  165.78    5370  167.21    5440  173.26
  5512.2  181.62
#Mann= 3 , 1 , 0
 4587.40    0.15       0  4987.9    0.05       0  5012.1    0.15       0
Bank Sta=4987.90,5012.10
Exp/Cntr=0.3,0.1

Type RM Length L Ch R = 1 ,55016.2,564.7,564.7,564.7
BEGIN DESCRIPTION:
Rocky Swamp 109.0
END DESCRIPTION:
#Sta/Elev= 30
  4311.7  172.29  4321.7  171.66  4341.7  172.13  4481.7  168.21  4511.7  165.93
  4601.7  163.26  4651.7     159  4731.7  154.82  4771.7  154.66  4871.7  151.54
  4881.7  150.39  4911.7  150.34  4951.7   147.7  4981.7  146.68  4987.9  144.53
  4989.4  141.53  5010.6  141.53  5012.1  144.53    5020  148.35    5100  148.43
    5210  150.47    5270  152.52    5300  154.53    5360  157.09    5400  160.19
    5430  163.48    5470  166.32    5490  168.74    5540  172.26  5616.1  181.28
#Mann= 3 , 1 , 0
 4311.70    0.15       0  4987.9    0.05       0  5012.1    0.15       0
Bank Sta=4987.90,5012.10
Exp/Cntr=0.3,0.1

Type RM Length L Ch R = 1 ,54451.5,368.1,368.1,368.1
BEGIN DESCRIPTION:
Rocky Swamp 108.0
END DESCRIPTION:
#Sta/Elev= 30
    3991  173.61    4121  166.22    4191  163.06    4331  160.73    4381  157.98
    4401  158.35    4481  156.37    4501  155.18    4531  155.86    4571  154.12
    4611  153.68    4641  151.12    4691  149.52    4731  149.68    4761  148.47
    4941  145.92    4961  147.29    4981  147.14  4987.9  144.25  4989.4  141.25
  5010.6  141.25  5012.1  144.25  5018.1  147.36  5158.1   148.8  5168.1  149.76
  5228.1  159.81  5268.1  167.26  5308.1  171.59  5378.1  174.85  5462.3   175.1
#Mann= 3 , 1 , 0
 3991.00   0.141       0  4987.9    0.05       0  5012.1   0.141       0
Bank Sta=4987.90,5012.10
Exp/Cntr=0.3,0.1

Type RM Length L Ch R = 1 ,54083.4,571.2,571.2,571.2
BEGIN DESCRIPTION:
Rocky Swamp 107.0
END DESCRIPTION:
#Sta/Elev= 30
    3998  178.22    4058  175.58    4198  164.02    4318  160.41    4358  157.64
    4408  158.27    4508  156.83    4548   158.1    4588  156.72    4638  157.68
    4668   155.9    4718  149.36    4838  147.16    4958  147.76  4987.9  143.67
  4989.4  140.67  5010.6  140.67  5012.1  143.67    5016  145.87    5086  147.18
    5116   147.1    5136  146.05    5256  147.55    5276  147.03    5356  148.43
    5486  158.81    5536  159.99    5606  168.21    5736  179.03  5827.4  182.46
#Mann= 3 , 1 , 0
 3998.00   0.141       0  4987.9    0.05       0  5012.1   0.141       0
Bank Sta=4987.90,5012.10
Exp/Cntr=0.3,0.1

Type RM Length L Ch R = 1 ,53512.2,499.5,499.5,499.5
BEGIN DESCRIPTION:
Rocky Swamp 106.0
END DESCRIPTION:
#Sta/Elev= 30
  3924.3  173.66  3994.3   171.9  4014.3  170.07  4044.3  169.64  4064.3  167.61
  4174.3  163.35  4184.3  162.45  4194.3  159.51  4214.3  162.02  4334.3  162.41
  4404.3  160.69  4434.3  161.56  4624.3  160.08  4714.3   158.5  4744.3   156.9
  4794.3  156.82  4834.3  154.31  4894.3   152.9  4914.3  149.48  4944.3  146.34
  4984.3  145.24  4987.9  142.56  4989.4  139.56  5010.6  139.56  5012.1  142.56
    5020  145.15    5110  146.74    5390  146.96    5430   148.3  5850.6  172.69
#Mann= 3 , 1 , 0
 3924.30   0.141       0  4987.9    0.05       0  5012.1   0.141       0
Bank Sta=4987.90,5012.10
Exp/Cntr=0.3,0.1

Type RM Length L Ch R = 1 ,53012.7,499.9,499.9,499.9
BEGIN DESCRIPTION:
Rocky Swamp 105.0
END DESCRIPTION:
#Sta/Elev= 30
  4043.2  184.16  4083.2  181.25  4183.2  176.07  4313.2  162.82  4423.2  158.87
  4443.2  159.11  4503.2  156.43  4543.2   156.7  4563.2  155.76  4723.2  155.61
  4843.2   157.5  4863.2  157.01  4943.2  147.83  4963.2  144.32    4985  142.33
  4986.5  139.33  5013.6  139.33  5015.1  142.33    5020  144.54    5050  146.12
    5170  144.87    5330   146.9    5380     146    5750  147.06    5850  155.44
    5920  157.57    5960  160.06    6030  168.26    6110  175.21  6164.7  177.12
#Mann= 3 , 1 , 0
 4043.20   0.141       0    4985    0.05       0  5015.1   0.141       0
Bank Sta=4985.00,5015.10
Exp/Cntr=0.3,0.1

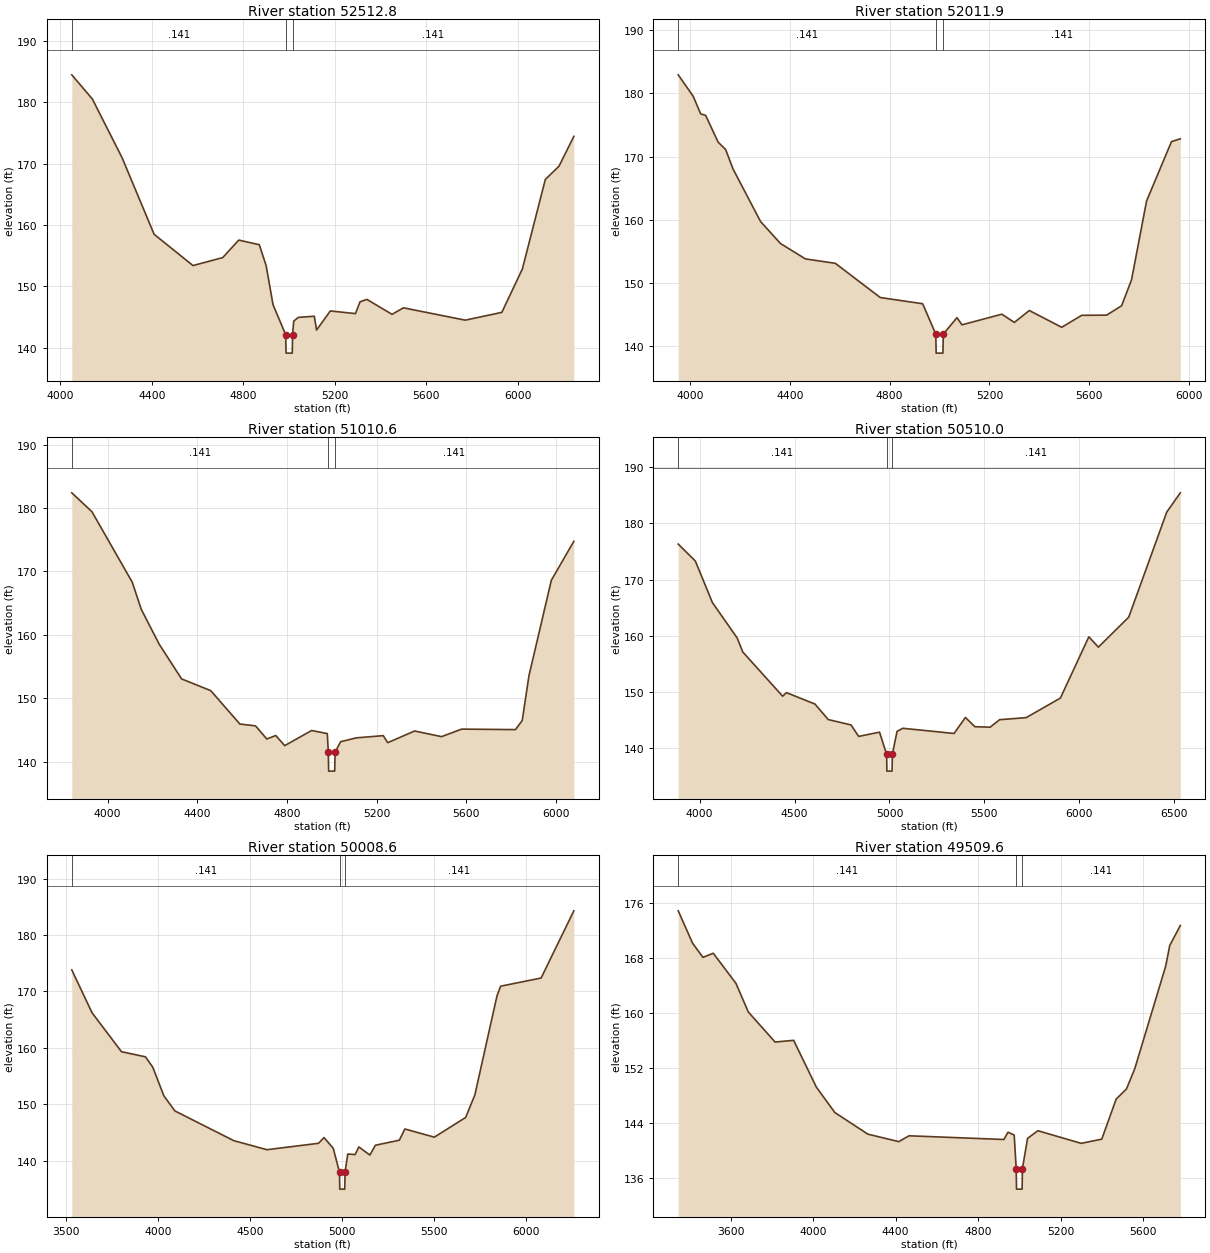
Type RM Length L Ch R = 1 ,52512.8,500.9,500.9,500.9
BEGIN DESCRIPTION:
Rocky Swamp 104.0
END DESCRIPTION:
#Sta/Elev= 30
  4049.6  184.47  4139.6  180.53  4269.6  170.97  4409.6   158.5  4579.6   153.4
  4709.6   154.7  4779.6  157.55  4869.6   156.8  4899.6  153.37  4929.6  147.02
    4985  142.14  4986.5  139.14  5013.6  139.14  5015.1  142.14    5020  144.35
    5040  144.96    5110  145.15    5120   142.9    5180  146.01    5290  145.58
    5310   147.5    5340  147.89    5450  145.46    5500  146.52    5770  144.51
    5930  145.78    6020  152.87    6120  167.42    6180  169.59  6244.8  174.45
#Mann= 3 , 1 , 0
 4049.60   0.141       0    4985    0.05       0  5015.1   0.141       0
Bank Sta=4985.00,5015.10
Exp/Cntr=0.3,0.1

Type RM Length L Ch R = 1 ,52011.9,1001.3,1001.3,1001.3
BEGIN DESCRIPTION:
Rocky Swamp 103.0
END DESCRIPTION:
#Sta/Elev= 30
  3952.4   182.9  4012.4  179.51  4042.4  176.74  4062.4  176.49  4112.4  172.27
  4142.4  171.11  4172.4  168.01  4282.4  159.74  4362.4  156.26  4462.4  153.83
  4582.4  153.13  4762.4  147.73  4932.4  146.75    4985  141.95  4986.5  138.95
  5013.6  138.95  5015.1  141.95    5070  144.55    5090  143.42    5250   145.1
    5300   143.8    5360  145.68    5490  143.03    5570  144.92    5670  144.95
    5730  146.43    5770  150.55    5830  162.96    5930  172.35  5965.4   172.8
#Mann= 3 , 1 , 0
 3952.40   0.141       0    4985    0.05       0  5015.1   0.141       0
Bank Sta=4985.00,5015.10
Exp/Cntr=0.3,0.1

Type RM Length L Ch R = 1 ,51010.6,500.6,500.6,500.6
BEGIN DESCRIPTION:
Rocky Swamp 102.0
END DESCRIPTION:
#Sta/Elev= 30
  3840.4  182.41  3930.4  179.43  4110.4   168.3  4150.4  164.03  4230.4  158.53
  4330.4  153.05  4460.4   151.2  4590.4  145.93  4660.4  145.64  4710.4  143.57
  4750.4  144.12  4790.4  142.52  4910.4  144.91  4980.4  144.42  4984.9   141.5
  4986.4   138.5  5013.5   138.5    5015   141.5    5040  143.14    5110  143.75
    5230   144.1    5250  142.99    5370  144.83    5490  143.94    5580  145.13
    5820  145.05    5850  146.49    5880  153.54    5980  168.62  6080.3  174.76
#Mann= 3 , 1 , 0
 3840.40   0.141       0  4984.9    0.05       0    5015   0.141       0
Bank Sta=4984.90,5015.00
Exp/Cntr=0.3,0.1

Type RM Length L Ch R = 1 ,50510.0,501.4,501.4,501.4
BEGIN DESCRIPTION:
Rocky Swamp 101.0
END DESCRIPTION:
#Sta/Elev= 30
  3887.6  176.32  3977.6  173.31  4067.6   165.9  4197.6  159.62  4227.6   157.1
  4437.6  149.22  4457.6  149.86  4607.6  147.83  4677.6  145.06  4797.6  144.11
  4837.6  142.06  4947.6  142.82  4984.9  138.88  4986.4  135.88  5013.6  135.88
  5015.1  138.88    5040  142.97    5070  143.51    5340  142.59    5400  145.44
    5450  143.79    5530  143.71    5580  145.04    5720  145.41    5900  148.89
    6050  159.81    6100  157.96    6260  163.31    6460  182.01  6531.5  185.45
#Mann= 3 , 1 , 0
 3887.60   0.141       0  4984.9    0.05       0  5015.1   0.141       0
Bank Sta=4984.90,5015.10
Exp/Cntr=0.3,0.1

Type RM Length L Ch R = 1 ,50008.6,499,499,499
BEGIN DESCRIPTION:
Rocky Swamp 100.0
END DESCRIPTION:
#Sta/Elev= 30
    3531  173.82    3641  166.23    3801  159.32    3931  158.41    3971  156.57
    4031  151.51    4091  148.82    4411  143.55    4591  141.95    4871  143.08
    4901   144.1    4951   142.2    4985  137.96  4986.5  134.96  5013.6  134.96
  5015.1  137.96    5030  141.18    5070  141.09    5090  142.44    5150     141
    5180  142.74    5310  143.63    5340  145.62    5500  144.17    5670  147.66
    5720  151.64    5840  169.17    5860  170.93    6080  172.38  6257.7  184.29
#Mann= 3 , 1 , 0
 3531.00   0.141       0    4985    0.05       0  5015.1   0.141       0
Bank Sta=4985.00,5015.10
Exp/Cntr=0.3,0.1

Type RM Length L Ch R = 1 ,49509.6,498.3,498.3,498.3
BEGIN DESCRIPTION:
Rocky Swamp 99.0
END DESCRIPTION:
#Sta/Elev= 30
  3345.1  174.84  3415.1  170.11  3465.1  168.07  3515.1  168.67  3625.1  164.29
  3685.1  160.12  3815.1  155.75  3905.1     156  4015.1   149.2  4105.1  145.49
  4265.1  142.35  4415.1  141.26  4465.1  142.11  4925.1  141.57  4945.1  142.63
  4975.1  142.22  4984.9  137.35  4986.4  134.35  5013.6  134.35  5015.1  137.35
    5040  141.73    5090  142.85    5300  141.01    5400  141.62    5470  147.45
    5520  148.93    5560  151.86    5710  166.77    5730  169.81  5781.1   172.7
#Mann= 3 , 1 , 0
 3345.10   0.141       0  4984.9    0.05       0  5015.1   0.141       0
Bank Sta=4984.90,5015.10
Exp/Cntr=0.3,0.1

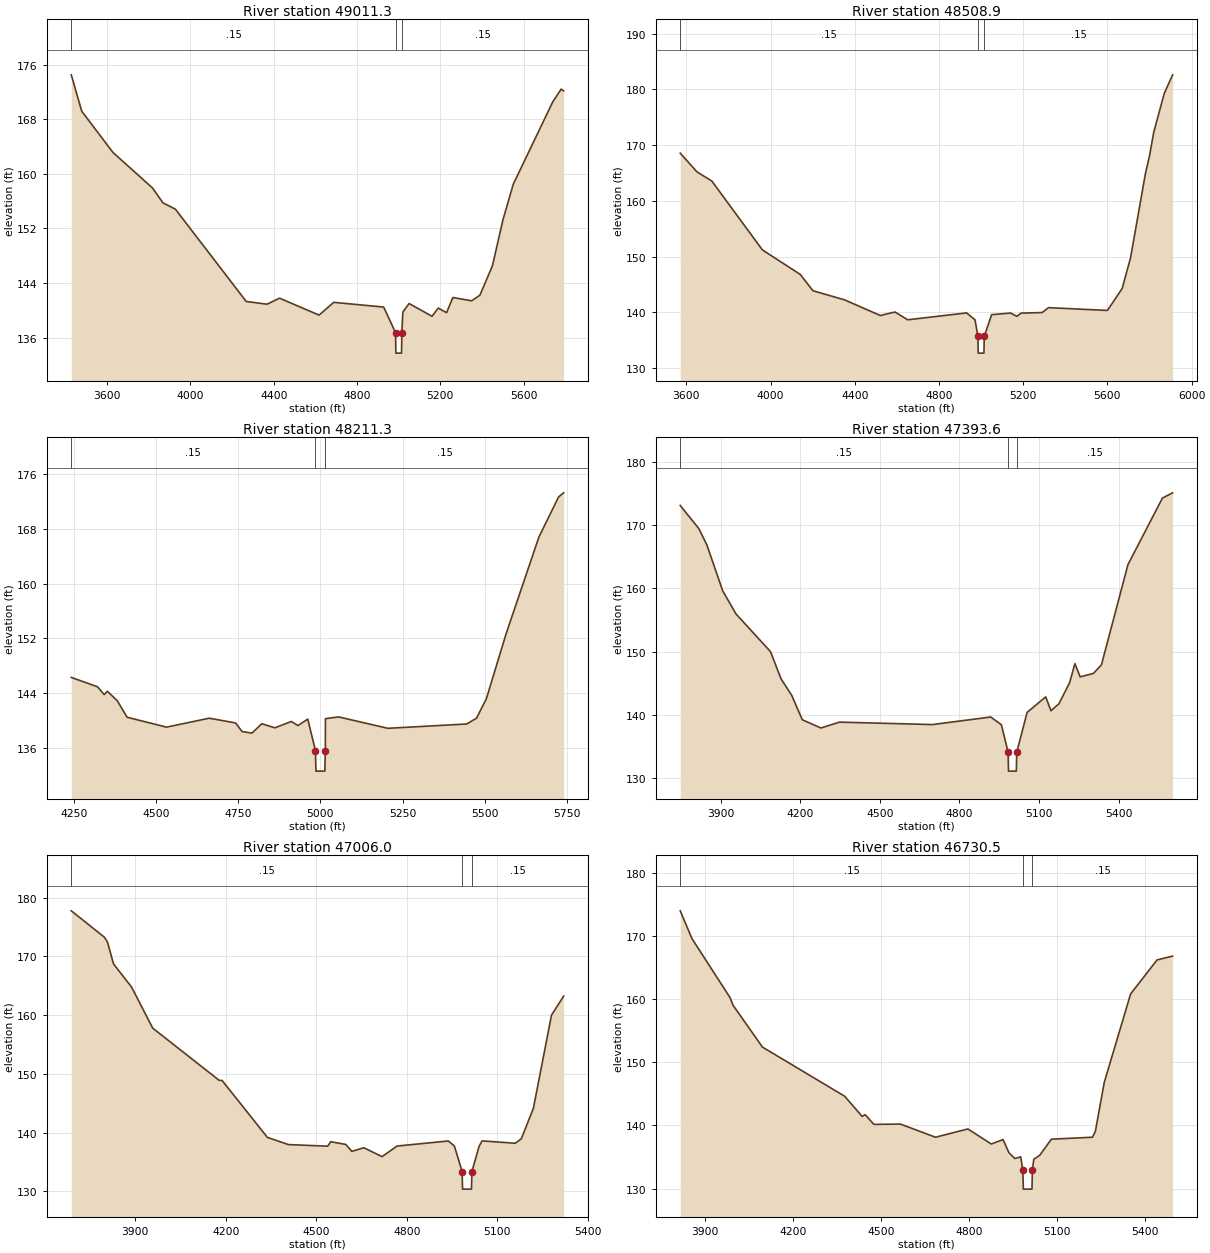
Type RM Length L Ch R = 1 ,49011.3,502.4,502.4,502.4
BEGIN DESCRIPTION:
Rocky Swamp 98.0
END DESCRIPTION:
#Sta/Elev= 30
  3427.8  174.51  3477.8  169.19  3627.8  163.14  3817.8  157.93  3867.8  155.76
  3927.8  154.82  4267.8   141.3  4367.8   140.9  4427.8  141.78  4617.8   139.3
  4687.8  141.17  4927.8  140.48  4984.9  136.73  4986.4  133.73  5013.6  133.73
  5015.1  136.73    5020  139.75    5050     141    5160  139.13    5190  140.33
    5230  139.66    5260  141.88    5350   141.4    5390  142.22    5450  146.51
    5500  153.19    5550  158.47    5740  170.56    5780  172.41  5792.1  172.16
#Mann= 3 , 1 , 0
 3427.80    0.15       0  4984.9   0.055       0  5015.1    0.15       0
Bank Sta=4984.90,5015.10
Exp/Cntr=0.3,0.1

Type RM Length L Ch R = 1 ,48508.9,297.6,297.6,297.6
BEGIN DESCRIPTION:
Rocky Swamp 97.0
END DESCRIPTION:
#Sta/Elev= 30
  3571.3  168.55  3651.3  165.18  3721.3  163.55  3961.3   151.2  4141.3  146.79
  4201.3  143.87  4351.3  142.23  4521.3  139.42  4591.3  140.05  4651.3  138.65
  4931.3  139.89  4971.3  138.64  4984.9  135.67  4986.4  132.67  5013.5  132.67
    5015  135.67    5050  139.57    5140  139.86    5170  139.27    5190  139.85
    5290  139.95    5320  140.83    5600  140.33    5670  144.27    5710   149.8
    5780   164.8    5800   168.1    5820  172.31    5870  179.28  5909.6  182.61
#Mann= 3 , 1 , 0
 3571.30    0.15       0  4984.9   0.055       0    5015    0.15       0
Bank Sta=4984.90,5015.00
Exp/Cntr=0.3,0.1

Type RM Length L Ch R = 1 ,48211.3,817.7,817.7,817.7
BEGIN DESCRIPTION:
Rocky Swamp 96.0
END DESCRIPTION:
#Sta/Elev= 30
  4241.5  146.27  4321.5   144.9  4341.5  143.76  4351.5  144.24  4381.5  142.86
  4411.5  140.44  4531.5  138.99  4661.5   140.3  4741.5  139.61  4761.5  138.35
  4791.5  138.11  4821.5  139.49  4861.5  138.89  4911.5  139.82  4931.5  139.22
  4961.5  140.17  4984.9  135.55  4986.4  132.55  5013.5  132.55    5015  135.55
  5015.3  140.23  5055.3  140.49  5205.3  138.82  5445.3  139.45  5475.3   140.3
  5505.3  143.15  5565.3  152.65  5665.3  166.83  5725.3  172.71  5740.6   173.3
#Mann= 3 , 1 , 0
 4241.50    0.15       0  4984.9   0.055       0    5015    0.15       0
Bank Sta=4984.90,5015.00
Exp/Cntr=0.3,0.1

Type RM Length L Ch R = 1 ,47393.6,387.6,387.6,387.6
BEGIN DESCRIPTION:
Rocky Swamp 95.0
END DESCRIPTION:
#Sta/Elev= 30
  3748.3  173.15  3818.3  169.49  3848.3  166.94  3908.3  159.62  3958.3  155.96
  4088.3  149.99  4128.3  145.66  4168.3  143.06  4208.3  139.18  4278.3  137.88
  4348.3  138.81  4698.3  138.42  4918.3  139.62  4958.3   138.4  4983.8  134.04
  4985.3  131.04  5014.8  131.04  5016.3  134.04  5055.4  140.35  5125.4  142.81
  5145.4  140.61  5175.4  141.73  5215.4  145.04  5235.4  148.08  5255.4  145.98
  5305.4  146.53  5335.4  147.88  5435.4  163.78  5565.4  174.33  5603.7  175.16
#Mann= 3 , 1 , 0
 3748.30    0.15       0  4983.8   0.055       0  5016.3    0.15       0
Bank Sta=4983.80,5016.30
Exp/Cntr=0.3,0.1

Type RM Length L Ch R = 1 ,47006.0,275.5,275.5,275.5
BEGIN DESCRIPTION:
Rocky Swamp 94.0
END DESCRIPTION:
#Sta/Elev= 30
  3688.1  177.76  3798.1  173.26  3808.1  172.45  3828.1  168.73  3888.1  164.77
  3958.1  157.79  4178.1  148.92  4188.1  148.88  4338.1   139.2  4408.1  137.97
  4538.1   137.7  4548.1  138.46  4598.1     138  4618.1  136.82  4658.1  137.43
  4718.1  135.92  4768.1  137.72  4938.1  138.59  4958.1  137.73  4983.7  133.39
  4985.2  130.39  5014.7  130.39  5016.2  133.39    5040  137.68    5050   138.6
    5160   138.2    5180  138.96    5220  144.15    5280     160  5320.3  163.24
#Mann= 3 , 1 , 0
 3688.10    0.15       0  4983.7   0.055       0  5016.2    0.15       0
Bank Sta=4983.70,5016.20
Exp/Cntr=0.3,0.1

Type RM Length L Ch R = 1 ,46730.5,722.6,722.6,722.6
BEGIN DESCRIPTION:
Rocky Swamp 93.0
END DESCRIPTION:
#Sta/Elev= 30
  3816.2  173.95  3856.2  169.55  3986.2   160.2  3996.2  159.01  4096.2   152.4
  4376.2  144.63  4436.2  141.43  4446.2  141.71  4476.2  140.17  4566.2  140.22
  4686.2  138.14  4796.2  139.45  4876.2  137.07  4916.2  137.77  4936.2  135.69
  4956.2  134.77  4976.2  135.04  4983.7  132.93  4985.2  129.93  5014.7  129.93
  5016.2  132.93  5020.9  134.65  5040.9  135.27  5080.9  137.83  5220.9  138.14
  5230.9   139.1  5260.9  146.78  5350.9  160.81  5440.9  166.18    5494  166.79
#Mann= 3 , 1 , 0
 3816.20    0.15       0  4983.7   0.055       0  5016.2    0.15       0
Bank Sta=4983.70,5016.20
Exp/Cntr=0.3,0.1

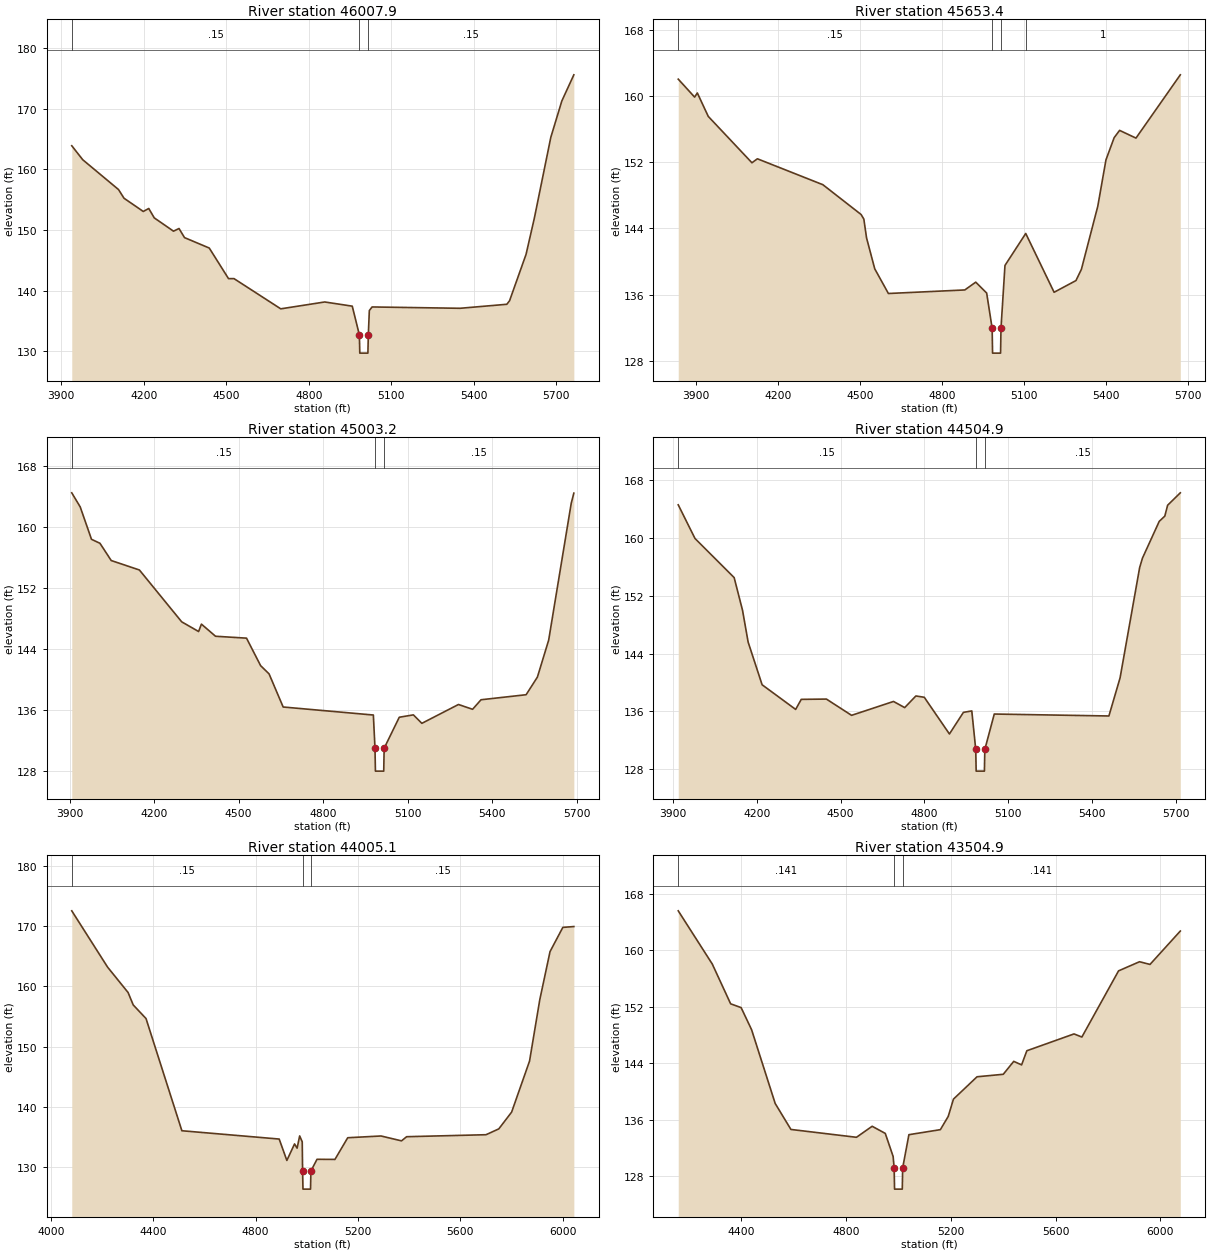
Type RM Length L Ch R = 1 ,46007.9,354.5,354.5,354.5
BEGIN DESCRIPTION:
Rocky Swamp 92.0
END DESCRIPTION:
#Sta/Elev= 30
  3937.9   163.9  3977.9  161.59  4107.9  156.68  4127.9  155.25  4197.9  153.07
  4217.9  153.56  4237.9  152.01  4307.9  149.82  4327.9  150.26  4347.9  148.76
  4437.9  147.04  4507.9     142  4527.9     142  4697.9  137.02  4857.9  138.15
  4957.9  137.46  4983.8  132.72  4985.3  129.72  5014.8  129.72  5016.3  132.72
    5020  136.73    5030  137.33    5350  137.11    5520  137.77    5530  138.36
    5590  146.01    5620  151.95    5680   165.3    5720  171.28  5763.7  175.59
#Mann= 3 , 1 , 0
 3937.90    0.15       0  4983.8   0.055       0  5016.3    0.15       0
Bank Sta=4983.80,5016.30
Exp/Cntr=0.3,0.1

Type RM Length L Ch R = 1 ,45653.4,650.2,650.2,650.2
BEGIN DESCRIPTION:
Rocky Swamp 91.0
END DESCRIPTION:
#Sta/Elev= 30
  3833.7  162.02  3893.7  159.85  3903.7  160.35  3943.7  157.52  4103.7  151.92
  4123.7   152.4  4363.7  149.27  4503.7  145.67  4513.7  145.12  4523.7  142.84
  4553.7  139.11  4603.7  136.13  4883.7  136.56  4923.7   137.5  4963.7  136.19
  4983.8  131.93  4985.3  128.93  5014.7  128.93  5016.2  131.93  5030.8  139.52
  5106.9  143.38  5210.8  136.28  5290.8  137.69  5310.8  139.05  5370.8  146.66
  5400.8  152.27  5430.8  154.95  5450.8  155.83  5510.8   154.9  5673.2  162.54
#Mann= 4 , 1 , 0
 3833.70    0.15       0  4983.8   0.055       0  5016.2    0.15       0
  5106.9       1       0
Bank Sta=4983.80,5016.20
Exp/Cntr=0.3,0.1

Type RM Length L Ch R = 1 ,45003.2,498.3,498.3,498.3
BEGIN DESCRIPTION:
Rocky Swamp 90.0
END DESCRIPTION:
#Sta/Elev= 30
    3908  164.48    3938  162.63    3978  158.39    4008  157.87    4048  155.61
    4148  154.37    4298  147.58    4358  146.31    4368  147.28    4418  145.69
    4528  145.44    4578  141.84    4608  140.76    4658  136.42    4978  135.37
  4983.8  131.02  4985.3  128.02  5014.8  128.02  5016.3  131.02    5070  135.08
    5120  135.39    5150  134.28    5280  136.75    5330  136.12    5360  137.37
    5520  138.03    5560  140.34    5600  145.18    5680   163.1  5689.3  164.44
#Mann= 3 , 1 , 0
 3908.00    0.15       0  4983.8   0.055       0  5016.3    0.15       0
Bank Sta=4983.80,5016.30
Exp/Cntr=0.3,0.1

Type RM Length L Ch R = 1 ,44504.9,499.8,499.8,499.8
BEGIN DESCRIPTION:
Rocky Swamp 89.0
END DESCRIPTION:
#Sta/Elev= 30
  3919.6  164.58  3979.6  159.92  4119.6  154.51  4149.6  149.98  4169.6  145.59
  4219.6  139.68  4339.6  136.27  4359.6  137.66  4449.6   137.7  4539.6  135.45
  4689.6  137.37  4729.6  136.52  4769.6  138.13  4799.6  137.95  4889.6  132.87
  4939.6  135.86  4969.6  136.06  4983.7  130.73  4985.2  127.73  5014.7  127.73
  5016.2  130.73    5050  135.63    5460  135.36    5500  140.64    5570   155.9
    5580   157.2    5640  162.29    5660  163.02    5670  164.52  5715.4  166.24
#Mann= 3 , 1 , 0
 3919.60    0.15       0  4983.7   0.055       0  5016.2    0.15       0
Bank Sta=4983.70,5016.20
Exp/Cntr=0.3,0.1

Type RM Length L Ch R = 1 ,44005.1,500.2,500.2,500.2
BEGIN DESCRIPTION:
Rocky Swamp 88.0
END DESCRIPTION:
#Sta/Elev= 30
  4082.3  172.55  4222.3   163.2  4302.3  158.99  4322.3  156.93  4372.3  154.67
  4512.3  136.05  4892.3  134.67  4922.3  131.12  4952.3  133.86  4962.3  133.16
  4972.3  135.19  4982.3  134.21  4983.7  129.36  4985.2  126.36  5014.7  126.36
  5016.2  129.36    5040  131.31    5110  131.29    5160  134.89    5290  135.18
    5370  134.37    5390  135.06    5700  135.39    5750  136.36    5800  139.14
    5870  147.61    5910   157.8    5950  165.78    6000   169.8    6043  169.94
#Mann= 3 , 1 , 0
 4082.30    0.15       0  4983.7   0.055       0  5016.2    0.15       0
Bank Sta=4983.70,5016.20
Exp/Cntr=0.3,0.1

Type RM Length L Ch R = 1 ,43504.9,501.8,501.8,501.8
BEGIN DESCRIPTION:
Rocky Swamp 87.0
END DESCRIPTION:
#Sta/Elev= 30
  4159.8  165.57  4289.8  158.04  4359.8  152.42  4399.8  151.88  4439.8  148.75
  4529.8  138.32  4589.8  134.65  4839.8  133.54  4899.8   135.1  4949.8  134.09
  4979.8  130.83  4983.7  129.21  4985.2  126.21  5014.7  126.21  5016.2  129.21
    5040  133.91    5160  134.62    5190  136.49    5210  138.94    5300   142.1
    5400  142.45    5440  144.28    5470  143.78    5490  145.78    5670  148.16
    5700  147.72    5840  157.08    5920  158.37    5960  157.99  6075.6  162.71
#Mann= 3 , 1 , 0
 4159.80   0.141       0  4983.7   0.055       0  5016.2   0.141       0
Bank Sta=4983.70,5016.20
Exp/Cntr=0.3,0.1