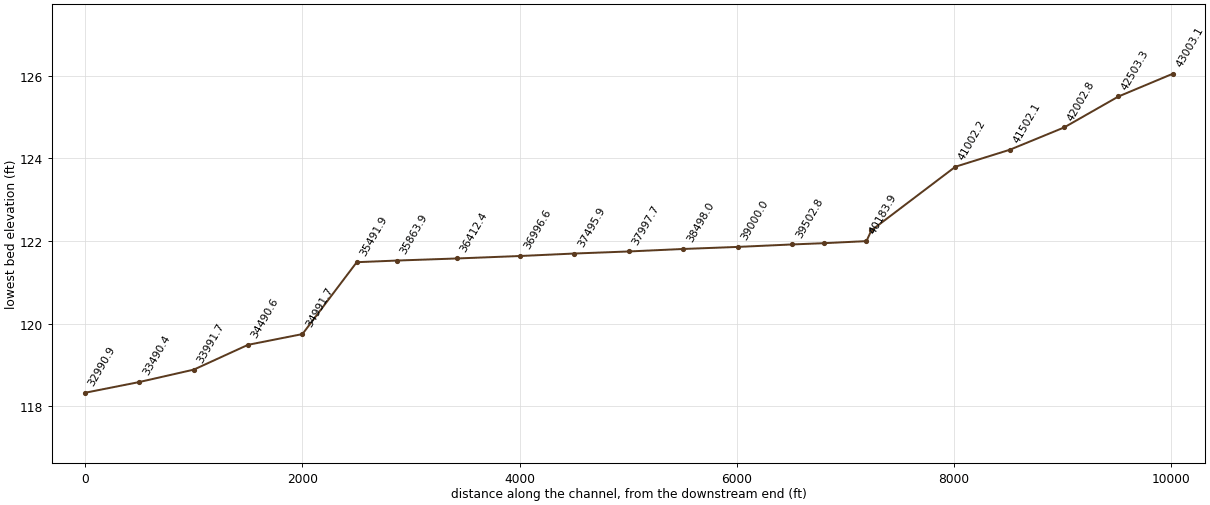
HEC-RAS study 021209_rocky_swamp.prj: Rocky Swamp

--- 021209_rocky_swamp.g01 (geometry) --- (continued)

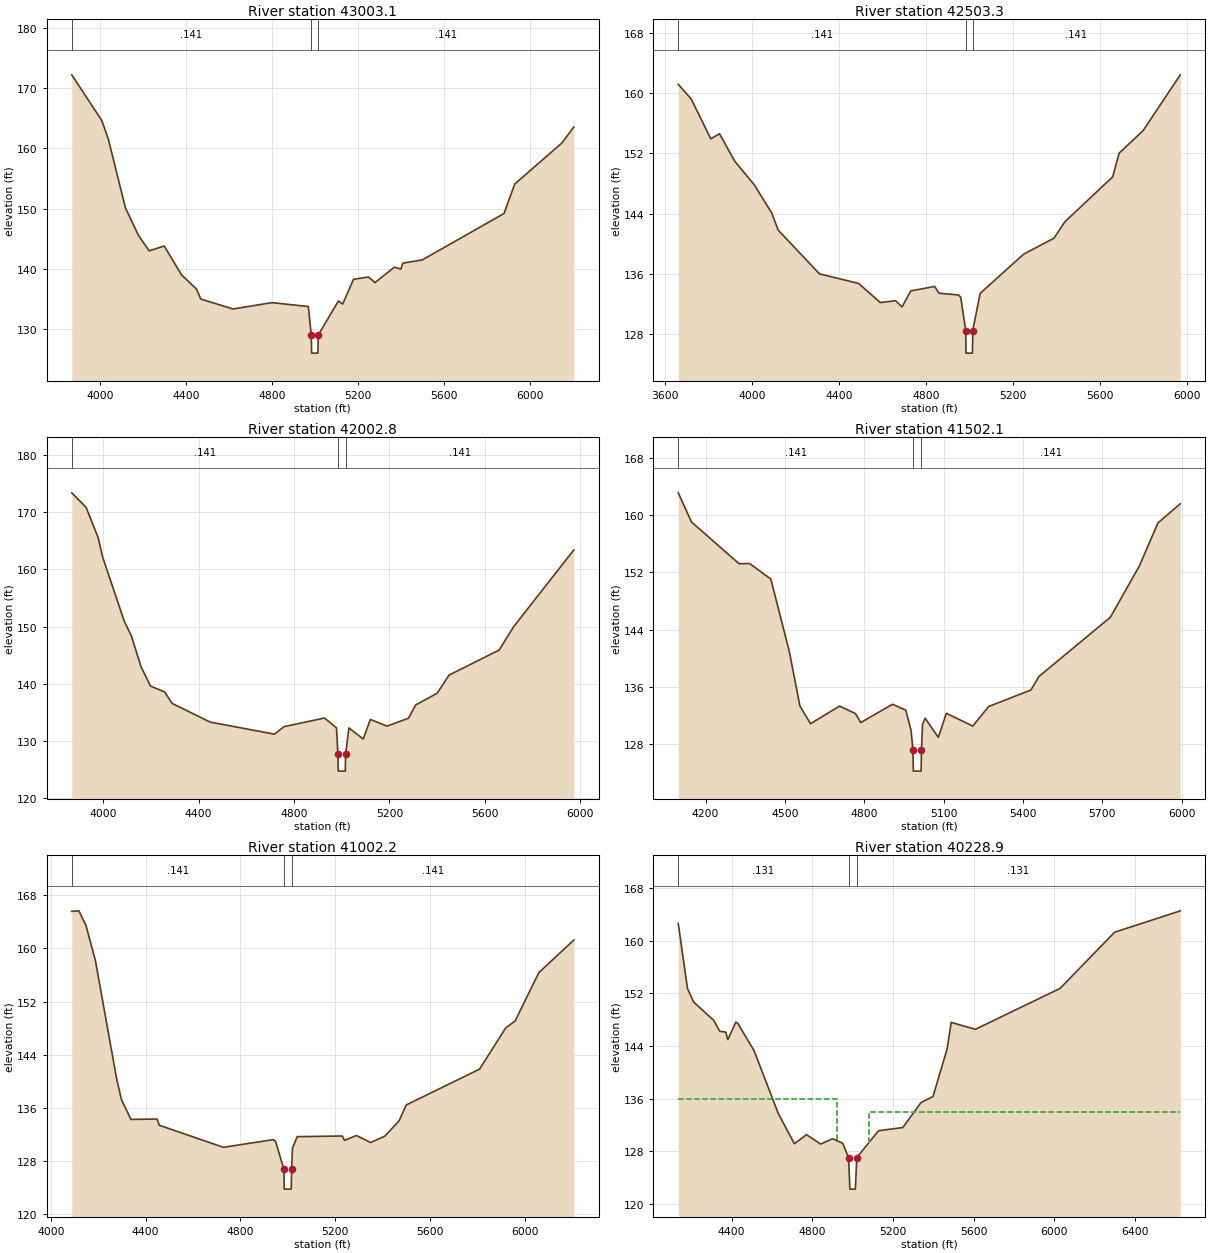
Type RM Length L Ch R = 1 ,43003.1,499.8,499.8,499.8
BEGIN DESCRIPTION:
Rocky Swamp 86.0
END DESCRIPTION:
#Sta/Elev= 30
  3869.9   172.2  4009.9   164.6  4039.9  161.54  4119.9  150.09  4179.9  145.59
  4229.9  143.01  4299.9  143.82  4379.9  139.05  4449.9  136.67  4469.9  135.02
  4619.9  133.37  4799.9  134.42  4969.9  133.78  4983.8  129.05  4985.3  126.05
  5014.7  126.05  5016.2  129.05    5110   134.7    5130  134.19    5180  138.29
    5250  138.67    5280  137.74    5370   140.3    5400  139.99    5410  140.97
    5500  141.51    5880   149.2    5930  154.09    6150  160.92  6204.8  163.56
#Mann= 3 , 1 , 0
 3869.90   0.141       0  4983.8   0.055       0  5016.2   0.141       0
Bank Sta=4983.80,5016.20
Exp/Cntr=0.3,0.1

Type RM Length L Ch R = 1 ,42503.3,500.5,500.5,500.5
BEGIN DESCRIPTION:
Rocky Swamp 85.0
END DESCRIPTION:
#Sta/Elev= 30
    3661  161.19    3721  159.22    3811  153.94    3851  154.62    3921  150.97
    4011  147.84    4091  144.11    4121  141.83    4311  136.02    4491  134.75
    4591  132.21    4661  132.46    4691  131.63    4731  133.76    4841  134.35
    4861  133.45    4951  133.22    4961  132.91  4983.8   128.5  4985.3   125.5
  5014.8   125.5  5016.3   128.5    5050  133.42    5250  138.63    5390  140.76
    5440  142.93    5660   148.9    5690  152.05    5800  155.03  5971.3  162.44
#Mann= 3 , 1 , 0
 3661.00   0.141       0  4983.8   0.055       0  5016.3   0.141       0
Bank Sta=4983.80,5016.30
Exp/Cntr=0.3,0.1

Type RM Length L Ch R = 1 ,42002.8,500.7,500.7,500.7
BEGIN DESCRIPTION:
Rocky Swamp 84.0
END DESCRIPTION:
#Sta/Elev= 30
  3867.9  173.37  3927.9  170.84  3977.9  165.61  3997.9  162.08  4087.9  150.96
  4117.9  148.37  4157.9  143.04  4197.9  139.61  4257.9  138.57  4287.9   136.6
  4447.9  133.32  4717.9  131.21  4757.9  132.52  4927.9  134.03  4977.9   132.3
  4983.8  127.75  4985.3  124.75  5014.7  124.75  5016.2  127.75    5030   132.3
    5090  130.36    5120  133.78    5190  132.61    5280     134    5310  136.31
    5400  138.35    5450  141.53    5660   145.9    5720  149.94  5973.2   163.4
#Mann= 3 , 1 , 0
 3867.90   0.141       0  4983.8   0.055       0  5016.2   0.141       0
Bank Sta=4983.80,5016.20
Exp/Cntr=0.3,0.1

Type RM Length L Ch R = 1 ,41502.1,499.9,499.9,499.9
BEGIN DESCRIPTION:
Rocky Swamp 83.0
END DESCRIPTION:
#Sta/Elev= 30
  4096.8  163.12  4146.8  159.05  4326.8  153.21  4366.8  153.23  4446.8  151.06
  4516.8   140.9  4556.8  133.31  4596.8  130.84  4706.8  133.31  4766.8  132.25
  4786.8     131  4906.8  133.56  4956.8  132.73  4976.8  129.91  4983.8  127.21
  4985.3  124.21  5014.7  124.21  5016.2  127.21    5020  130.73    5030   131.6
    5080  128.93    5110   132.3    5210  130.51    5270  133.24    5430  135.56
    5460  137.44    5730  145.72    5840  152.92    5910  158.92  5994.4  161.59
#Mann= 3 , 1 , 0
 4096.80   0.141       0  4983.8   0.055       0  5016.2   0.141       0
Bank Sta=4983.80,5016.20
Exp/Cntr=0.3,0.1

Type RM Length L Ch R = 1 ,41002.2,773.3,773.3,773.3
BEGIN DESCRIPTION:
Rocky Swamp 82.0
END DESCRIPTION:
#Sta/Elev= 30
  4088.2  165.57  4118.2  165.65  4148.2  163.45  4188.2  158.14  4278.2  140.28
  4298.2  137.25  4338.2  134.28  4448.2  134.34  4458.2   133.4  4728.2  130.09
  4938.2  131.24  4948.2     131  4983.8   126.8  4985.3   123.8  5014.8   123.8
  5016.3   126.8    5020  129.96    5040  131.69    5230  131.79    5240  131.13
    5290  131.87    5350  130.81    5410  131.77    5470  134.06    5500  136.45
    5810  141.85    5920  148.03    5960  149.09    6060  156.35  6207.9  161.26
#Mann= 3 , 1 , 0
 4088.20   0.141       0  4983.8   0.055       0  5016.3   0.141       0
Bank Sta=4983.80,5016.30
Exp/Cntr=0.5,0.3

Type RM Length L Ch R = 1 ,40228.9,45,45,45
BEGIN DESCRIPTION:
Upstream Section of Bridge/Culvert/Weir
END DESCRIPTION:
#Sta/Elev= 30
  4135.3  162.64  4181.2  152.76  4211.2  150.71  4311.2  147.92  4341.2  146.25
  4371.2  146.12  4381.2  144.99  4421.2  147.65  4431.2  147.43  4511.2  143.31
  4631.2  133.77  4711.2  129.16  4771.2  130.54  4841.2  129.11  4901.2  129.92
  4951.2  129.22  4979.5  127.06  4986.5  122.26  5013.5  122.26  5020.5  127.06
  5128.6  131.14  5248.6  131.62  5338.6  135.41  5398.6  136.34  5468.6   143.6
  5488.6   147.6  5608.6  146.55  6028.6  152.77  6298.6   161.3  6624.6  164.56
#Mann= 3 , 1 , 0
 4135.30   0.131       0  4979.5   0.055       0  5020.5   0.131       0
#XS Ineff= 2 , 0
       0    4920     136    5079       0     134
Bank Sta=4979.50,5020.50
Exp/Cntr=0.5,0.3

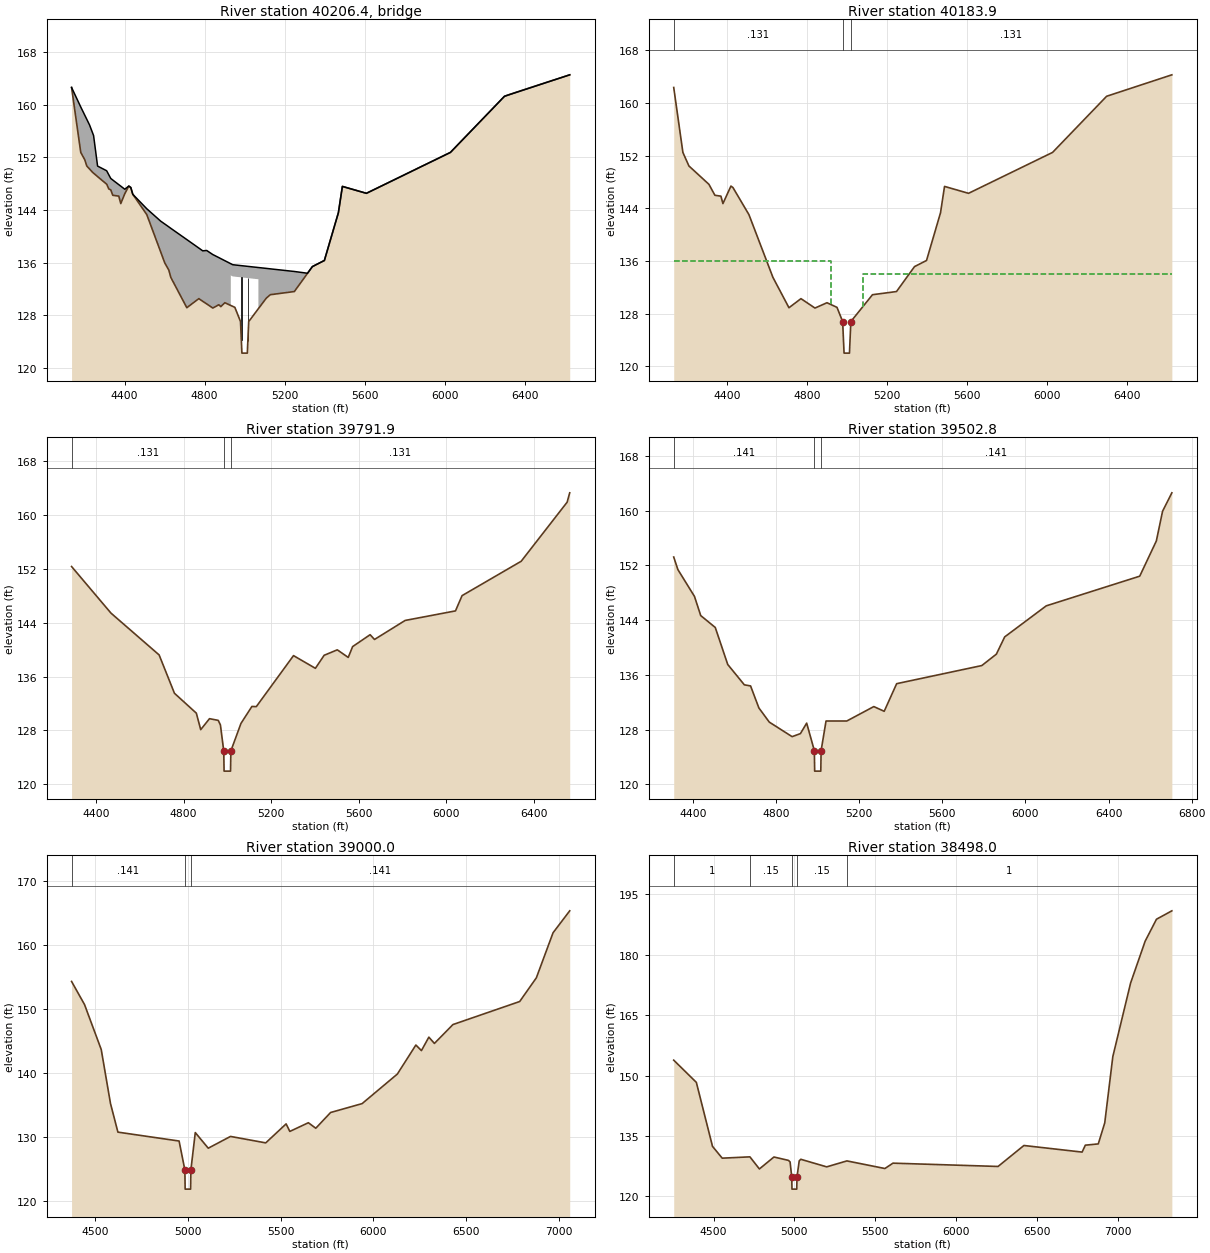
Type RM Length L Ch R = 3 ,40206.4,,,
BEGIN DESCRIPTION:
Ringwood Road-TOR
Structure ID: Ringwood Road
Approximate Survey Structure
END DESCRIPTION:
Bridge Culvert--1,0,-1,-1, 0
Deck Dist Width WeirC Skew NumUp NumDn MinLoCord MaxHiCord MaxSubmerge Is_Ogee
10,25,2.6,, 47, 48,,,0.95,0,1,1,,
  4135.3  4181.2  4201.2  4211.2  4225.3  4245.3  4265.3  4310.6  4321.2  4331.2
  4341.2  4371.2  4381.2  4401.2  4421.2  4431.2  4441.2  4511.2  4580.6  4601.2
  4621.2  4631.2  4711.2  4771.2  4790.6  4810.6  4841.2  4871.2  4881.2  4901.2
 4930.91    4931  4940.6 5068.89    5069  5108.6  5128.6  5248.6  5314.5  5338.6
  5398.6  5468.6  5488.6  5608.6  6028.6  6298.6  6624.6
  162.63  159.66  158.42   157.8  156.92  155.32  150.68  149.97  149.36   148.8
  148.56  147.86  147.63  147.16  147.64  147.42  146.39  144.19  142.31  141.87
  141.44  141.22  139.51  138.22   137.8  137.85  137.23  136.77  136.61   136.3
  135.84  135.84  135.69  135.26  135.26  135.13  135.06  134.66  134.39   135.4
  136.33  143.59  147.59  146.54  152.76  161.29  164.55
  162.63  152.75  151.64   150.7  150.23   149.6  149.08  147.93  147.21  147.06
  146.24  146.11  144.98  146.47  147.64  147.42  146.39   143.3  137.63  135.95
  134.87  133.76  129.15  130.53  130.13  129.73   129.1   129.6  129.32  129.91
  129.49  134.06  133.91  133.48  129.01  130.61  131.13  131.61  134.39   135.4
  136.33  143.59  147.59  146.54  152.76  161.29  164.55
  4135.3  4181.2  4201.2  4211.2  4225.3  4245.3  4265.3  4310.6  4321.2  4331.2
  4341.2  4371.2  4381.2  4401.2  4421.2  4431.2  4441.2  4511.2  4580.6  4601.2
  4621.2  4631.2  4711.2  4771.2  4790.6  4810.6  4841.2  4871.2  4881.2  4901.2
 4930.91    4931  4940.6 5068.89    5069  5108.6  5128.6  5248.6  5304.5  5314.5
  5338.6  5398.6  5468.6  5488.6  5608.6  6028.6  6298.6  6624.6
  162.51  159.66  158.42   157.8  156.92  155.32  150.68  149.97  149.36   148.8
  148.56  147.86  147.63  147.16  147.53  147.31  146.28  144.19  142.31  141.87
  141.44  141.22  139.51  138.22   137.8  137.85  137.23  136.77  136.61   136.3
  135.84  135.84  135.69  135.26  135.26  135.13  135.06  134.66  134.47  134.28
  135.29  136.28  143.48  147.48  146.43  152.65  161.18  164.43
  162.38   152.5  151.39  150.45  149.98  149.35  148.83  147.68  146.96  146.81
  145.99  145.86  144.73  146.22  147.39  147.17  146.14  143.05  137.38   135.7
  134.62  133.51   128.9  130.28  129.88  129.48  128.85  129.35  129.07  129.66
  129.24  133.81  133.66  133.23  128.76  130.36  130.88  131.36  133.71  134.14
  135.15  136.08  143.34  147.34  146.29  152.51  161.04   164.3
Pier Skew, UpSta & Num, DnSta & Num=,4983.7, 2 ,4983.7, 2 , 0 , 0 , 0 ,,
       2       2
  122.48  134.77
       2       2
  122.23  134.52
Pier Skew, UpSta & Num, DnSta & Num=,5016.2, 2 ,5016.2, 2 , 0 , 0 , 0 ,,
       2       2
  122.42  134.66
       2       2
  122.17  134.41
Abutment Skew #Up #Dn=, 2 , 2
 4930.80 4967.50
  134.06  127.97
 4930.80 4967.50
  133.81  127.72
Abutment Skew #Up #Dn=, 2 , 2
 5032.50 5069.09
  127.53  133.48
 5032.50 5069.09
  127.28  133.23
BR Coef= 1 , 1 , 0 ,1.25, 0 ,,,0.8,0,2,0,
Wspro=,,,, 1 ,,,, 0 ,,,, 0 ,,,,-1 ,-1 ,-1 , 0 , 0 , 0 , 0 , 0
BC Design=,, 0 ,, 0 ,,,,,,
BR U #Sta/Elev= 75
  4135.3  162.63  4181.2  152.75  4201.2  151.64  4211.2   150.7  4225.3  150.23
  4241.2   149.7  4245.3   149.6  4265.3  149.08  4310.6  147.93  4311.2  147.91
  4321.2  147.21  4330.6  147.07  4331.2  147.06  4341.2  146.24  4371.2  146.11
  4381.2  144.98  4400.6  146.43  4401.2  146.47  4421.2  147.64  4431.2  147.42
  4441.2  146.39  4511.2   143.3  4580.6  137.63  4601.2  135.95  4621.2  134.87
  4631.2  133.76  4711.2  129.15  4771.2  130.53  4790.6  130.13  4810.6  129.73
  4840.6  129.11  4841.2   129.1  4871.2   129.6  4881.2  129.32  4901.2  129.91
 4930.91  129.49    4931  129.49  4940.6  129.36  4951.2  129.21  4967.5  127.97
  4979.5  127.05  4986.5  122.25  5013.5  122.25  5020.5  127.05  5032.5  127.53
 5068.89  129.01    5069  129.01  5108.6  130.61  5128.6  131.13  5248.6  131.61
  5304.5  133.96  5314.5  134.39  5324.5  134.81  5334.5  135.23  5338.6   135.4
  5344.5  135.49  5374.5  135.96  5398.6  136.33  5424.5  139.02  5454.5  142.13
  5468.6  143.59  5488.6  147.59  5608.6  146.54  5794.5  149.29  5884.5  150.63
  5914.5  151.07  5964.5  151.81  6028.6  152.76  6034.5  152.95  6234.5  159.26
  6298.6  161.29  6327.2   161.6  6534.5  163.66  6564.5  163.95  6624.6  164.55
BR U #Mann= 3
 4135.30   0.131  4979.5   0.055  5020.5   0.131
BR U Banks=4979.50,5020.50
BR D #Sta/Elev= 75
  4135.3  162.38  4181.2   152.5  4201.2  151.39  4211.2  150.45  4225.3  149.98
  4241.2  149.45  4245.3  149.35  4265.3  148.83  4310.6  147.68  4311.2  147.66
  4321.2  146.96  4330.6  146.82  4331.2  146.81  4341.2  145.99  4371.2  145.86
  4381.2  144.73  4400.6  146.18  4401.2  146.22  4421.2  147.39  4431.2  147.17
  4441.2  146.14  4511.2  143.05  4580.6  137.38  4601.2   135.7  4621.2  134.62
  4631.2  133.51  4711.2   128.9  4771.2  130.28  4790.6  129.88  4810.6  129.48
  4840.6  128.86  4841.2  128.85  4871.2  129.35  4881.2  129.07  4901.2  129.66
 4930.91  129.24    4931  129.24  4940.6  129.11  4951.2  128.96  4967.5  127.72
  4979.5   126.8  4986.5     122  5013.5     122  5020.5   126.8  5032.5  127.28
 5068.89  128.76    5069  128.76  5108.6  130.36  5128.6  130.88  5248.6  131.36
  5304.5  133.71  5314.5  134.14  5324.5  134.56  5334.5  134.98  5338.6  135.15
  5344.5  135.24  5374.5  135.71  5398.6  136.08  5424.5  138.77  5454.5  141.88
  5468.6  143.34  5488.6  147.34  5608.6  146.29  5794.5  149.04  5884.5  150.38
  5914.5  150.82  5964.5  151.56  6028.6  152.51  6034.5   152.7  6234.5  159.01
  6298.6  161.04  6327.2  161.35  6534.5  163.41  6564.5   163.7  6624.6   164.3
BR D #Mann= 3
 4135.30   0.131  4979.5   0.055  5020.5   0.131
BR D Banks=4979.50,5020.50

Type RM Length L Ch R = 1 ,40183.9,392,392,392
BEGIN DESCRIPTION:
Downstream Section of Bridge/Culvert/Weir
END DESCRIPTION:
#Sta/Elev= 30
  4135.3  162.38  4181.2   152.5  4211.2  150.45  4311.2  147.66  4341.2  145.99
  4371.2  145.86  4381.2  144.73  4421.2  147.39  4431.2  147.17  4511.2  143.05
  4631.2  133.51  4711.2   128.9  4771.2  130.28  4841.2  128.85  4901.2  129.66
  4951.2  128.96  4979.5   126.8  4986.5     122  5013.5     122  5020.5   126.8
  5128.6  130.88  5248.6  131.36  5338.6  135.15  5398.6  136.08  5468.6  143.34
  5488.6  147.34  5608.6  146.29  6028.6  152.51  6298.6  161.04  6624.6   164.3
#Mann= 3 , 1 , 0
 4135.30   0.131       0  4979.5   0.055       0  5020.5   0.131       0
#XS Ineff= 2 , 0
       0    4920     136    5079       0     134
Bank Sta=4979.50,5020.50
Exp/Cntr=0.5,0.3

Type RM Length L Ch R = 1 ,39791.9,289.1,289.1,289.1
BEGIN DESCRIPTION:
Rocky Swamp 80.0
END DESCRIPTION:
#Sta/Elev= 30
  4288.5  152.38  4468.5  145.45  4688.5  139.23  4758.5  133.53  4858.5  130.57
  4878.5  128.12  4918.5  129.75  4958.5   129.5  4968.5  128.82  4983.7  124.95
  4985.2  121.95  5014.7  121.95  5016.2  124.95  5062.4  129.05  5112.4  131.57
  5132.4  131.54  5302.4  139.13  5402.4  137.24  5442.4  139.18  5502.4  139.99
  5552.4  138.86  5572.4  140.47  5652.4  142.24  5672.4  141.53  5812.4  144.36
  6042.4  145.78  6072.4  148.05  6342.4  153.16  6552.4  161.95  6564.2  163.34
#Mann= 3 , 1 , 0
 4288.50   0.131       0  4983.7   0.055       0  5016.2   0.131       0
Bank Sta=4983.70,5016.20
Exp/Cntr=0.3,0.1

Type RM Length L Ch R = 1 ,39502.8,502.8,502.8,502.8
BEGIN DESCRIPTION:
Rocky Swamp 79.0
END DESCRIPTION:
#Sta/Elev= 30
  4306.8  153.23  4326.8   151.4  4406.8  147.47  4436.8  144.67  4506.8  142.93
  4566.8  137.52  4646.8  134.54  4676.8  134.38  4716.8  131.16  4766.8  129.09
  4876.8  126.96  4916.8  127.41  4946.8  128.94  4983.8  124.92  4985.3  121.92
  5014.8  121.92  5016.3  124.92    5040  129.25    5140  129.25    5270  131.36
    5320  130.67    5380  134.71    5790  137.36    5860  139.03    5900  141.55
    6100  146.09    6550  150.43    6630  155.58    6660  159.93  6704.7  162.62
#Mann= 3 , 1 , 0
 4306.80   0.141       0  4983.8   0.055       0  5016.3   0.141       0
Bank Sta=4983.80,5016.30
Exp/Cntr=0.3,0.1

Type RM Length L Ch R = 1 ,39000.0,502,502,502
BEGIN DESCRIPTION:
Rocky Swamp 78.0
END DESCRIPTION:
#Sta/Elev= 30
  4372.6  154.33  4442.6  150.71  4532.6  143.69  4582.6  135.24  4622.6  130.77
  4952.6  129.38  4983.8  124.86  4985.3  121.86  5014.7  121.86  5016.2  124.86
    5040   130.7    5110  128.26    5230   130.1    5420  129.09    5530  132.06
    5550  130.88    5650  132.24    5690  131.38    5770  133.84    5940  135.23
    6130  139.85    6230  144.39    6260  143.52    6300  145.62    6330  144.64
    6430  147.59    6790  151.19    6880   154.9    6970  161.94  7059.9  165.37
#Mann= 3 , 1 , 0
 4372.60   0.141       0  4983.8   0.055       0  5016.2   0.141       0
Bank Sta=4983.80,5016.20
Exp/Cntr=0.3,0.1

Type RM Length L Ch R = 1 ,38498.0,500.3,500.3,500.3
BEGIN DESCRIPTION:
Rocky Swamp 77.0
END DESCRIPTION:
#Sta/Elev= 30
  4253.6  153.85  4393.6  148.33  4493.6  132.43  4553.6   129.5  4724.9  129.83
  4783.6  126.82  4873.6  129.79  4963.6  128.95  4973.6  128.55  4983.7  124.81
  4985.2  121.81  5014.7  121.81  5016.2  124.81    5030  128.84    5040  129.22
    5200  127.34  5324.9  128.82    5560  126.93    5610  128.26    6260  127.44
    6420  132.65    6780  131.01    6800  132.73    6880  133.04    6920  138.26
    6970  154.74    7080  173.01    7170   183.4    7240  188.85  7335.2  190.94
#Mann= 5 , 1 , 0
 4253.60       1       0  4724.9    0.15       0  4983.7   0.055       0
  5016.2    0.15       0  5324.9       1       0
Bank Sta=4983.70,5016.20
Exp/Cntr=0.3,0.1

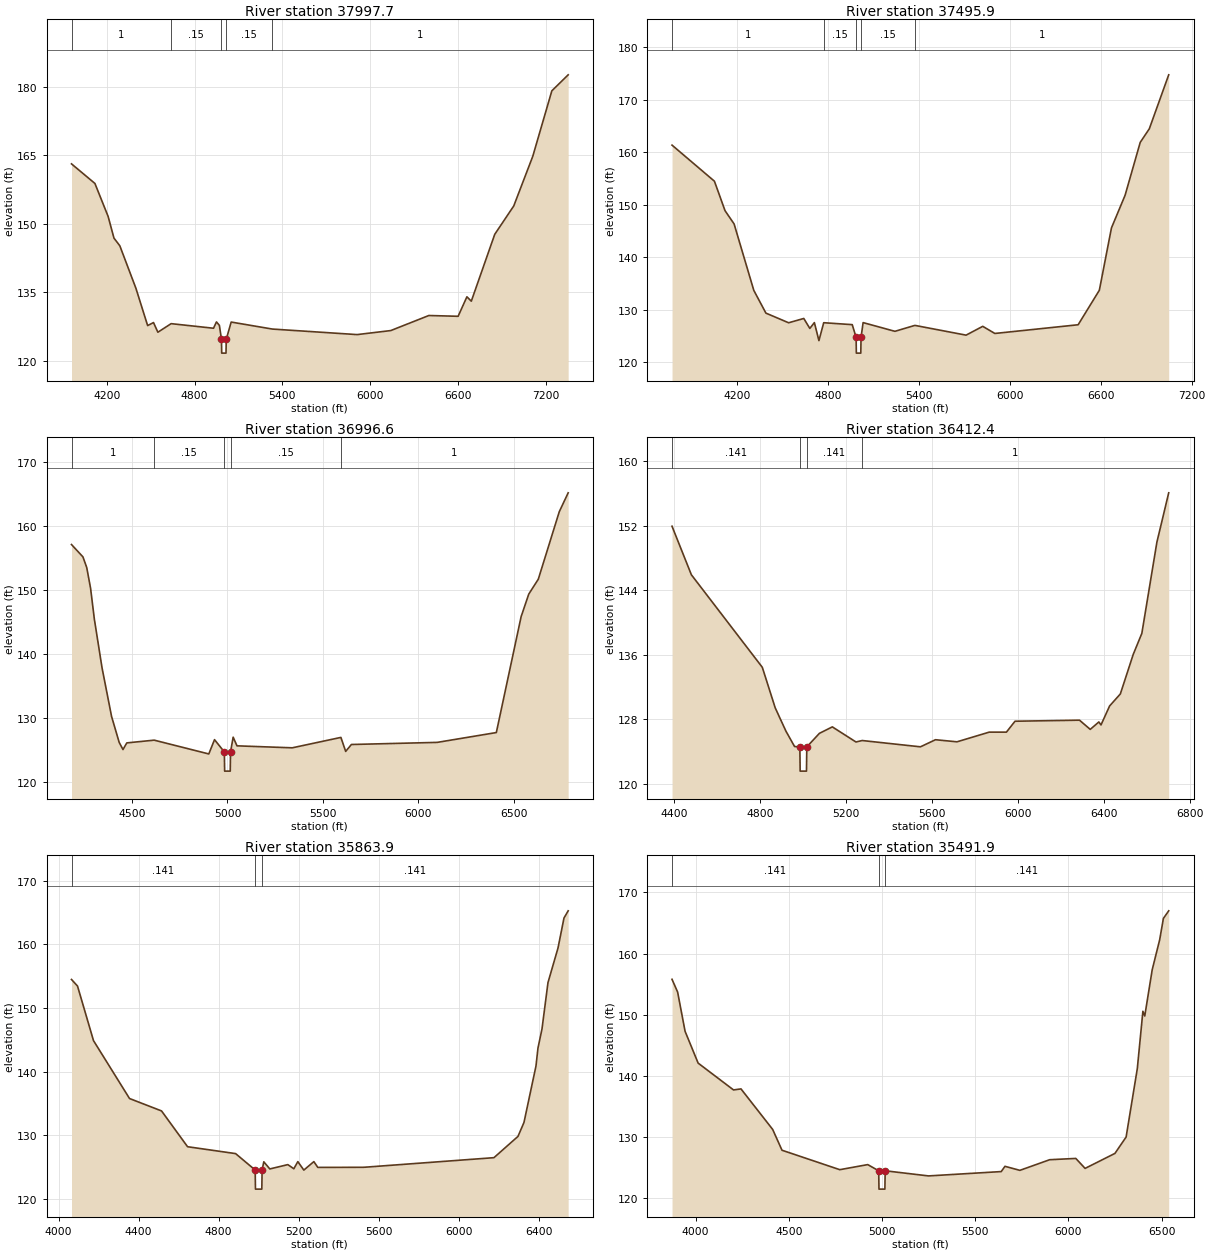
Type RM Length L Ch R = 1 ,37997.7,501.8,501.8,501.8
BEGIN DESCRIPTION:
Rocky Swamp 76.0
END DESCRIPTION:
#Sta/Elev= 30
  3959.4  163.11  4119.4  158.83  4209.4  151.64  4249.4  146.89  4289.4  145.21
  4399.4  135.92  4479.4  127.77  4519.4  128.43  4549.4  126.32  4639.9  128.19
  4929.4  127.19  4949.4  128.57  4969.4  127.82  4983.7  124.75  4985.2  121.75
  5014.7  121.75  5016.2  124.75    5050  128.54  5330.9  127.01    5910   125.8
    6140  126.68    6400  129.97    6600   129.8    6660  134.06    6690   133.1
    6850  147.71    6980  153.92    7110  164.78    7240  179.07  7351.6  182.57
#Mann= 5 , 1 , 0
 3959.40       1       0  4639.9    0.15       0  4983.7   0.055       0
  5016.2    0.15       0  5330.9       1       0
Bank Sta=4983.70,5016.20
Exp/Cntr=0.3,0.1

Type RM Length L Ch R = 1 ,37495.9,499.3,499.3,499.3
BEGIN DESCRIPTION:
Rocky Swamp 75.0
END DESCRIPTION:
#Sta/Elev= 30
  3768.2  161.37  4048.2  154.49  4118.2  148.87  4178.2  146.33  4308.2  133.67
  4388.2  129.33  4538.2  127.49  4638.2  128.31  4678.2  126.41  4708.2  127.52
  4738.2  124.09  4769.9   127.5  4958.2  127.13  4983.8   124.7  4985.3   121.7
  5014.8   121.7  5016.3   124.7    5030  127.52    5240  125.86  5371.9  126.99
    5710  125.13    5820  126.81    5900  125.45    6450  127.11    6590  133.69
    6670  145.58    6760  151.81    6860   161.9    6920  164.49    7048  174.78
#Mann= 5 , 1 , 0
 3768.20       1       0  4769.9    0.15       0  4983.8   0.055       0
  5016.3    0.15       0  5371.9       1       0
Bank Sta=4983.80,5016.30
Exp/Cntr=0.3,0.1

Type RM Length L Ch R = 1 ,36996.6,584.2,584.2,584.2
BEGIN DESCRIPTION:
Rocky Swamp 74.0
END DESCRIPTION:
#Sta/Elev= 30
  4182.3  157.12  4242.3  155.19  4262.3  153.51  4282.3  150.28  4302.3  145.41
  4342.3  137.84  4392.3  130.22  4432.3  126.14  4452.3  125.02  4472.3  126.06
  4615.9  126.49  4902.3  124.33  4932.3  126.57  4983.8  124.64  4985.3  121.64
  5014.7  121.64  5016.2  124.64    5030  126.96    5050   125.6    5340  125.29
  5594.9  126.92    5620  124.73    5650  125.81    6100  126.14    6410  127.68
    6540  145.83    6580  149.36    6630  151.69    6740  162.26  6786.7  165.22
#Mann= 5 , 1 , 0
 4182.30       1       0  4615.9    0.15       0  4983.8   0.055       0
  5016.2    0.15       0  5594.9       1       0
Bank Sta=4983.80,5016.20
Exp/Cntr=0.3,0.1

Type RM Length L Ch R = 1 ,36412.4,548.5,548.5,548.5
BEGIN DESCRIPTION:
Rocky Swamp 73.0
END DESCRIPTION:
#Sta/Elev= 30
  4389.2  151.91  4479.2   145.9  4809.2  134.44  4869.2  129.42  4919.2  126.53
  4959.2  124.63  4983.8  124.58  4985.3  121.58  5014.7  121.58  5016.2  124.58
  5074.9  126.26  5134.9  127.06  5244.9  125.19  5273.9  125.37  5544.9  124.59
  5614.9  125.47  5714.9  125.21  5864.9  126.41  5944.9  126.41  5984.9  127.76
  6284.9  127.89  6334.9  126.75  6374.9  127.67  6384.9   127.3  6424.9  129.65
  6474.9  131.14  6534.9  136.04  6574.9  138.64  6644.9  149.93  6699.9  156.05
#Mann= 4 , 1 , 0
 4389.20   0.141       0  4983.8   0.055       0  5016.2   0.141       0
  5273.9       1       0
Bank Sta=4983.80,5016.20
Exp/Cntr=0.3,0.1

Type RM Length L Ch R = 1 ,35863.9,372,372,372
BEGIN DESCRIPTION:
Rocky Swamp 72.0
END DESCRIPTION:
#Sta/Elev= 30
  4064.8  154.46  4094.8  153.43  4174.8  144.85  4354.8  135.76  4514.8  133.81
  4644.8  128.19  4884.8  127.11  4982.6  124.53  4984.1  121.53  5015.8  121.53
  5017.3  124.53  5025.8  125.82  5055.8   124.7  5145.8  125.38  5175.8  124.73
  5195.8  125.85  5225.8  124.52  5275.8  125.85  5295.8  124.94  5525.8  124.96
  6175.8  126.47  6295.8  129.81  6325.8     132  6385.8  140.86  6395.8  143.69
  6415.8  146.68  6445.8  153.97  6495.8  159.39  6525.8  164.11  6546.7  165.24
#Mann= 3 , 1 , 0
 4064.80   0.141       0  4982.6   0.055       0  5017.3   0.141       0
Bank Sta=4982.60,5017.30
Exp/Cntr=0.3,0.1

Type RM Length L Ch R = 1 ,35491.9,500.2,500.2,500.2
BEGIN DESCRIPTION:
Rocky Swamp 71.0
END DESCRIPTION:
#Sta/Elev= 30
  3873.8   155.8  3903.8  153.72  3943.8   147.3  4013.8   142.1  4203.8  137.71
  4243.8  137.88  4413.8  131.25  4463.8  127.85  4773.8  124.67  4923.8   125.5
  4982.6  124.49  4984.1  121.49  5015.8  121.49  5017.3  124.49    5250  123.65
    5640  124.36    5660  125.22    5740  124.56    5900   126.3    6040  126.51
    6090  124.88    6250  127.33    6310  130.01    6370  141.18    6400  150.57
    6410   149.8    6450  157.37    6490  162.26    6510  165.76  6538.5     167
#Mann= 3 , 1 , 0
 3873.80   0.141       0  4982.6   0.055       0  5017.3   0.141       0
Bank Sta=4982.60,5017.30
Exp/Cntr=0.3,0.1

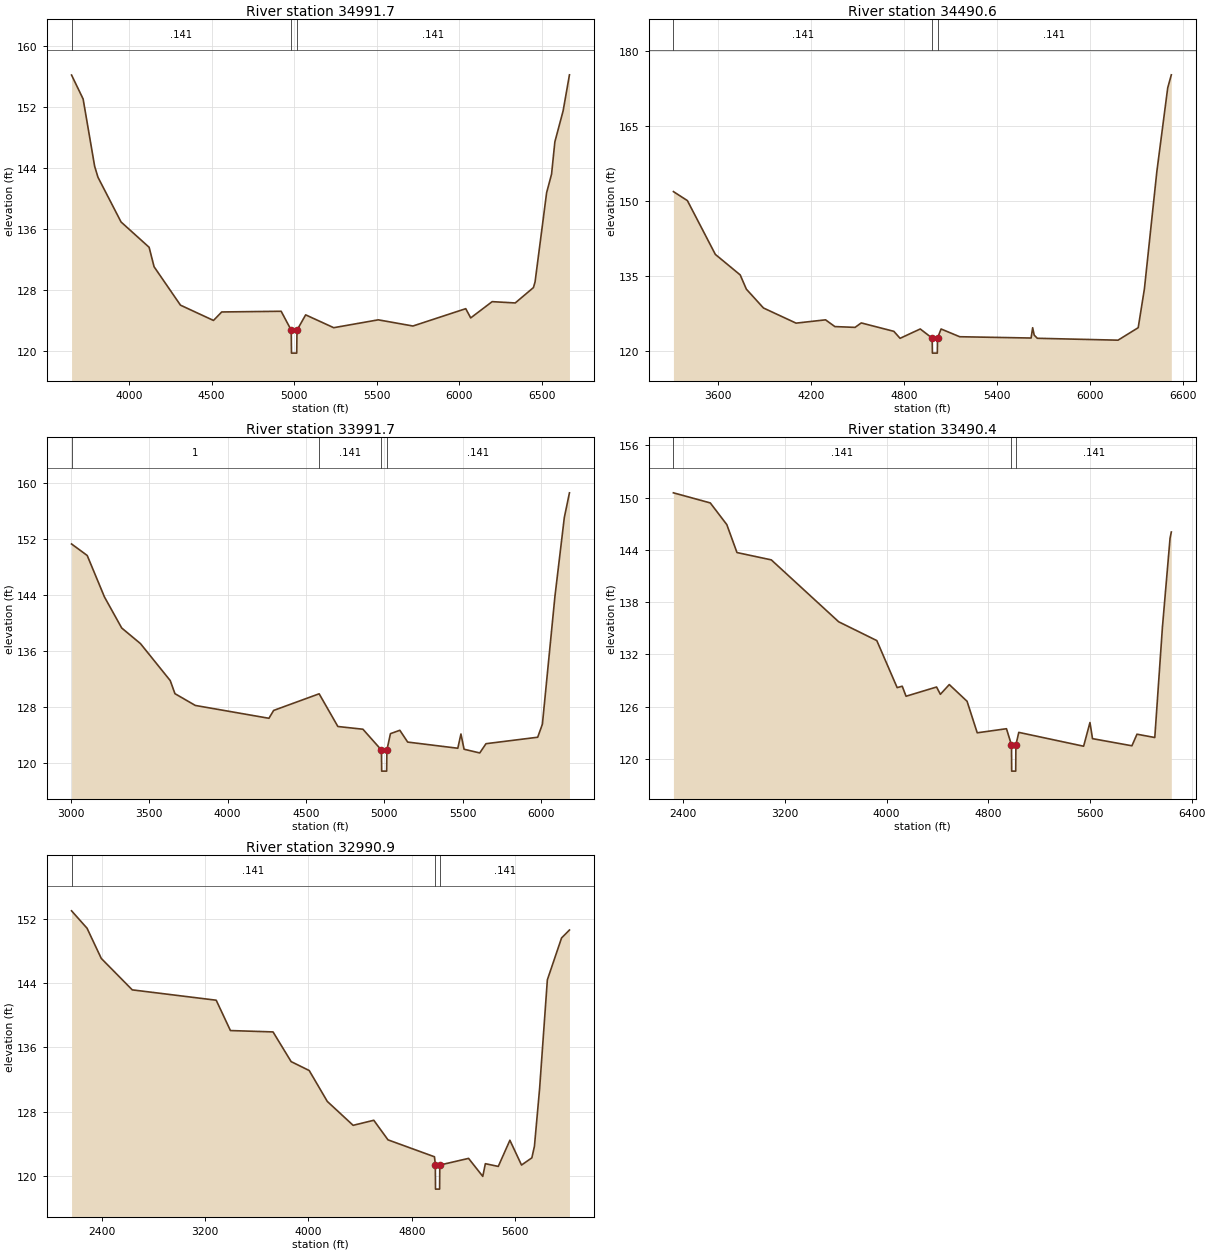
Type RM Length L Ch R = 1 ,34991.7,501.1,501.1,501.1
BEGIN DESCRIPTION:
Rocky Swamp 70.0
END DESCRIPTION:
#Sta/Elev= 30
  3651.4  156.16  3721.4  153.03  3791.4  144.21  3811.4  142.78  3951.4  136.92
  4121.4  133.61  4151.4  131.06  4311.4  126.03  4511.4  124.03  4561.4  125.14
  4921.4  125.23  4982.6  122.75  4984.1  119.75  5015.8  119.75  5017.3  122.75
    5070  124.76    5240  123.08    5510  124.11    5720   123.3    6040  125.57
    6070  124.36    6200  126.49    6340  126.32    6450  128.33    6460  129.07
    6530  140.75    6560  143.19    6580  147.41    6630  151.47  6668.4  156.19
#Mann= 3 , 1 , 0
 3651.40   0.141       0  4982.6   0.055       0  5017.3   0.141       0
Bank Sta=4982.60,5017.30
Exp/Cntr=0.3,0.1

Type RM Length L Ch R = 1 ,34490.6,498.9,498.9,498.9
BEGIN DESCRIPTION:
Rocky Swamp 69.0
END DESCRIPTION:
#Sta/Elev= 30
  3315.8   151.8  3405.8     150  3585.8  139.24  3745.8  135.14  3785.8  132.28
  3895.8  128.52  4105.8  125.49  4295.8  126.15  4355.8   124.8  4485.8  124.64
  4525.8  125.53  4735.8  123.85  4775.8  122.45  4905.8  124.32  4982.7  122.49
  4984.2  119.49  5015.8  119.49  5017.3  122.49    5040  124.32    5160  122.77
    5620  122.51    5630  124.57    5640  123.09    5660  122.46    6180  122.08
    6310  124.58    6350  132.36    6430   155.8    6500  172.54  6523.3  175.16
#Mann= 3 , 1 , 0
 3315.80   0.141       0  4982.7   0.055       0  5017.3   0.141       0
Bank Sta=4982.70,5017.30
Exp/Cntr=0.3,0.1

Type RM Length L Ch R = 1 ,33991.7,501.3,501.3,501.3
BEGIN DESCRIPTION:
Rocky Swamp 68.0
END DESCRIPTION:
#Sta/Elev= 30
  3004.4  151.26  3104.4  149.62  3214.4  143.71  3324.4  139.29  3444.4  137.06
  3634.4  131.79  3664.4  129.93  3794.4  128.25  4264.4  126.42  4294.4  127.54
  4584.9  129.91  4704.4  125.25  4864.4  124.86  4982.6  121.89  4984.1  118.89
  5015.8  118.89  5017.3  121.89    5040  124.23    5100  124.71    5150  123.03
    5470  122.15    5490  124.18    5510  122.01    5610  121.48    5650   122.8
    5980  123.72    6010  125.58    6090  143.79    6150  155.04  6182.7  158.55
#Mann= 4 , 1 , 0
 3004.40       1       0  4584.9   0.141       0  4982.6   0.055       0
  5017.3   0.141       0
Bank Sta=4982.60,5017.30
Exp/Cntr=0.3,0.1

Type RM Length L Ch R = 1 ,33490.4,499.5,499.5,499.5
BEGIN DESCRIPTION:
Rocky Swamp 67.0
END DESCRIPTION:
#Sta/Elev= 30
  2323.2  150.55  2613.2  149.39  2743.2   146.9  2823.2  143.69  3093.2  142.85
  3623.2  135.74  3923.2  133.58  4083.2  128.18  4123.2  128.34  4153.2  127.19
  4393.2  128.25  4423.2  127.41  4493.2  128.53  4633.2  126.61  4713.2  122.99
  4943.2  123.46  4982.7  121.59  4984.2  118.59  5015.8  118.59  5017.3  121.59
    5040  123.04    5550  121.45    5600  124.17    5620  122.32    5930   121.5
    5970  122.83    6110  122.45    6170  135.11    6230  145.33    6240  146.05
#Mann= 3 , 1 , 0
 2323.20   0.141       0  4982.7   0.055       0  5017.3   0.141       0
Bank Sta=4982.70,5017.30
Exp/Cntr=0.3,0.1

Type RM Length L Ch R = 1 ,32990.9,497.4,497.4,497.4
BEGIN DESCRIPTION:
Rocky Swamp 66.0
END DESCRIPTION:
#Sta/Elev= 30
  2166.2  153.01  2286.2  150.84  2396.2  147.08  2636.2  143.16  3286.2  141.87
  3396.2  138.09  3726.2  137.92  3866.2  134.22  4006.2  133.11  4146.2  129.26
  4346.2  126.28  4506.2  126.91  4616.2  124.47  4976.2  122.36  4982.6  121.33
  4984.1  118.33  5015.8  118.33  5017.3  121.33    5240  122.16    5350  119.92
    5370   121.5    5470  121.16    5560  124.42    5650  121.33    5730  122.23
    5750  123.67    5790  130.85    5850  144.41    5960  149.63  6021.1  150.62
#Mann= 3 , 1 , 0
 2166.20   0.141       0  4982.6   0.055       0  5017.3   0.141       0
Bank Sta=4982.60,5017.30
Exp/Cntr=0.3,0.1