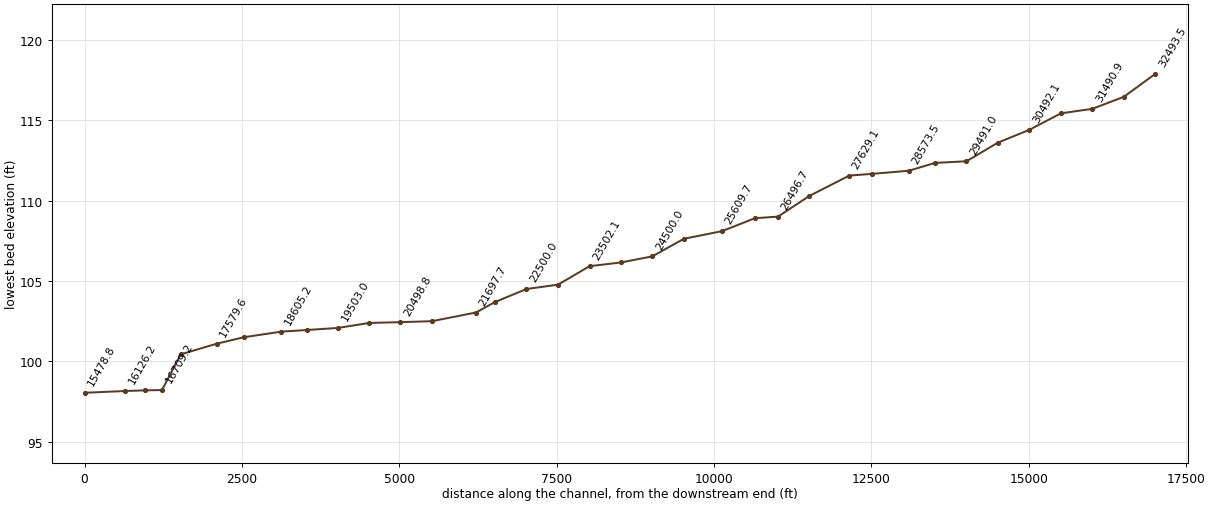
HEC-RAS study 021209_rocky_swamp.prj: Rocky Swamp

--- 021209_rocky_swamp.g01 (geometry) --- (continued)

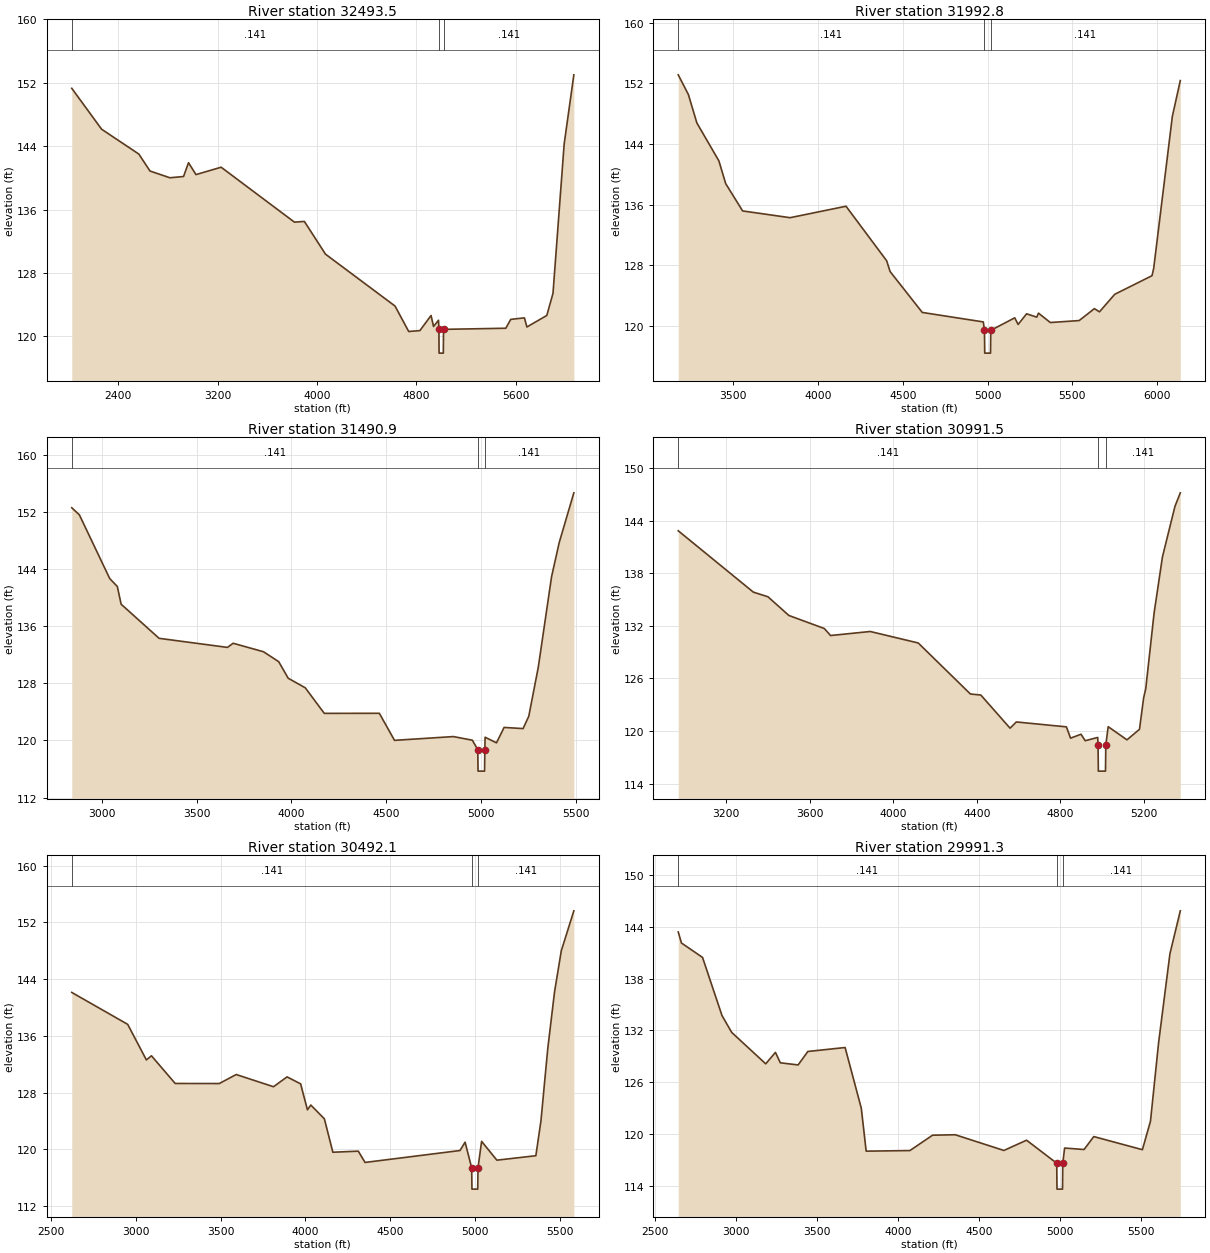
Type RM Length L Ch R = 1 ,32493.5,500.7,500.7,500.7
BEGIN DESCRIPTION:
Rocky Swamp 65.0
END DESCRIPTION:
#Sta/Elev= 30
  2025.5   151.3  2265.5  146.14  2565.5     143  2655.5  140.86  2815.5  140.01
  2925.5  140.17  2965.5  141.91  3025.5  140.41  3228.3  141.34  3818.3  134.41
  3898.3   134.5  4068.3  130.37  4628.3  123.82  4738.3  120.61  4828.3  120.72
  4918.3  122.63  4938.3  121.24  4978.3  122.03  4981.4  120.88  4982.9  117.88
  5017.1  117.88  5018.6  120.88    5520  121.02    5560  122.14    5670  122.33
    5690  121.18    5850  122.63    5900  125.42    5990  144.27  6067.9     153
#Mann= 3 , 1 , 0
 2025.50   0.141       0  4981.4   0.055       0  5018.6   0.141       0
Bank Sta=4981.40,5018.60
Exp/Cntr=0.3,0.1

Type RM Length L Ch R = 1 ,31992.8,501.9,501.9,501.9
BEGIN DESCRIPTION:
Rocky Swamp 64.0
END DESCRIPTION:
#Sta/Elev= 30
  3174.5  153.11  3234.5  150.51  3284.5  146.77  3414.5  141.77  3454.5  138.78
  3554.5  135.18  3834.5  134.29  4164.5   135.8  4404.5  128.61  4424.5   127.2
  4614.5  121.81  4974.5  120.56  4981.4  119.45  4982.9  116.45  5017.1  116.45
  5018.6  119.45    5160   121.1    5180  120.23    5230  121.63    5290  121.19
    5300  121.72    5370  120.48    5540  120.74    5630  122.31    5660  121.89
    5750   124.2    5970  126.65    5980  127.64    6090  147.65  6136.9  152.35
#Mann= 3 , 1 , 0
 3174.50   0.141       0  4981.4   0.055       0  5018.6   0.141       0
Bank Sta=4981.40,5018.60
Exp/Cntr=0.3,0.1

Type RM Length L Ch R = 1 ,31490.9,499.4,499.4,499.4
BEGIN DESCRIPTION:
Rocky Swamp 63.0
END DESCRIPTION:
#Sta/Elev= 30
  2842.9  152.59  2882.9   151.6  3042.9  142.67  3082.9  141.56  3102.9  139.08
  3302.9   134.3  3662.9  133.03  3692.9  133.61  3852.9  132.42  3932.9  131.03
  3982.9  128.71  4072.9  127.37  4172.9  123.79  4462.9   123.8  4542.9  120.01
  4852.9  120.54  4952.9  120.03  4981.4   118.7  4982.9   115.7  5017.1   115.7
  5018.6   118.7    5020  120.45    5080  119.66    5120  121.82    5220  121.66
    5250  123.38    5300  130.23    5370  142.92    5410  147.68  5487.4  154.68
#Mann= 3 , 1 , 0
 2842.90   0.141       0  4981.4   0.055       0  5018.6   0.141       0
Bank Sta=4981.40,5018.60
Exp/Cntr=0.3,0.1

Type RM Length L Ch R = 1 ,30991.5,499.4,499.4,499.4
BEGIN DESCRIPTION:
Rocky Swamp 62.0
END DESCRIPTION:
#Sta/Elev= 30
  2969.8  142.84  3329.8  135.84  3399.8  135.31  3499.8  133.18  3669.8  131.69
  3699.8  130.89  3889.8  131.35  4119.8  130.04  4369.8  124.22  4419.8   124.1
  4559.8  120.32  4589.8  121.03  4829.8  120.47  4849.8  119.18  4899.8  119.63
  4919.8  118.89  4979.8  119.26  4981.4  118.42  4982.9  115.42  5017.1  115.42
  5018.6  118.42    5030  120.49    5120  118.99    5180  120.19    5200   123.8
    5210  124.82    5250  133.45    5290  139.86    5350  145.63  5375.6  147.17
#Mann= 3 , 1 , 0
 2969.80   0.141       0  4981.4   0.055       0  5018.6   0.141       0
Bank Sta=4981.40,5018.60
Exp/Cntr=0.3,0.1

Type RM Length L Ch R = 1 ,30492.1,500.8,500.8,500.8
BEGIN DESCRIPTION:
Rocky Swamp 61.0
END DESCRIPTION:
#Sta/Elev= 30
  2622.5  142.12  2952.5  137.62  3062.5  132.61  3092.5  133.19  3232.5  129.29
  3492.5  129.28  3592.5  130.55  3812.5  128.83  3892.5  130.22  3972.5  129.23
  4012.5  125.58  4032.5  126.25  4112.5  124.31  4162.5   119.6  4312.5  119.75
  4352.5  118.16  4912.5  119.84  4942.5  121.02  4981.4   117.4  4982.9   114.4
  5017.1   114.4  5018.6   117.4    5040  121.13    5130  118.48    5360  119.11
    5390  124.03    5430  134.16    5470  142.17    5510  147.99    5584  153.62
#Mann= 3 , 1 , 0
 2622.50   0.141       0  4981.4   0.055       0  5018.6   0.141       0
Bank Sta=4981.40,5018.60
Exp/Cntr=0.3,0.1

Type RM Length L Ch R = 1 ,29991.3,500.3,500.3,500.3
BEGIN DESCRIPTION:
Rocky Swamp 60.0
END DESCRIPTION:
#Sta/Elev= 30
  2645.1   143.4  2665.1  142.12  2795.1  140.45  2915.1  133.72  2975.1  131.76
  3185.1  128.12  3245.1  129.45  3275.1  128.24  3385.1  127.99  3445.1  129.55
  3675.1  130.01  3775.1  122.97  3805.1     118  4075.1  118.07  4215.1  119.85
  4355.1   119.9  4655.1  118.08  4795.1  119.27  4981.4   116.6  4982.9   113.6
  5017.1   113.6  5018.6   116.6    5030  118.36    5150  118.19    5210  119.69
    5510  118.17    5560  121.47    5610  130.55    5680  140.87  5744.1  145.85
#Mann= 3 , 1 , 0
 2645.10   0.141       0  4981.4   0.055       0  5018.6   0.141       0
Bank Sta=4981.40,5018.60
Exp/Cntr=0.3,0.1

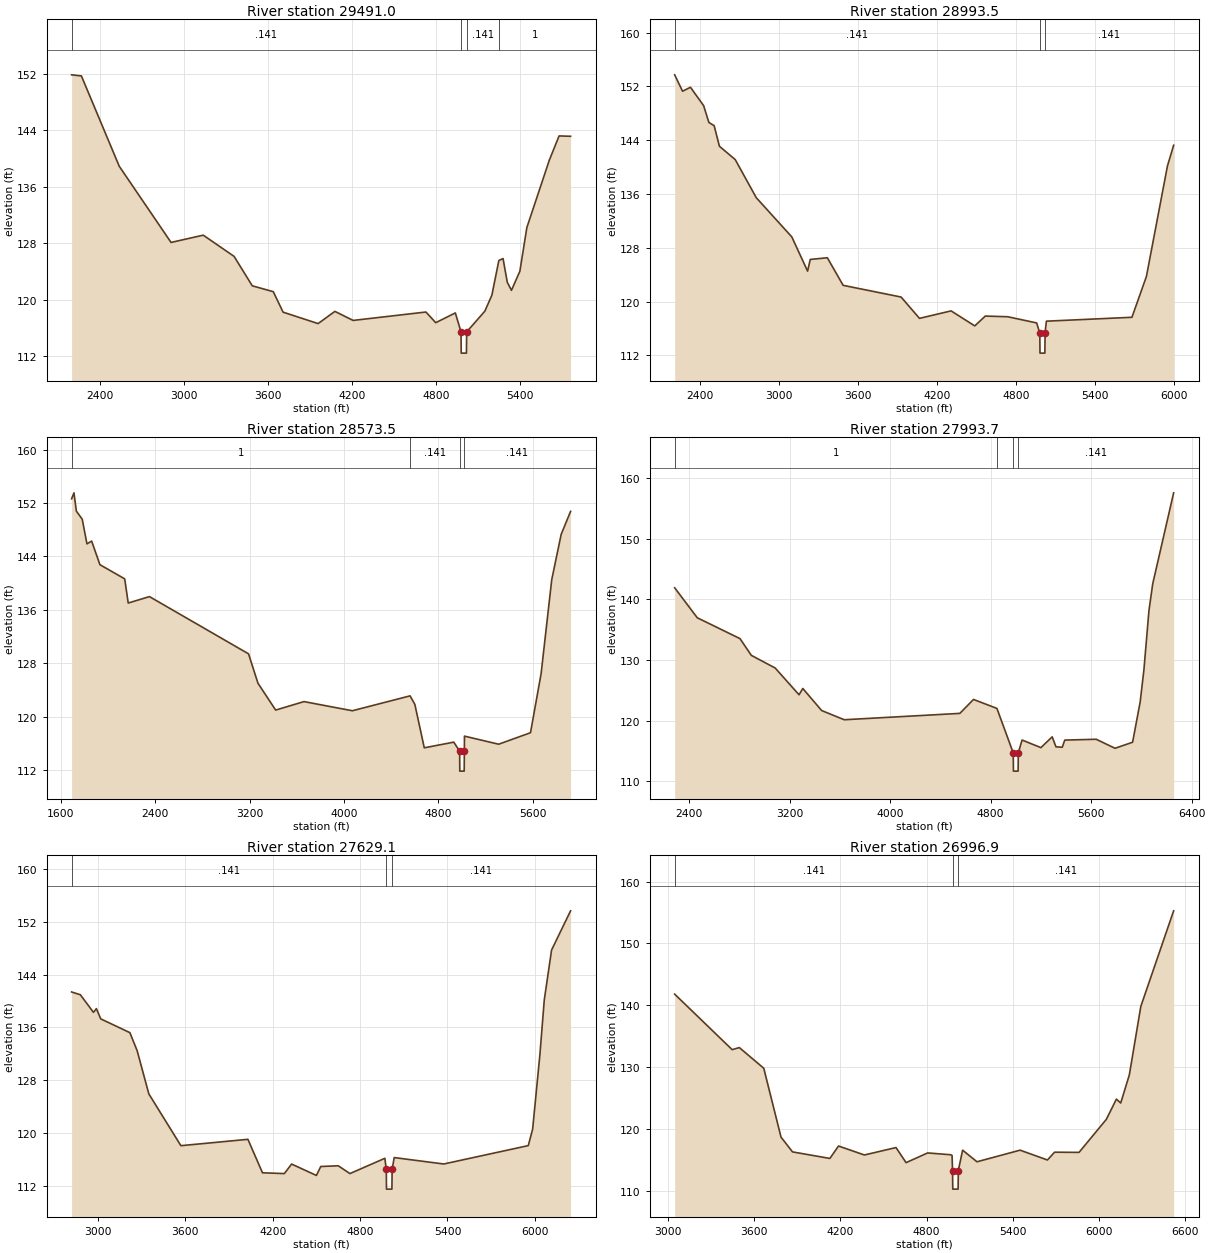
Type RM Length L Ch R = 1 ,29491.0,497.5,497.5,497.5
BEGIN DESCRIPTION:
Rocky Swamp 59.0
END DESCRIPTION:
#Sta/Elev= 30
  2199.3  151.84  2269.3  151.68  2539.3   138.9  2909.3  128.11  3139.3  129.14
  3359.3  126.14  3489.3  121.97  3639.3  121.14  3709.3  118.24  3959.3  116.62
  4079.3  118.35  4209.3  117.07  4729.3  118.26  4799.3  116.75  4939.3  118.13
  4979.9  115.44  4981.4  112.44  5018.6  112.44  5020.1  115.44    5150  118.38
    5200  120.63  5249.9  125.55    5280  125.83    5310  122.48    5340  121.33
    5400  124.03    5450  130.22    5610  139.74    5680  143.19  5762.2  143.14
#Mann= 4 , 1 , 0
 2199.30   0.141       0  4979.9   0.055       0  5020.1   0.141       0
  5249.9       1       0
Bank Sta=4979.90,5020.10
Exp/Cntr=0.3,0.1

Type RM Length L Ch R = 1 ,28993.5,420,420,420
BEGIN DESCRIPTION:
Rocky Swamp 58.0
END DESCRIPTION:
#Sta/Elev= 30
    2206  153.72    2266  151.28    2326  151.87    2426  149.14    2466  146.64
    2506  146.16    2546   143.1    2666  141.12    2826  135.45    3096  129.62
    3216  124.53    3236  126.27    3366  126.52    3486  122.42    3926  120.68
    4066  117.51    4306  118.62    4486  116.39    4566  117.85    4736  117.75
    4956  116.83  4979.9  115.34  4981.4  112.34  5018.6  112.34  5020.1  115.34
    5030  117.09    5680  117.67    5790  123.74    5950  140.18  5996.8  143.25
#Mann= 3 , 1 , 0
 2206.00   0.141       0  4979.9   0.055       0  5020.1   0.141       0
Bank Sta=4979.90,5020.10
Exp/Cntr=0.3,0.1

Type RM Length L Ch R = 1 ,28573.5,579.8,579.8,579.8
BEGIN DESCRIPTION:
Rocky Swamp 57.0
END DESCRIPTION:
#Sta/Elev= 30
  1690.3  152.62  1710.3  153.52  1730.3  150.79  1780.3  149.57  1820.3  145.88
  1860.3  146.29  1930.3  142.76  2140.3  140.64  2170.3  137.02  2350.3  137.98
  3190.3  129.41  3270.3  125.01  3420.3  120.99  3660.3  122.26  4070.3  120.89
  4559.9  123.12  4600.3  121.85  4680.3  115.34  4930.3  116.19  4979.9  114.85
  4981.4  111.85  5018.6  111.85  5020.1  114.85  5020.9  117.09  5310.9  115.88
  5580.9   117.6  5670.9  126.46  5760.9  140.51  5840.9   147.3  5920.7  150.74
#Mann= 4 , 1 , 0
 1690.30       1       0  4559.9   0.141       0  4979.9   0.055       0
  5020.1   0.141       0
Bank Sta=4979.90,5020.10
Exp/Cntr=0.3,0.1

Type RM Length L Ch R = 1 ,27993.7,364.6,364.6,364.6
BEGIN DESCRIPTION:
Rocky Swamp 56.0
END DESCRIPTION:
#Sta/Elev= 30
  2284.8  141.92  2464.8  136.97  2804.8  133.53  2894.8  130.77  3084.8  128.68
  3274.8  124.26  3304.8   125.3  3454.8  121.66  3634.8  120.14  4554.8  121.19
  4663.6  123.49  4849.9  122.01  4979.9  114.66  4981.4  111.66  5018.6  111.66
  5020.1  114.66    5050  116.79    5200  115.54    5290  117.32    5320  115.67
    5370   115.6    5390  116.78    5640  116.92    5790  115.43    5930  116.43
    5990  123.05    6020  128.37    6060  138.13    6090  142.56  6256.6  157.59
#Mann= 4 , 1 , 0
 2284.80       1       0  4849.9   0.141       0  4979.9   0.055       0
  5020.1   0.141       0
Bank Sta=4979.90,5020.10
Exp/Cntr=0.3,0.1

Type RM Length L Ch R = 1 ,27629.1,632.2,632.2,632.2
BEGIN DESCRIPTION:
Rocky Swamp 55.0
END DESCRIPTION:
#Sta/Elev= 30
  2820.3  141.36  2880.3  140.94  2970.3  138.28  2990.3  138.84  3020.3  137.29
  3220.3  135.21  3270.3  132.47  3350.3  125.95  3570.3  118.12  4030.3  119.08
  4130.3  114.02  4280.3   113.9  4330.3  115.34  4500.3  113.62  4530.3  114.97
  4650.3  115.08  4730.3   113.9  4970.3  116.21  4979.9  114.55  4981.4  111.55
  5018.6  111.55  5020.1  114.55  5034.4  116.32  5374.4  115.35  5954.4  118.13
  5984.4  120.61  6034.4  131.91  6064.4  140.17  6114.4   147.7  6244.9  153.63
#Mann= 3 , 1 , 0
 2820.30   0.141       0  4979.9   0.055       0  5020.1   0.141       0
Bank Sta=4979.90,5020.10
Exp/Cntr=0.3,0.1

Type RM Length L Ch R = 1 ,26996.9,500.2,500.2,500.2
BEGIN DESCRIPTION:
Rocky Swamp 54.0
END DESCRIPTION:
#Sta/Elev= 30
  3046.6  141.81  3446.6  132.84  3496.6  133.17  3666.6  129.83  3786.6  118.69
  3866.6  116.31  4126.6  115.25  4186.6  117.26  4366.6  115.81  4586.6  117.01
  4656.6  114.57  4806.6  116.14  4966.6  115.85  4976.6  115.73    4980  113.29
  4981.5  110.29  5018.6  110.29  5020.1  113.29    5050  116.59    5150  114.71
    5450  116.59    5640     115    5690  116.26    5860  116.23    6050  121.57
    6120  124.84    6150  124.21    6210  128.76    6290  139.84  6518.2  155.28
#Mann= 3 , 1 , 0
 3046.60   0.141       0    4980   0.055       0  5020.1   0.141       0
Bank Sta=4980.00,5020.10
Exp/Cntr=0.3,0.1

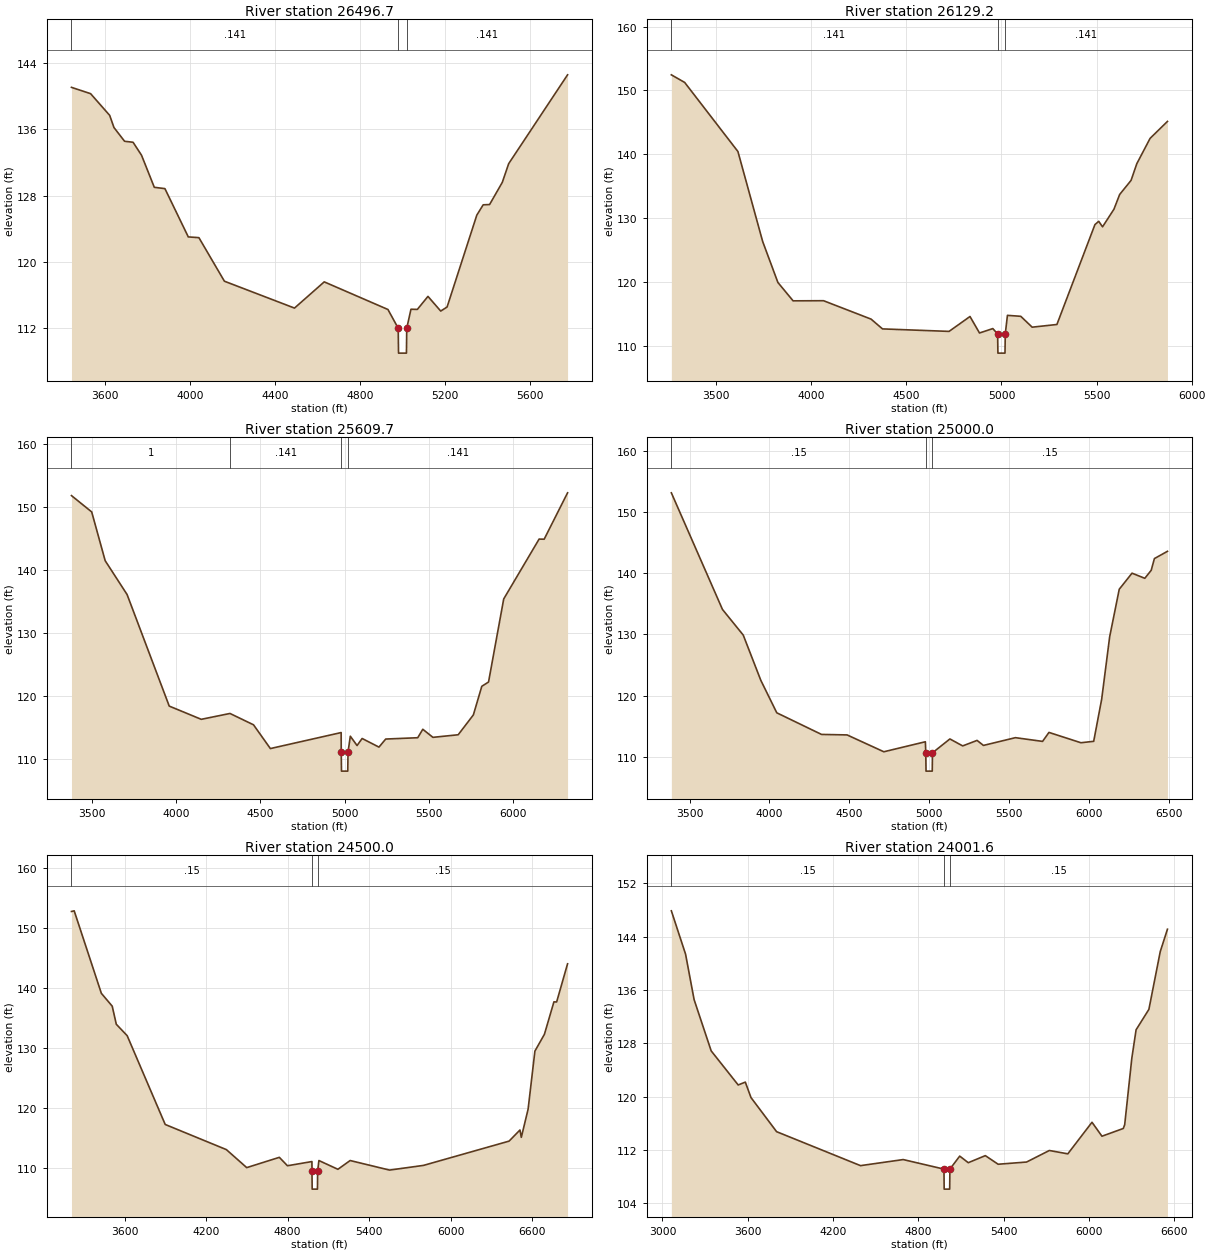
Type RM Length L Ch R = 1 ,26496.7,367.5,367.5,367.5
BEGIN DESCRIPTION:
Rocky Swamp 53.0
END DESCRIPTION:
#Sta/Elev= 30
  3441.6  141.04  3531.6  140.28  3621.6  137.66  3641.6   136.2  3691.6  134.54
  3731.6  134.42  3771.6  132.85  3831.6  128.99  3881.6  128.83  3991.6  123.01
  4041.6  122.92  4161.6  117.67  4491.6  114.43  4631.6  117.59  4931.6  114.26
  4979.9     112  4981.4     109  5018.6     109  5020.1     112    5040  114.29
    5070  114.27    5120  115.84    5180  114.07    5210  114.56    5350  125.64
    5380  126.88    5410  126.91    5470  129.59    5500  131.84  5777.2  142.55
#Mann= 3 , 1 , 0
 3441.60   0.141       0  4979.9   0.055       0  5020.1   0.141       0
Bank Sta=4979.90,5020.10
Exp/Cntr=0.3,0.1

Type RM Length L Ch R = 1 ,26129.2,519.5,519.5,519.5
BEGIN DESCRIPTION:
Rocky Swamp 52.0
END DESCRIPTION:
#Sta/Elev= 30
  3264.6  152.44  3334.6  151.25  3614.6  140.44  3744.6  126.37  3824.6  119.96
  3904.6  117.08  4064.6   117.1  4314.6  114.22  4374.6  112.69  4724.6   112.3
  4834.6  114.63  4884.6  112.05  4954.6  112.74  4979.9   111.9  4981.4   108.9
  5018.6   108.9  5020.1   111.9  5031.5  114.81  5101.5  114.66  5161.5  112.96
  5291.5  113.38  5491.5  129.01  5511.5  129.52  5531.5  128.66  5591.5  131.42
  5621.5  133.72  5681.5  135.93  5711.5  138.53  5781.5   142.5  5872.7  145.15
#Mann= 3 , 1 , 0
 3264.60   0.141       0  4979.9   0.055       0  5020.1   0.141       0
Bank Sta=4979.90,5020.10
Exp/Cntr=0.3,0.1

Type RM Length L Ch R = 1 ,25609.7,609.7,609.7,609.7
BEGIN DESCRIPTION:
Rocky Swamp 51.0
END DESCRIPTION:
#Sta/Elev= 30
  3379.5  151.82  3499.5  149.23  3579.5  141.49  3709.5  136.12  3959.5  118.42
  4149.5  116.32  4319.9  117.25  4459.5  115.45  4559.5  111.68  4979.5  114.22
  4979.9   111.1  4981.4   108.1  5018.6   108.1  5020.1   111.1  5033.8  113.64
  5073.8  112.16  5103.8  113.28  5203.8  111.91  5243.8  113.19  5433.8   113.4
  5463.8  114.74  5523.8  113.46  5673.8  113.87  5763.8  117.02  5813.8  121.56
  5853.8  122.24  5943.8  135.42  6153.8  144.92  6183.8   144.9  6322.6  152.26
#Mann= 4 , 1 , 0
 3379.50       1       0  4319.9   0.141       0  4979.9   0.055       0
  5020.1   0.141       0
Bank Sta=4979.90,5020.10
Exp/Cntr=0.3,0.1

Type RM Length L Ch R = 1 ,25000.0,500,500,500
BEGIN DESCRIPTION:
Rocky Swamp 50.0
END DESCRIPTION:
#Sta/Elev= 30
  3386.4   153.2  3706.4   134.1  3836.4   129.9  3946.4  122.49  4046.4  117.17
  4326.4  113.63  4486.4  113.55  4716.4  110.79  4976.4  112.43    4979  110.62
  4980.5  107.62  5019.4  107.62  5020.9  110.62    5130  112.89    5210  111.75
    5300  112.65    5340  111.83    5540   113.1    5710  112.49    5750  113.96
    5950  112.27    6030   112.5    6080   119.4    6130  129.62    6190  137.41
    6270  140.04    6350   139.2    6390  140.51    6410  142.43  6491.7  143.62
#Mann= 3 , 1 , 0
 3386.40    0.15       0    4979   0.055       0  5020.9    0.15       0
Bank Sta=4979.00,5020.90
Exp/Cntr=0.3,0.1

Type RM Length L Ch R = 1 ,24500.0,498.4,498.4,498.4
BEGIN DESCRIPTION:
Rocky Swamp 49.0
END DESCRIPTION:
#Sta/Elev= 30
  3208.8  152.74  3228.8  152.85  3428.8  139.12  3508.8  136.98  3538.8  133.97
  3618.8  132.07  3898.8  117.29  4348.8  113.11  4498.8  110.11  4738.8  111.82
  4798.8  110.42  4978.8  111.12  4979.1  109.53  4980.6  106.53  5019.4  106.53
  5020.9  109.53    5030  111.29    5170  109.83    5260  111.29    5550   109.7
    5800  110.48    6430  114.52    6510  116.37    6520  115.15    6570  119.84
    6620   129.5    6690   132.3    6760   137.7    6780  137.68  6860.4  144.03
#Mann= 3 , 1 , 0
 3208.80    0.15       0  4979.1   0.055       0  5020.9    0.15       0
Bank Sta=4979.10,5020.90
Exp/Cntr=0.3,0.1

Type RM Length L Ch R = 1 ,24001.6,499.5,499.5,499.5
BEGIN DESCRIPTION:
Rocky Swamp 48.0
END DESCRIPTION:
#Sta/Elev= 30
  3062.4  147.86  3162.4  141.36  3222.4  134.55  3342.4  126.87  3532.4  121.76
  3582.4  122.19  3622.4  119.87  3802.4  114.76  4392.4  109.67  4692.4  110.58
  4979.1  109.15  4980.6  106.15  5019.4  106.15  5020.9  109.15    5090   111.1
    5150  110.11    5270  111.17    5360  109.88    5560  110.21    5720  111.94
    5850  111.44    6020  116.17    6090  114.08    6240  115.24    6250  115.82
    6300  125.77    6330  130.03    6420  133.09    6500  141.76  6550.5   145.1
#Mann= 3 , 1 , 0
 3062.40    0.15       0  4979.1   0.055       0  5020.9    0.15       0
Bank Sta=4979.10,5020.90
Exp/Cntr=0.3,0.1

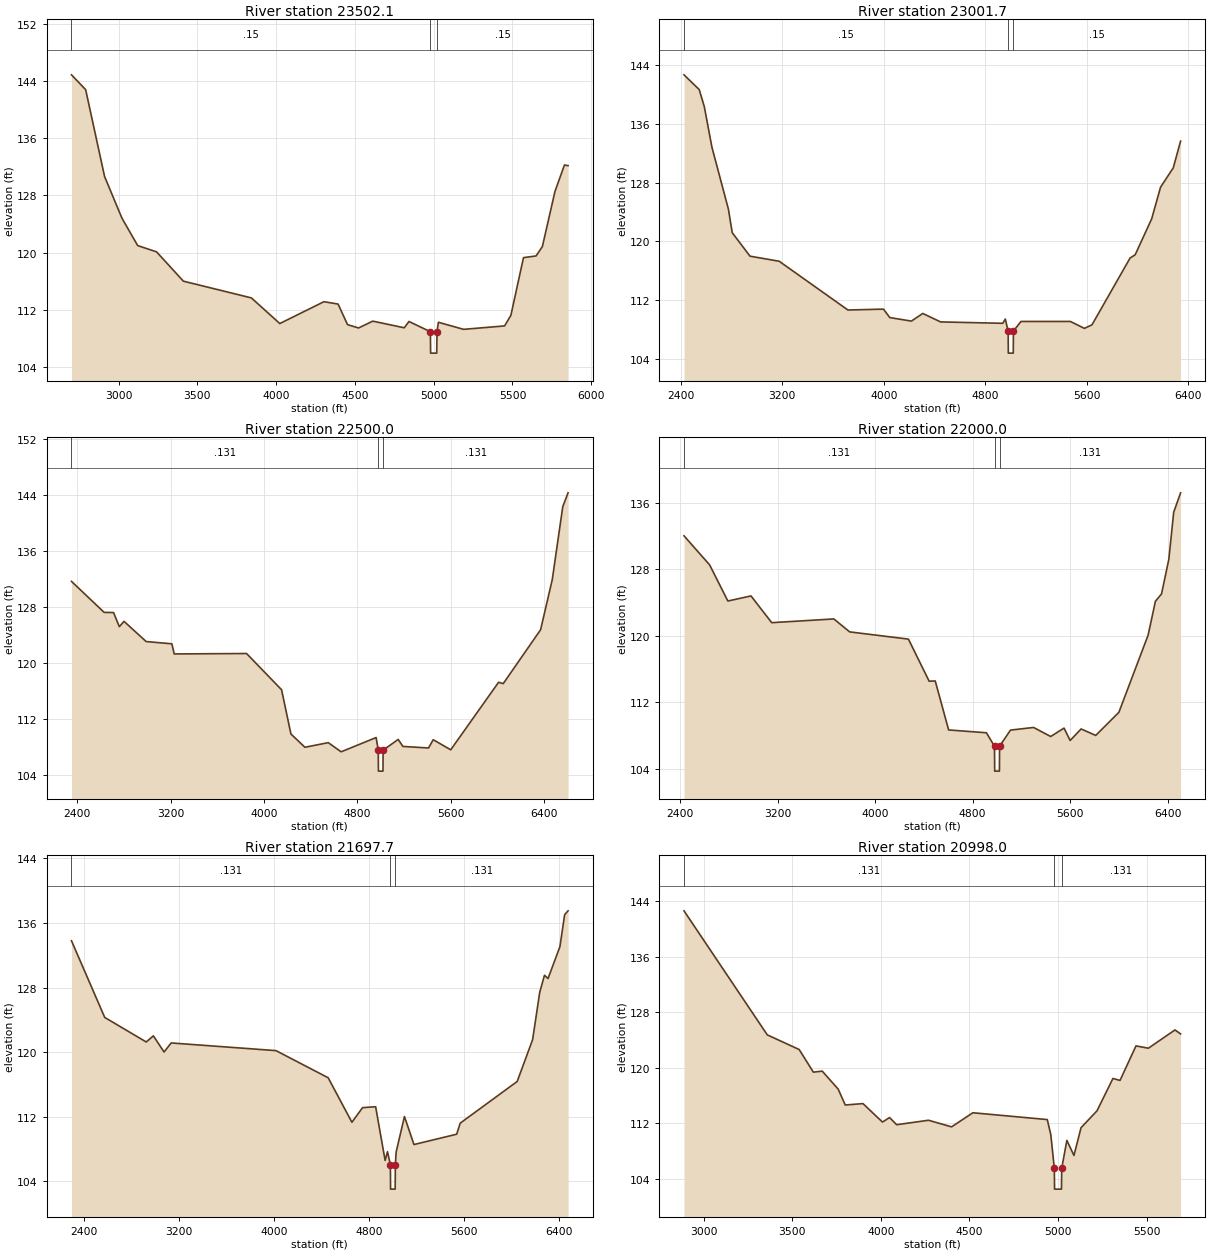
Type RM Length L Ch R = 1 ,23502.1,500.4,500.4,500.4
BEGIN DESCRIPTION:
Rocky Swamp 47.0
END DESCRIPTION:
#Sta/Elev= 30
  2701.1  144.89  2791.1  142.81  2911.1  130.65  3021.1  124.83  3121.1  120.98
  3241.1   120.1  3411.1     116  3843.2  113.65  4023.2  110.06  4303.2  113.12
  4393.2  112.79  4453.2  109.91  4523.2  109.44  4613.2   110.4  4813.2  109.47
  4843.2  110.35    4979  108.92  4980.5  105.92  5019.4  105.92  5020.9  108.92
    5030  110.24    5190  109.25    5450  109.73    5490  111.21    5570  119.29
    5650  119.53    5690  120.85    5770  128.58    5830  132.26    5853  132.17
#Mann= 3 , 1 , 0
 2701.10    0.15       0    4979   0.055       0  5020.9    0.15       0
Bank Sta=4979.00,5020.90
Exp/Cntr=0.3,0.1

Type RM Length L Ch R = 1 ,23001.7,501.7,501.7,501.7
BEGIN DESCRIPTION:
Rocky Swamp 46.0
END DESCRIPTION:
#Sta/Elev= 30
  2425.2  142.66  2545.2  140.65  2585.2  138.33  2645.2  132.81  2775.2  124.36
  2805.2  121.17  2945.2  117.97  3175.2  117.28  3716.8  110.64  3996.8  110.76
  4046.8  109.61  4216.8  109.13  4306.8  110.17  4446.8  109.02  4936.8  108.83
  4956.8  109.41  4979.1  107.77  4980.6  104.77  5019.4  104.77  5020.9  107.77
    5080  109.08    5470  109.08    5580  108.14    5640  108.63    5940  117.72
    5980  118.16    6110  123.05    6180  127.36    6280  129.99  6337.8  133.63
#Mann= 3 , 1 , 0
 2425.20    0.15       0  4979.1   0.055       0  5020.9    0.15       0
Bank Sta=4979.10,5020.90
Exp/Cntr=0.3,0.1

Type RM Length L Ch R = 1 ,22500.0,500,500,500
BEGIN DESCRIPTION:
Rocky Swamp 45.0
END DESCRIPTION:
#Sta/Elev= 30
  2350.9  131.62  2630.9  127.19  2710.9  127.17  2760.9  125.15  2800.9  125.91
  2990.9  123.02  3210.9   122.7  3230.9  121.25  3850.9  121.31  4150.9  116.13
  4230.9  109.81  4350.9  107.91  4550.9  108.57  4660.9  107.26  4960.9   109.3
  4979.1   107.5  4980.6   104.5  5019.4   104.5  5020.9   107.5    5150  109.03
    5190  108.03    5410  107.81    5450  108.99    5600  107.55    6010   117.2
    6050  117.01    6370  124.71    6470  131.88    6560  142.31  6605.4  144.28
#Mann= 3 , 1 , 0
 2350.90   0.131       0  4979.1   0.055       0  5020.9   0.131       0
Bank Sta=4979.10,5020.90
Exp/Cntr=0.3,0.1

Type RM Length L Ch R = 1 ,22000.0,302.3,302.3,302.3
BEGIN DESCRIPTION:
Rocky Swamp 44.0
END DESCRIPTION:
#Sta/Elev= 30
  2430.5  132.03  2640.5  128.54  2790.5  124.18  2980.5  124.79  3150.5  121.57
  3660.5  122.02  3790.5  120.46  4272.7  119.59  4442.7  114.52  4492.7  114.55
  4602.7  108.65  4912.7  108.31  4979.1  106.69  4980.6  103.69  5019.4  103.69
  5020.9  106.69    5110  108.63    5300  108.95    5440  107.86    5550  108.87
    5600  107.38    5690  108.77    5810  107.99    6000  110.77    6240  120.07
    6300  124.15    6350  125.03    6410   129.2    6450  134.87  6506.5  137.21
#Mann= 3 , 1 , 0
 2430.50   0.131       0  4979.1   0.055       0  5020.9   0.131       0
Bank Sta=4979.10,5020.90
Exp/Cntr=0.3,0.1

Type RM Length L Ch R = 1 ,21697.7,699.7,699.7,699.7
BEGIN DESCRIPTION:
Rocky Swamp 43.0
END DESCRIPTION:
#Sta/Elev= 30
  2291.7  133.79  2571.7   124.3  2921.7  121.26  2981.7  122.02  3071.7  120.02
  3131.7  121.14  4014.7  120.19  4454.7  116.83  4654.7  111.32  4744.7  113.13
  4854.7  113.24  4934.7  106.59  4954.7  107.68    4979  106.04  4980.5  103.04
  5019.4  103.04  5020.9  106.04  5027.6  107.64  5097.6  112.03  5177.6  108.56
  5537.6  109.84  5567.6  111.21  6047.6  116.37  6177.6  121.55  6237.6  127.42
  6277.6  129.52  6307.6  129.12  6407.6  133.06  6447.6  137.03  6476.4   137.5
#Mann= 3 , 1 , 0
 2291.70   0.131       0    4979   0.055       0  5020.9   0.131       0
Bank Sta=4979.00,5020.90
Exp/Cntr=0.3,0.1

Type RM Length L Ch R = 1 ,20998.0,499.2,499.2,499.2
BEGIN DESCRIPTION:
Rocky Swamp 42.0
END DESCRIPTION:
#Sta/Elev= 30
  2889.4  142.59  3359.4  124.72  3539.4  122.61  3619.4  119.35  3669.4   119.5
  3759.4  116.91  3799.4  114.62  3899.4  114.82  4009.4  112.16  4049.4  112.81
  4089.4  111.78  4269.4  112.42  4399.4  111.47  4519.4   113.5  4939.4  112.52
  4959.4  110.34  4979.1   105.5  4980.6   102.5  5019.4   102.5  5020.9   105.5
    5050  109.52    5090  107.35    5130  111.35    5220  113.78    5310  118.44
    5350  118.16    5440  123.13    5510   122.8    5660  125.43  5691.7  124.86
#Mann= 3 , 1 , 0
 2889.40   0.131       0  4979.1   0.055       0  5020.9   0.131       0
Bank Sta=4979.10,5020.90
Exp/Cntr=0.3,0.1

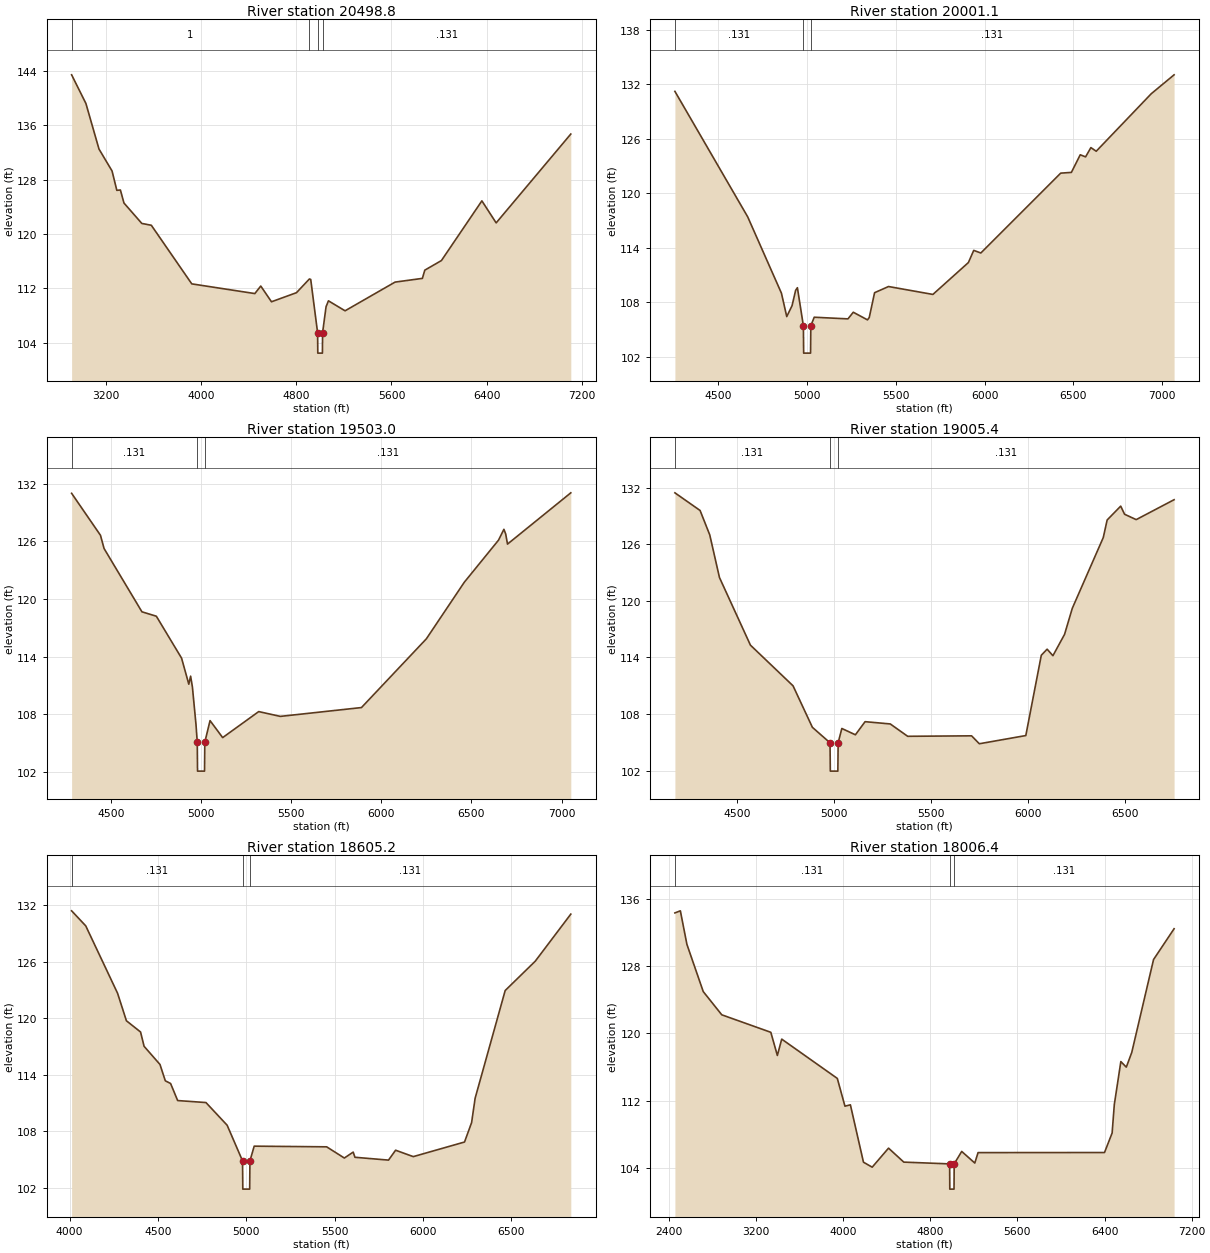
Type RM Length L Ch R = 1 ,20498.8,497.7,497.7,497.7
BEGIN DESCRIPTION:
Rocky Swamp 41.0
END DESCRIPTION:
#Sta/Elev= 30
  2911.3  143.47  3031.3  139.25  3141.3  132.53  3251.3  129.29  3291.3  126.44
  3321.3  126.49  3351.3  124.57  3501.3  121.56  3581.3  121.29  3921.3  112.65
  4451.3  111.22  4501.3  112.33  4591.3  110.01  4801.3  111.35  4909.9  113.37
  4921.3   113.3  4979.1  105.44  4980.6  102.44  5019.4  102.44  5020.9  105.44
    5050  109.27    5070  110.15    5210  108.68    5630  112.91    5860  113.46
    5880  114.67    6020  116.09    6360  124.89    6480  121.64  7107.5  134.74
#Mann= 4 , 1 , 0
 2911.30       1       0  4909.9   0.131       0  4979.1   0.055       0
  5020.9   0.131       0
Bank Sta=4979.10,5020.90
Exp/Cntr=0.3,0.1

Type RM Length L Ch R = 1 ,20001.1,498.1,498.1,498.1
BEGIN DESCRIPTION:
Rocky Swamp 40.0
END DESCRIPTION:
#Sta/Elev= 30
  4255.3   131.2  4665.3  117.39  4855.3  108.99  4885.3  106.41  4915.3  107.62
  4935.3   109.3  4945.3  109.59    4979  105.39  4980.5  102.39  5019.4  102.39
  5020.9  105.39    5040  106.34    5230  106.16    5260  106.89    5340  106.05
    5350  106.31    5380  109.04  5458.5  109.72  5708.5  108.85  5908.5  112.36
  5938.5   113.7  5978.5  113.41  6428.5   122.2  6488.5  122.28  6538.5  124.22
  6568.5  123.99  6598.5  125.01  6628.5  124.61  6938.5  130.94  7067.1  133.02
#Mann= 3 , 1 , 0
 4255.30   0.131       0    4979   0.055       0  5020.9   0.131       0
Bank Sta=4979.00,5020.90
Exp/Cntr=0.3,0.1

Type RM Length L Ch R = 1 ,19503.0,497.6,497.6,497.6
BEGIN DESCRIPTION:
Rocky Swamp 39.0
END DESCRIPTION:
#Sta/Elev= 26
  4282.2  131.01  4442.2  126.64  4462.2  125.26  4672.2  118.67  4752.2  118.21
  4892.2  113.84  4932.2  111.13  4942.2  111.97  4952.2  110.84  4972.2   106.9
  4979.1  105.08  4980.6  102.08  5019.4  102.08  5020.9  105.08    5050  107.34
    5120  105.57    5320  108.28    5440  107.78    5890   108.7    6250  115.86
    6460  121.74    6650  126.13    6680  127.26    6690  126.77    6700  125.72
  7051.1  131.06
#Mann= 3 , 1 , 0
 4282.20   0.131       0  4979.1   0.055       0  5020.9   0.131       0
Bank Sta=4979.10,5020.90
Exp/Cntr=0.3,0.1

Type RM Length L Ch R = 1 ,19005.4,400.2,400.2,400.2
BEGIN DESCRIPTION:
Rocky Swamp 38.0
END DESCRIPTION:
#Sta/Elev= 30
    4178  131.44    4308  129.57    4358  126.98    4408  122.47    4568   115.3
    4788  110.99    4888  106.59    4979  104.95  4980.5  101.95  5019.4  101.95
  5020.9  104.95    5040  106.47    5110   105.8    5160  107.19    5290  106.95
    5380  105.64    5710  105.69    5750  104.85    5990  105.72    6070  114.23
    6100  114.87    6130  114.18    6190  116.44    6230   119.2    6390   126.7
    6410  128.56    6480  130.03    6500  129.17    6560   128.6  6755.7  130.71
#Mann= 3 , 1 , 0
 4178.00   0.131       0    4979   0.055       0  5020.9   0.131       0
Bank Sta=4979.00,5020.90
Exp/Cntr=0.3,0.1

Type RM Length L Ch R = 1 ,18605.2,598.8,598.8,598.8
BEGIN DESCRIPTION:
Rocky Swamp 37.0
END DESCRIPTION:
#Sta/Elev= 30
    4012  131.39    4092  129.79    4272  122.64    4322  119.72    4402  118.53
    4422  117.01    4512  115.08    4542  113.35    4572  113.06    4612  111.25
    4772  111.04    4892  108.63    4979  104.85  4980.5  101.85  5019.4  101.85
  5020.9  104.85    5045  106.41    5455  106.34    5555  105.15    5605  105.78
    5615  105.23    5805  104.93    5845  105.98    5945   105.3    6235  106.85
    6275  108.91    6295   111.5    6465  122.93    6635  126.04  6836.3  131.04
#Mann= 3 , 1 , 0
 4012.00   0.131       0    4979   0.055       0  5020.9   0.131       0
Bank Sta=4979.00,5020.90
Exp/Cntr=0.3,0.1

Type RM Length L Ch R = 1 ,18006.4,426.8,426.8,426.8
BEGIN DESCRIPTION:
Rocky Swamp 36.0
END DESCRIPTION:
#Sta/Elev= 30
  2458.6  134.33  2508.6  134.58  2568.6   130.6  2718.6  124.98  2888.6  122.22
  3338.6  120.14  3398.6  117.39  3438.6  119.33  3948.6  114.66  4018.6  111.36
  4068.6  111.52  4188.6   104.7  4268.6  104.11  4418.6  106.37  4558.6  104.71
  4979.1   104.5  4980.6   101.5  5019.4   101.5  5020.9   104.5    5090  105.98
    5210   104.6    5240  105.84    6400  105.85    6470  108.17    6490  111.55
    6550  116.66    6600     116    6650  117.74    6850  128.79  7038.5  132.45
#Mann= 3 , 1 , 0
 2458.60   0.131       0  4979.1   0.055       0  5020.9   0.131       0
Bank Sta=4979.10,5020.90
Exp/Cntr=0.3,0.1

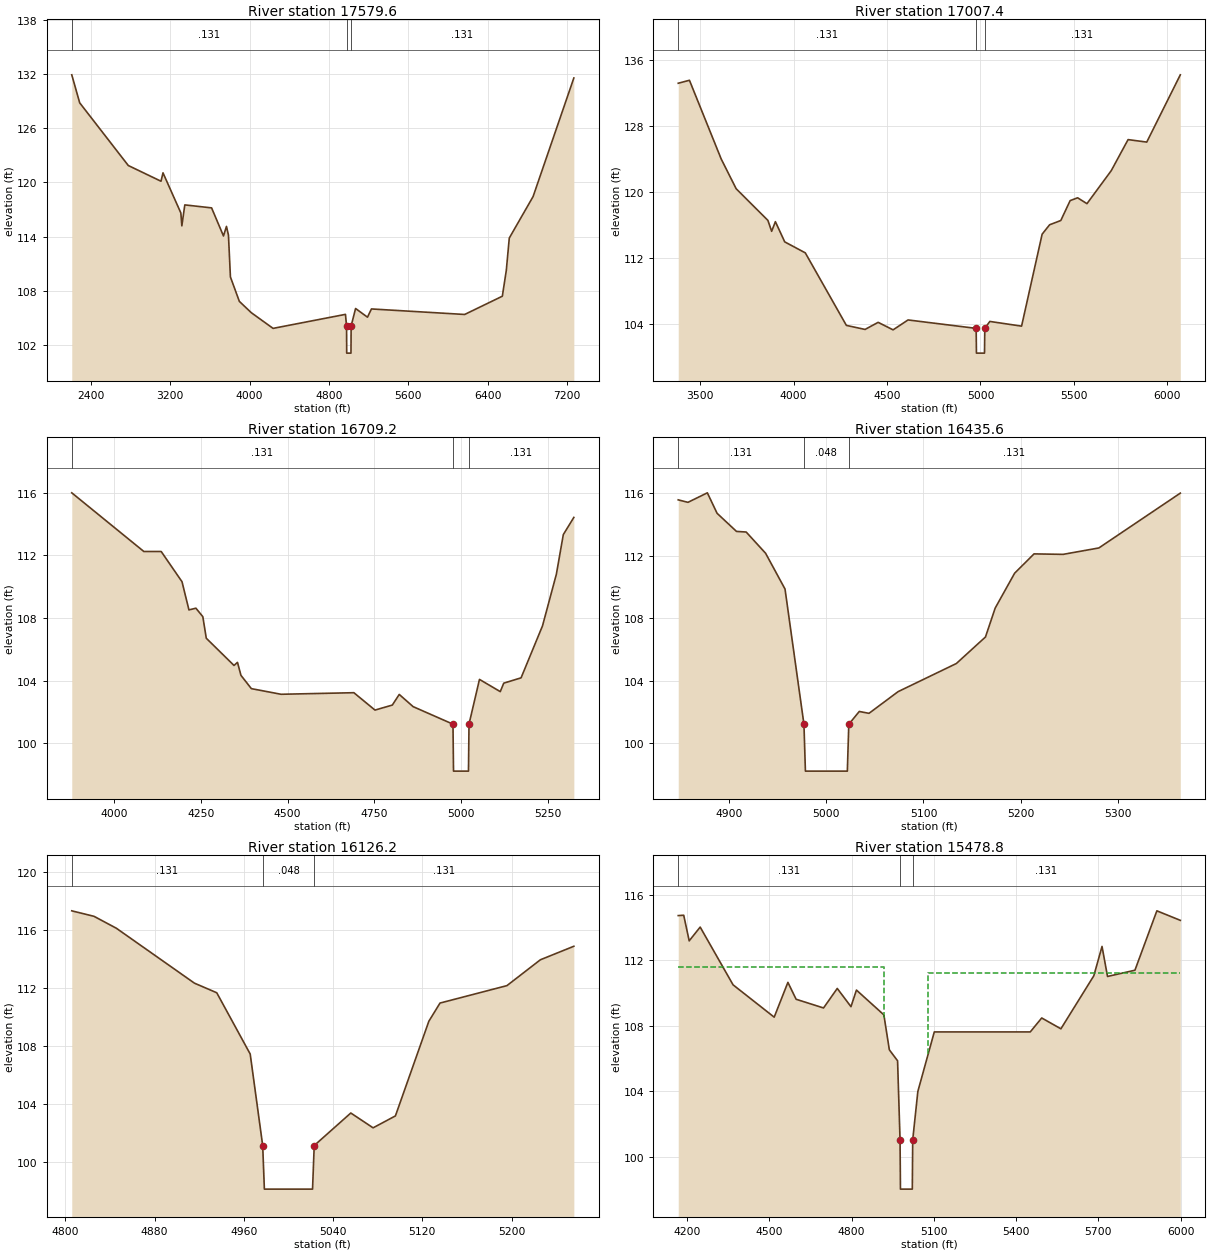
Type RM Length L Ch R = 1 ,17579.6,572.2,572.2,572.2
BEGIN DESCRIPTION:
Rocky Swamp 35.0
END DESCRIPTION:
#Sta/Elev= 30
  2205.9  131.91  2285.9  128.81  2775.9  121.87  3105.9  120.13  3125.9  121.06
  3305.9  116.62  3315.9  115.19  3345.9  117.51  3615.9  117.18  3735.9  114.07
  3765.9  115.13  3785.9  114.18  3805.9  109.53  3895.9  106.83  4015.9  105.58
  4235.9  103.84  4965.9  105.39    4977   104.1  4978.5   101.1  5021.6   101.1
  5023.1   104.1    5068  106.04    5188  105.08    5228  105.99    6168  105.38
    6548   107.4    6588  110.26    6618  113.84    6858  118.43  7269.1  131.56
#Mann= 3 , 1 , 0
 2205.90   0.131       0    4977   0.055       0  5023.1   0.131       0
Bank Sta=4977.00,5023.10
Exp/Cntr=0.3,0.1

Type RM Length L Ch R = 1 ,17007.4,298.2,298.2,298.2
BEGIN DESCRIPTION:
Rocky Swamp 34.0
END DESCRIPTION:
#Sta/Elev= 30
  3382.3  133.14  3442.3   133.5  3612.3  123.96  3692.3  120.36  3862.3  116.52
  3882.3   115.2  3902.3  116.37  3952.3  113.92  4062.3  112.59  4282.3   103.8
  4382.3  103.31  4452.3  104.17  4532.3  103.26  4612.3  104.46  4976.9  103.44
  4978.4  100.44  5021.6  100.44  5023.1  103.44    5050  104.28    5220  103.71
    5330  114.85    5370  115.99    5430  116.51    5480  118.92    5520  119.26
    5570  118.55    5700  122.55    5790  126.31    5890  126.01  6069.6  134.16
#Mann= 3 , 1 , 0
 3382.30   0.131       0  4976.9   0.055       0  5023.1   0.131       0
Bank Sta=4976.90,5023.10
Exp/Cntr=0.3,0.1

Type RM Length L Ch R = 1 ,16709.2,273.6,273.6,273.6
BEGIN DESCRIPTION:
Rocky Swamp 33.0
END DESCRIPTION:
#Sta/Elev= 30
  3877.3     116  4085.3  112.25  4135.3  112.25  4195.3  110.32  4215.3  108.52
  4235.3  108.63  4255.3  108.09  4265.3  106.71  4345.3  104.97  4355.3  105.17
  4365.3  104.34  4395.3  103.49    4481  103.13    4691  103.23  4751.9  102.12
  4801.9  102.44  4821.9  103.12  4861.9  102.34  4976.9  101.22  4978.4   98.22
  5021.6   98.22  5023.1  101.22  5053.3  104.08  5113.3   103.3  5123.3  103.84
  5173.3  104.18  5235.1   107.5  5275.1   110.8  5295.1  113.33  5325.5  114.43
#Mann= 3 , 1 , 0
 3877.30   0.131       0  4976.9   0.048       0  5023.1   0.131       0
Bank Sta=4976.90,5023.10
Exp/Cntr=0.3,0.1

Type RM Length L Ch R = 1 ,16435.6,309.4,309.4,309.4
BEGIN DESCRIPTION:
Rocky Swamp 32.0
END DESCRIPTION:
#Sta/Elev= 23
  4847.4  115.57  4857.4  115.41  4877.4  116.02  4887.4  114.71  4907.4  113.55
  4917.4  113.51  4937.4  112.15  4957.4  109.86  4976.9   101.2  4978.4    98.2
  5021.6    98.2  5023.1   101.2  5033.9  102.02  5043.9   101.9  5073.9  103.29
  5133.9  105.09  5163.9  106.79  5173.9  108.64  5193.9  110.87  5213.9  112.11
  5243.9  112.08  5280.7  112.49  5364.6     116
#Mann= 3 , 1 , 0
 4847.40   0.131       0  4976.9   0.048       0  5023.1   0.131       0
Bank Sta=4976.90,5023.10
Exp/Cntr=0.3,0.1

Type RM Length L Ch R = 1 ,16126.2,647.4,647.4,647.4
BEGIN DESCRIPTION:
Rocky Swamp 31.0
END DESCRIPTION:
#Sta/Elev= 18
  4805.7  117.32  4825.7  116.94  4845.7  116.12  4915.7  112.34  4935.7  111.68
  4965.7  107.46  4976.9  101.16  4978.4   98.16  5021.6   98.16  5023.1  101.16
  5055.9   103.4  5075.9  102.38  5095.9   103.2  5125.9  109.72  5135.9  110.97
  5195.9  112.17  5225.9  113.95  5255.9  114.88
#Mann= 3 , 1 , 0
 4805.70   0.131       0  4976.9   0.048       0  5023.1   0.131       0
Bank Sta=4976.90,5023.10
Exp/Cntr=0.3,0.1

Type RM Length L Ch R = 1 ,15478.8,50,50,50
BEGIN DESCRIPTION:
Upstream Section of Bridge/Culvert/Weir
END DESCRIPTION:
#Sta/Elev= 30
  4167.9  114.72  4187.9  114.74  4207.9  113.18  4247.9  114.02  4367.9   110.5
  4517.9  108.53  4567.9  110.65  4597.9  109.62  4697.9  109.09  4747.9  110.28
  4797.9  109.17  4817.9  110.18  4917.9  108.67  4937.9  106.54  4967.9  105.87
  4976.9  101.05  4978.4   98.05  5021.6   98.05  5023.1  101.05  5041.8     104
  5101.8  107.63  5451.8  107.63  5493.6  108.48  5563.6  107.82  5683.6  111.05
  5713.6  112.84  5733.6  111.01  5833.6  111.39  5913.6  115.01  5999.1  114.43
#Mann= 3 , 1 , 0
 4167.90   0.131       0  4976.9   0.048       0  5023.1   0.131       0
#XS Ineff= 2 , 0
       0    4920   111.6    5080       0   111.2
Bank Sta=4976.90,5023.10
Exp/Cntr=0.5,0.3