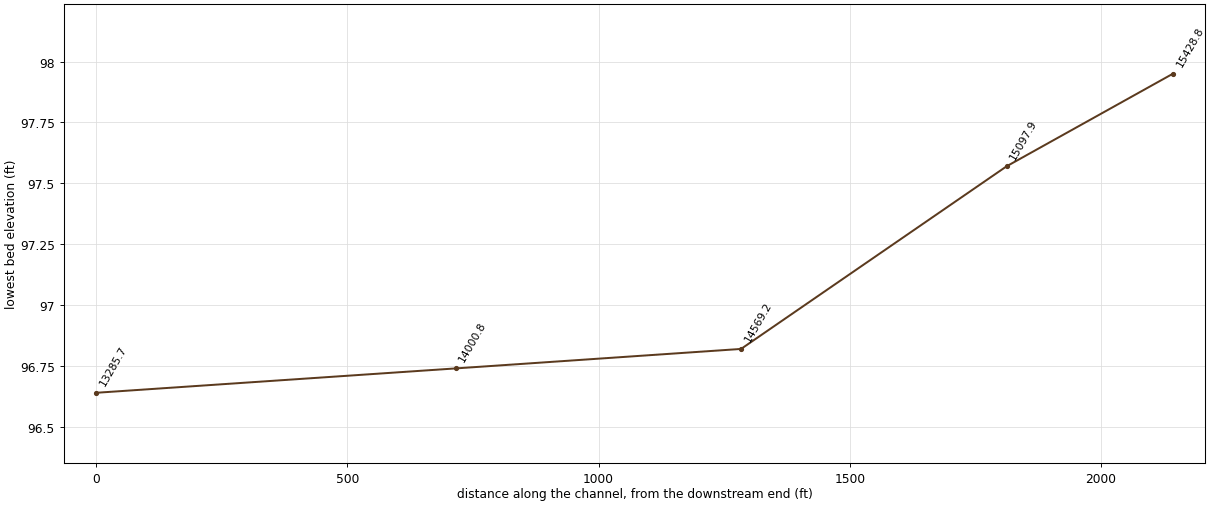
HEC-RAS study 021209_rocky_swamp.prj: Rocky Swamp

--- 021209_rocky_swamp.g01 (geometry) --- (continued)

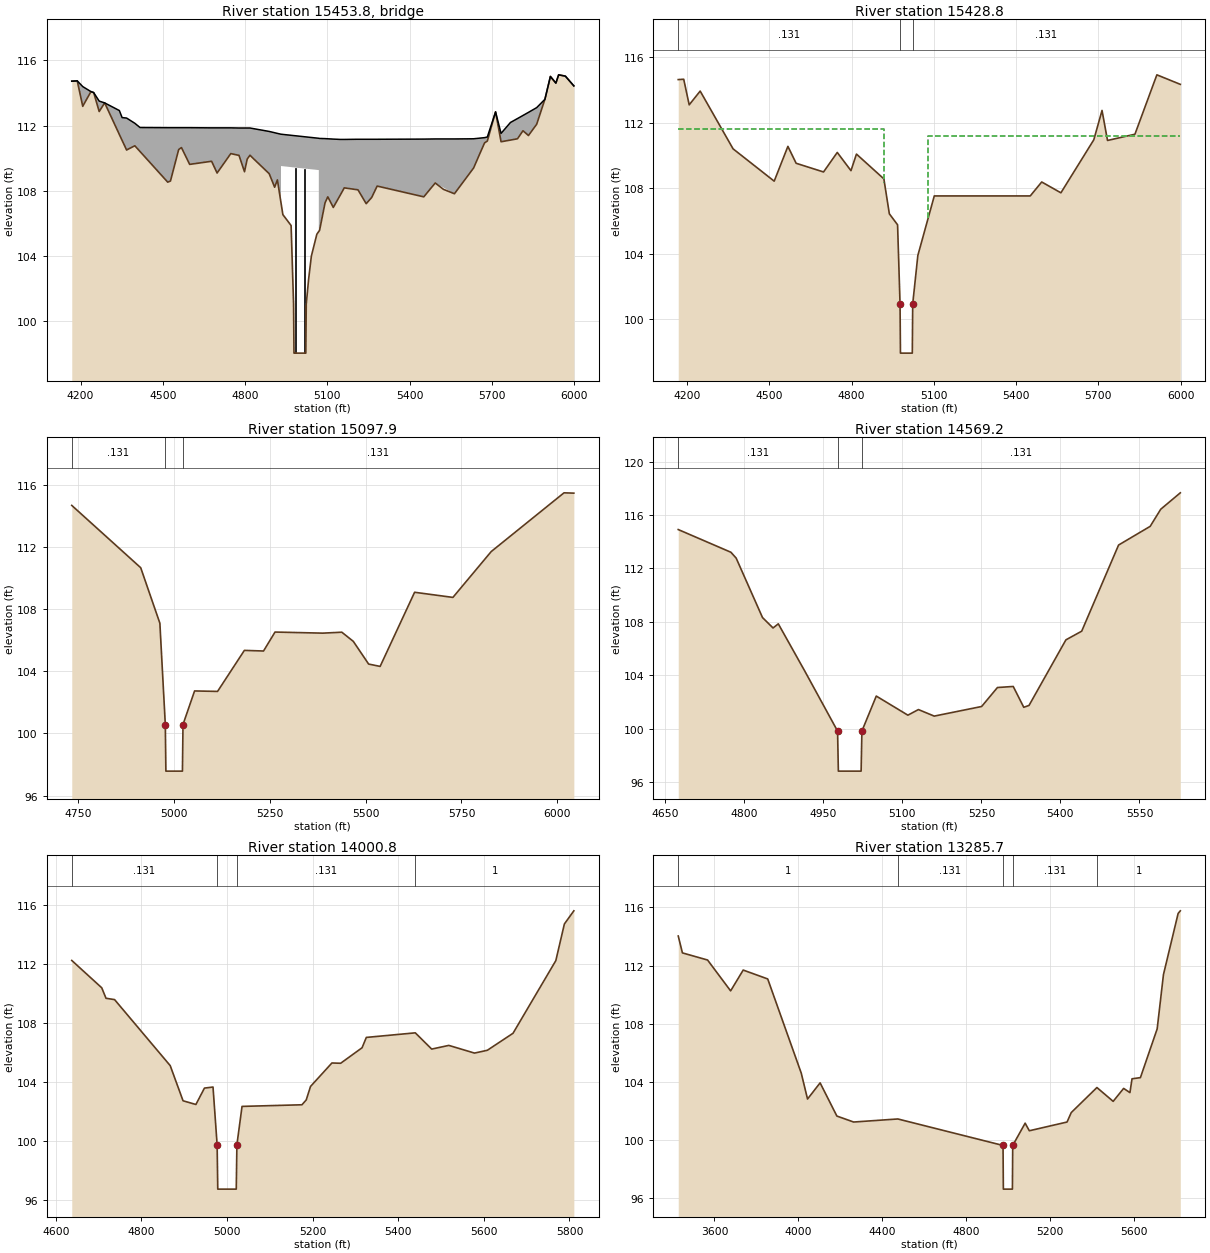
Type RM Length L Ch R = 3 ,15453.8,,,
BEGIN DESCRIPTION:
NC 481-TOR
Structure ID: NC 481
Approximate Survey Structure
END DESCRIPTION:
Bridge Culvert--1,0,-1,-1, 0
Deck Dist Width WeirC Skew NumUp NumDn MinLoCord MaxHiCord MaxSubmerge Is_Ogee
10,30,2.6,, 60, 60,,,0.95,0,1,1,,
  4167.9  4187.9  4207.9  4237.9  4247.9  4267.9  4287.9  4341.5  4351.5  4367.9
  4397.9  4416.8  4517.9  4527.9  4557.9  4567.9  4597.9  4677.9  4697.9  4747.9
  4777.9  4797.9  4807.9  4817.9  4887.9  4907.9  4917.9 4930.91    4931 5068.89
    5069  5071.8  5091.8  5101.8  5121.8  5147.9  5161.8  5211.8  5241.8  5261.8
  5281.8  5451.8  5493.6  5563.6  5633.6  5673.6  5683.6  5713.6  5733.6  5767.9
  5793.6  5813.6  5833.6  5863.6  5893.6  5913.6  5933.6  5943.6  5968.2  5999.1
  114.72  114.74  114.39  114.08  114.02   113.5  113.39  112.92  112.49  112.46
  112.14  111.88  111.87  111.87  111.87  111.87  111.87  111.86  111.86  111.86
  111.85  111.85  111.85  111.85  111.64  111.56  111.52  111.47  111.47  111.22
  111.22  111.21   111.2  111.19  111.17  111.15  111.15  111.16  111.16  111.16
  111.16  111.17  111.18  111.18  111.19  111.26   111.3  112.84  111.52  112.19
  112.43  112.62  112.81   113.1  113.61  115.01   114.6  115.11  115.03  114.43
  114.72  114.74  113.18  114.08  114.02  112.86  113.39  111.45  111.09   110.5
  110.76  110.41  108.53   108.6  110.53  110.65  109.62  109.81  109.09  110.28
  110.17  109.17  109.95  110.18  109.05  108.22  108.67  107.28  109.52  109.27
  105.51  105.58  107.27  107.63  106.98  107.76  108.18  108.06  107.21  107.59
  108.29  107.63  108.48  107.82   109.4  110.94  111.05  112.84  111.01  111.11
  111.19  111.68  111.39  112.08  113.61  115.01   114.6  115.11  115.03  114.43
  4167.9  4187.9  4207.9  4237.9  4247.9  4267.9  4287.9  4341.5  4351.5  4367.9
  4397.9  4416.8  4517.9  4527.9  4557.9  4567.9  4597.9  4677.9  4697.9  4747.9
  4777.9  4797.9  4807.9  4817.9  4887.9  4907.9  4917.9 4930.91    4931 5068.89
    5069  5071.8  5091.8  5101.8  5121.8  5147.9  5161.8  5211.8  5241.8  5261.8
  5281.8  5451.8  5493.6  5563.6  5633.6  5673.6  5683.6  5713.6  5733.6  5767.9
  5793.6  5813.6  5833.6  5863.6  5893.6  5913.6  5933.6  5943.6  5968.2  5999.1
  114.67   114.7  114.39  114.04  113.98   113.5  113.39  112.92  112.49  112.46
  112.14  111.88  111.87  111.87  111.87  111.87  111.87  111.86  111.86  111.86
  111.85  111.85  111.85  111.85  111.64  111.56  111.52  111.47  111.47  111.22
  111.22  111.21   111.2  111.19  111.17  111.15  111.15  111.16  111.16  111.16
  111.16  111.17  111.18  111.18  111.19  111.26   111.3   112.8  111.52  112.19
  112.43  112.62  112.81   113.1  113.57  114.97  114.56  115.07  114.99  114.38
  114.62  114.64  113.08  113.98  113.92  112.76  113.29  111.35  110.99   110.4
  110.66  110.31  108.43   108.5  110.43  110.55  109.52  109.71  108.99  110.18
  110.07  109.07  109.85  110.08  108.95  108.12  108.57  107.18  109.42  109.17
  105.41  105.48  107.17  107.53  106.88  107.66  108.08  107.96  107.11  107.49
  108.19  107.53  108.38  107.72   109.3  110.84  110.95  112.74  110.91  111.01
  111.09  111.58  111.29  111.98  113.51  114.91   114.5  115.01  114.93  114.33
Pier Skew, UpSta & Num, DnSta & Num=,4983.7, 2 ,4983.7, 2 , 0 , 0 , 0 ,,
       2       2
   97.05  110.34
       2       2
   96.95  110.24
Pier Skew, UpSta & Num, DnSta & Num=,5016.2, 2 ,5016.2, 2 , 0 , 0 , 0 ,,
       2       2
   97.05  110.31
       2       2
   96.95  110.21
Abutment Skew #Up #Dn=, 2 , 2
 4930.80 4967.50
  109.52  105.88
 4930.80 4967.50
  109.42  105.78
Abutment Skew #Up #Dn=, 2 , 2
 5032.50 5069.09
  102.69  109.27
 5032.50 5069.09
  102.59  109.17
BR Coef= 1 , 1 , 0 ,1.25, 0 ,,,0.8,0,2,0,
Wspro=,,,, 1 ,,,, 0 ,,,, 0 ,,,,-1 ,-1 ,-1 , 0 , 0 , 0 , 0 , 0
BC Design=,, 0 ,, 0 ,,,,,,
BR U #Sta/Elev= 80
  4167.9  114.72  4187.9  114.74  4207.9  113.18  4211.5  113.29  4237.9  114.08
  4247.9  114.02  4251.5  113.81  4267.9  112.86  4287.9  113.39  4301.5   112.9
  4341.5  111.45  4351.5  111.09  4367.9   110.5  4376.8  110.58  4397.9  110.76
  4416.8  110.41  4517.9  108.53  4527.9   108.6  4557.9  110.53  4567.9  110.65
  4597.9  109.62  4677.9  109.81  4697.9  109.09  4747.9  110.28  4777.9  110.17
  4797.9  109.17  4807.9  109.95  4817.9  110.18  4831.3  109.96  4887.9  109.05
  4907.9  108.22  4917.9  108.67 4930.91  107.28    4931  107.27  4937.9  106.54
  4967.5  105.88  4967.9  105.87  4976.9  101.05  4978.4   98.05    4980   98.05
  5021.6   98.05  5023.1  101.05  5031.8  102.59  5032.5  102.69  5041.8     104
  5061.8  105.34 5068.89  105.51    5069  105.51  5071.8  105.58  5091.8  107.27
  5101.8  107.63  5121.8  106.98  5147.9  107.76  5161.8  108.18  5211.8  108.06
  5241.8  107.21  5261.8  107.59  5281.8  108.29  5451.8  107.63  5493.6  108.48
  5523.6  108.09  5563.6  107.82  5633.6   109.4  5657.9  110.34  5673.6  110.94
  5683.6  111.05  5713.6  112.84  5733.6  111.01  5737.9  111.02  5767.9  111.11
  5793.6  111.19  5813.6  111.68  5833.6  111.39  5863.6  112.08  5893.6  113.61
  5913.6  115.01  5933.6   114.6  5943.6  115.11  5968.2  115.03  5999.1  114.43
BR U #Mann= 3
 4167.90   0.131  4976.9   0.048  5023.1   0.131
BR U Banks=4976.90,5023.10
BR D #Sta/Elev= 80
  4167.9  114.62  4187.9  114.64  4207.9  113.08  4211.5  113.19  4237.9  113.98
  4247.9  113.92  4251.5  113.71  4267.9  112.76  4287.9  113.29  4301.5   112.8
  4341.5  111.35  4351.5  110.99  4367.9   110.4  4376.8  110.48  4397.9  110.66
  4416.8  110.31  4517.9  108.43  4527.9   108.5  4557.9  110.43  4567.9  110.55
  4597.9  109.52  4677.9  109.71  4697.9  108.99  4747.9  110.18  4777.9  110.07
  4797.9  109.07  4807.9  109.85  4817.9  110.08  4831.3  109.86  4887.9  108.95
  4907.9  108.12  4917.9  108.57 4930.91  107.18    4931  107.17  4937.9  106.44
  4967.5  105.78  4967.9  105.77  4976.9  100.95  4978.4   97.95    4980   97.95
  5021.6   97.95  5023.1  100.95  5031.8  102.49  5032.5  102.59  5041.8   103.9
  5061.8  105.24 5068.89  105.41    5069  105.41  5071.8  105.48  5091.8  107.17
  5101.8  107.53  5121.8  106.88  5147.9  107.66  5161.8  108.08  5211.8  107.96
  5241.8  107.11  5261.8  107.49  5281.8  108.19  5451.8  107.53  5493.6  108.38
  5523.6  107.99  5563.6  107.72  5633.6   109.3  5657.9  110.24  5673.6  110.84
  5683.6  110.95  5713.6  112.74  5733.6  110.91  5737.9  110.92  5767.9  111.01
  5793.6  111.09  5813.6  111.58  5833.6  111.29  5863.6  111.98  5893.6  113.51
  5913.6  114.91  5933.6   114.5  5943.6  115.01  5968.2  114.93  5999.1  114.33
BR D #Mann= 3
 4167.90   0.131  4976.9   0.048  5023.1   0.131
BR D Banks=4976.90,5023.10

Type RM Length L Ch R = 1 ,15428.8,330.9,330.9,330.9
BEGIN DESCRIPTION:
Downstream Section of Bridge/Culvert/Weir
END DESCRIPTION:
#Sta/Elev= 30
  4167.9  114.62  4187.9  114.64  4207.9  113.08  4247.9  113.92  4367.9   110.4
  4517.9  108.43  4567.9  110.55  4597.9  109.52  4697.9  108.99  4747.9  110.18
  4797.9  109.07  4817.9  110.08  4917.9  108.57  4937.9  106.44  4967.9  105.77
  4976.9  100.95  4978.4   97.95  5021.6   97.95  5023.1  100.95  5041.8   103.9
  5101.8  107.53  5451.8  107.53  5493.6  108.38  5563.6  107.72  5683.6  110.95
  5713.6  112.74  5733.6  110.91  5833.6  111.29  5913.6  114.91  5999.1  114.33
#Mann= 3 , 1 , 0
 4167.90   0.131       0  4976.9   0.048       0  5023.1   0.131       0
#XS Ineff= 2 , 0
       0    4920   111.6    5080       0   111.2
Bank Sta=4976.90,5023.10
Exp/Cntr=0.5,0.3

Type RM Length L Ch R = 1 ,15097.9,528.7,528.7,528.7
BEGIN DESCRIPTION:
Rocky Swamp 30.0
END DESCRIPTION:
#Sta/Elev= 22
  4732.7  114.67  4912.7  110.66  4962.7  107.09  4976.9  100.57  4978.4   97.57
  5021.6   97.57  5023.1  100.57  5053.3  102.73  5113.3   102.7  5183.3  105.34
  5233.3   105.3  5263.3  106.52  5387.7  106.45  5437.7  106.51  5467.7  105.92
  5507.7  104.46  5537.7  104.31  5627.7  109.08  5727.7  108.75  5827.7   111.7
  6017.7  115.48  6043.4  115.46
#Mann= 3 , 1 , 0
 4732.70   0.131       0  4976.9   0.048       0  5023.1   0.131       0
Bank Sta=4976.90,5023.10
Exp/Cntr=0.3,0.1

Type RM Length L Ch R = 1 ,14569.2,568.4,568.4,568.4
BEGIN DESCRIPTION:
Rocky Swamp 29.0
END DESCRIPTION:
#Sta/Elev= 26
  4674.4  114.91  4774.4  113.21  4784.4  112.77  4834.4  108.32  4854.4  107.54
  4864.4  107.85  4914.4  104.33  4976.9   99.82  4978.4   96.82  5021.6   96.82
  5023.1   99.82  5050.4  102.44  5110.4  101.01  5130.4  101.43  5160.4  100.94
  5250.4  101.66  5280.4  103.08  5310.4  103.16  5330.4   101.6  5340.4  101.74
  5410.4  106.65  5440.4   107.3  5510.4  113.75  5570.4  115.15  5590.4  116.43
  5627.6  117.66
#Mann= 3 , 1 , 0
 4674.40   0.131       0  4976.9   0.048       0  5023.1   0.131       0
Bank Sta=4976.90,5023.10
Exp/Cntr=0.3,0.1

Type RM Length L Ch R = 1 ,14000.8,715.1,715.1,715.1
BEGIN DESCRIPTION:
Rocky Swamp 28.0
END DESCRIPTION:
#Sta/Elev= 30
  4637.3  112.22  4707.3  110.37  4717.3  109.66  4737.3  109.57  4867.3   105.1
  4897.3  102.72  4927.3  102.47  4947.3  103.58  4967.3  103.65  4976.9   99.74
  4978.4   96.74  5021.6   96.74  5023.1   99.74  5035.1  102.34  5175.1  102.45
  5185.1  102.78  5195.1  103.69  5245.1  105.28  5265.5  105.26  5315.5  106.31
  5325.5  107.01  5439.9  107.32  5478.2  106.22  5518.2  106.47  5578.2  105.95
  5608.2  106.14  5668.2  107.29  5768.2  112.21  5788.2  114.69  5810.3  115.58
#Mann= 4 , 1 , 0
 4637.30   0.131       0  4976.9   0.048       0  5023.1   0.131       0
  5439.9       1       0
Bank Sta=4976.90,5023.10
Exp/Cntr=0.3,0.1

Type RM Length L Ch R = 1 ,13285.7,0,0,0
BEGIN DESCRIPTION:
Rocky Swamp 27.0
END DESCRIPTION:
#Sta/Elev= 30
    3427  114.03    3447  112.87    3567  112.38    3677  110.26    3737  111.69
    3854  111.08    4014  104.61    4044  102.83    4104  103.94    4184  101.66
    4264  101.25  4474.9  101.46  4976.9   99.64  4978.4   96.64  5021.6   96.64
  5023.1   99.64  5082.4  101.17  5102.4  100.65  5282.4  101.25  5302.4   101.9
  5424.9  103.62  5502.4  102.67  5552.4  103.56  5582.4  103.27  5592.4  104.22
  5632.4   104.3  5712.4  107.65  5742.4  111.38  5812.4  115.58  5822.8  115.76
#Mann= 5 , 1 , 0
 3427.00       1       0  4474.9   0.131       0  4976.9   0.048       0
  5023.1   0.131       0  5424.9       1       0
Bank Sta=4976.90,5023.10
Exp/Cntr=0.3,0.1

Chan Stop Cuts=-1