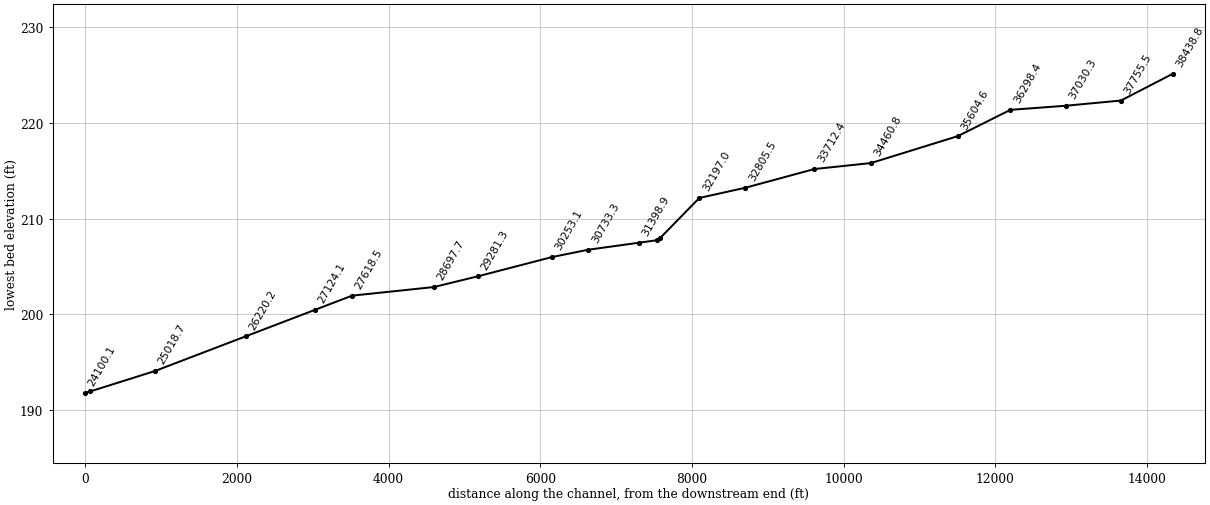
--- 020911_big_peachtree_creek.prj (project) ---

Proj Title=BIG_PEACHTREE_CREEK
Current Plan=p01
Default Exp/Contr=.3,.1
English Units
Geom File=g01
Flow File=f01
Plan File=p01
Y Axis Title=Elevation
X Axis Title(PF)=Main Channel Distance
X Axis Title(XS)=Station
BEGIN DESCRIPTION:
STONY-CREEK
END DESCRIPTION:
DSS Export Rating Curves= 0
DSS Export Rating Curve Sorted= 0
DSS Export Volume Flow Curves= 0
DXF OffsetX= 0
DXF OffsetY= 0
DXF ScaleX= 1
DXF ScaleY= 10

--- 020911_big_peachtree_creek.p01 (plan) ---

Plan Title=BIG_PEACHTREE_CREEK
Version=Version 3.0.1  Mar 2001
Short Identifier=Base Plan
Geom File=g01
Flow File=f01
Subcritical Flow
K Sum by GR= 0
Std Step Tol= 0.01
Critical Tol= 0.01
Num of Std Step Trials= 20
Max Error Tol= 0.3
Flow Tol Ratio= 0.001
Split Flow NTrial= 30
Split Flow Tol= 0.02
Split Flow Ratio= 0.02
Log Output Level= 0
Friction Slope Method= 1
Unsteady Friction Slope Method= 2
Parabolic Critical Depth
Global Vel Dist= 0 , 0 , 0
Global Log Level= 0
CheckData=True
Encroach Param=-1 ,10,10, 2
Encroach River=Main Stem
Encroach Reach=Reach - 1
Encroach Node=38438.8
       4      .8
Encroach Node=37755.5
       4      .8
Encroach Node=37030.3
       4      .8
Encroach Node=36298.4
       4      .8
Encroach Node=35604.6
       4      .8
Encroach Node=34460.8
       4      .8
Encroach Node=33712.4
       1    4964    5050
Encroach Node=32805.5
       4      .8
Encroach Node=32197.0
       4      .8
Encroach Node=31684.2
       1    4955    5042
Encroach Node=31664.2
       1    4955    5042
Encroach Node=31644.2
       1    4955    5042
Encroach Node=31398.9
       4      .8
Encroach Node=30733.3
       4      .8
Encroach Node=30253.1
       1    4671    5011
Encroach Node=29281.3
       4      .8
Encroach Node=28697.7
       4      .8
Encroach Node=27618.5
       4      .8
Encroach Node=27124.1
       4      .8
Encroach Node=26220.2
       4      .8
Encroach Node=25018.7
       4      .8
Encroach Node=24170.1
       4      .8
Encroach Node=24135.1
       4      .8
Encroach Node=24100.1
       4      .8
Encroach Node=23354.7
       4      .8
Encroach Node=22250.6
       4      .8
Encroach Node=21577.5
       4      .8
Encroach Node=20788.7
       4      .8
Encroach Node=20766.2
       4      .8
Encroach Node=20743.7
       4      .8
Encroach Node=20528.5
       4      .8
Encroach Node=19100.6
       4      .8
Encroach Node=17838.8
       4      .8
Encroach Node=17204.0
       4      .8
Encroach Node=16203.7
       4      .8
Encroach Node=14659.1
       4      .8
Encroach Node=14003.3
       4      .8
Encroach Node=12854.4
       4      .8
Encroach Node=11935.9
       4      .8
Encroach Node=10922.0
       1    4860    5055
Encroach Node=10899.5
       1    4860    5055
Encroach Node=10877.0
       1    4860    5055
Encroach Node=10525.4
       4      .7
Encroach Node=9392.5
       4      .7
Encroach Node=7586.1
       4      .7
Encroach Node=6213.3
       4      .7
Encroach Node=5054.5
       4      .7
Encroach Node=3671.5
       4      .7
Encroach Node=2091.0
       4     2.5
Encroach Node=641.6
       4     2.5
Encroach Node=0.0
       1    4806    5100
Computation Interval=1HOUR
Output Interval=1HOUR
Run HTab= 0
Run UNet= 0
Run PostProcess= 0
UNET Theta= 1
UNET ZTol= 0.02
UNET ZSATol= 0.1
UNET MxIter= 20
UNET MaxInSteps= 20
UNET DtIC= 0
UNET DtMin= 0
UNET MaxCRTS= 20
UNET WFStab= 2
UNET SFStab= 1
UNET WFX= 1
UNET SFX= 1
UNET Convert EG Bridges=-1
UNET Use Existing IB Tables=-1
Instantaneous Interval=1HOUR
Write IC File= 0
Write Velocity= 0
Write Detailed= 0

--- 020911_big_peachtree_creek.f01 (steady flow) ---

Flow Title=BIG_PEACHTREE_CREEK
Version=Version 3.0.1  Mar 2001
Number of Profiles= 2
Profile Names=100-YEAR,AFW
River Rch & RM=Main Stem,Reach - 1       ,38438.8
    1921    1921
River Rch & RM=Main Stem,Reach - 1       ,36298.4
    2336    2336
River Rch & RM=Main Stem,Reach - 1       ,32805.5
    2415    2415
River Rch & RM=Main Stem,Reach - 1       ,30253.1
    2559    2559
River Rch & RM=Main Stem,Reach - 1       ,27618.5
    3113    3113
River Rch & RM=Main Stem,Reach - 1       ,22250.6
    3415    3415
River Rch & RM=Main Stem,Reach - 1       ,20788.7
    4137    4137
River Rch & RM=Main Stem,Reach - 1       ,17838.8
    4394    4394
River Rch & RM=Main Stem,Reach - 1       ,12854.4
    4840    4840
River Rch & RM=Main Stem,Reach - 1       ,9392.5
    5035    5035
River Rch & RM=Main Stem,Reach - 1       ,3671.5
    6596    6596
River Rch & RM=Main Stem,Reach - 1       ,0.01
    8486    8486
Boundary for River Rch & Prof#=Main Stem,Reach - 1       , 1
Up Type= 0
Dn Type= 1
Dn Known WS=182.17
Boundary for River Rch & Prof#=Main Stem,Reach - 1       , 2
Up Type= 0
Dn Type= 1
Dn Known WS=182.46
DSS Import GetInterval= 0
DSS Import GetPeak= 0
DSS Import FillOption= 0

--- 020911_big_peachtree_creek.g01 (geometry) ---

Geom Title=Geom 01 by CodeH2 for Windows
Version=Version 3.0.1  Mar 2001

River Reach=Main Stem       ,Reach - 1
Reach XY= 2
              .5             .95              .5             .05

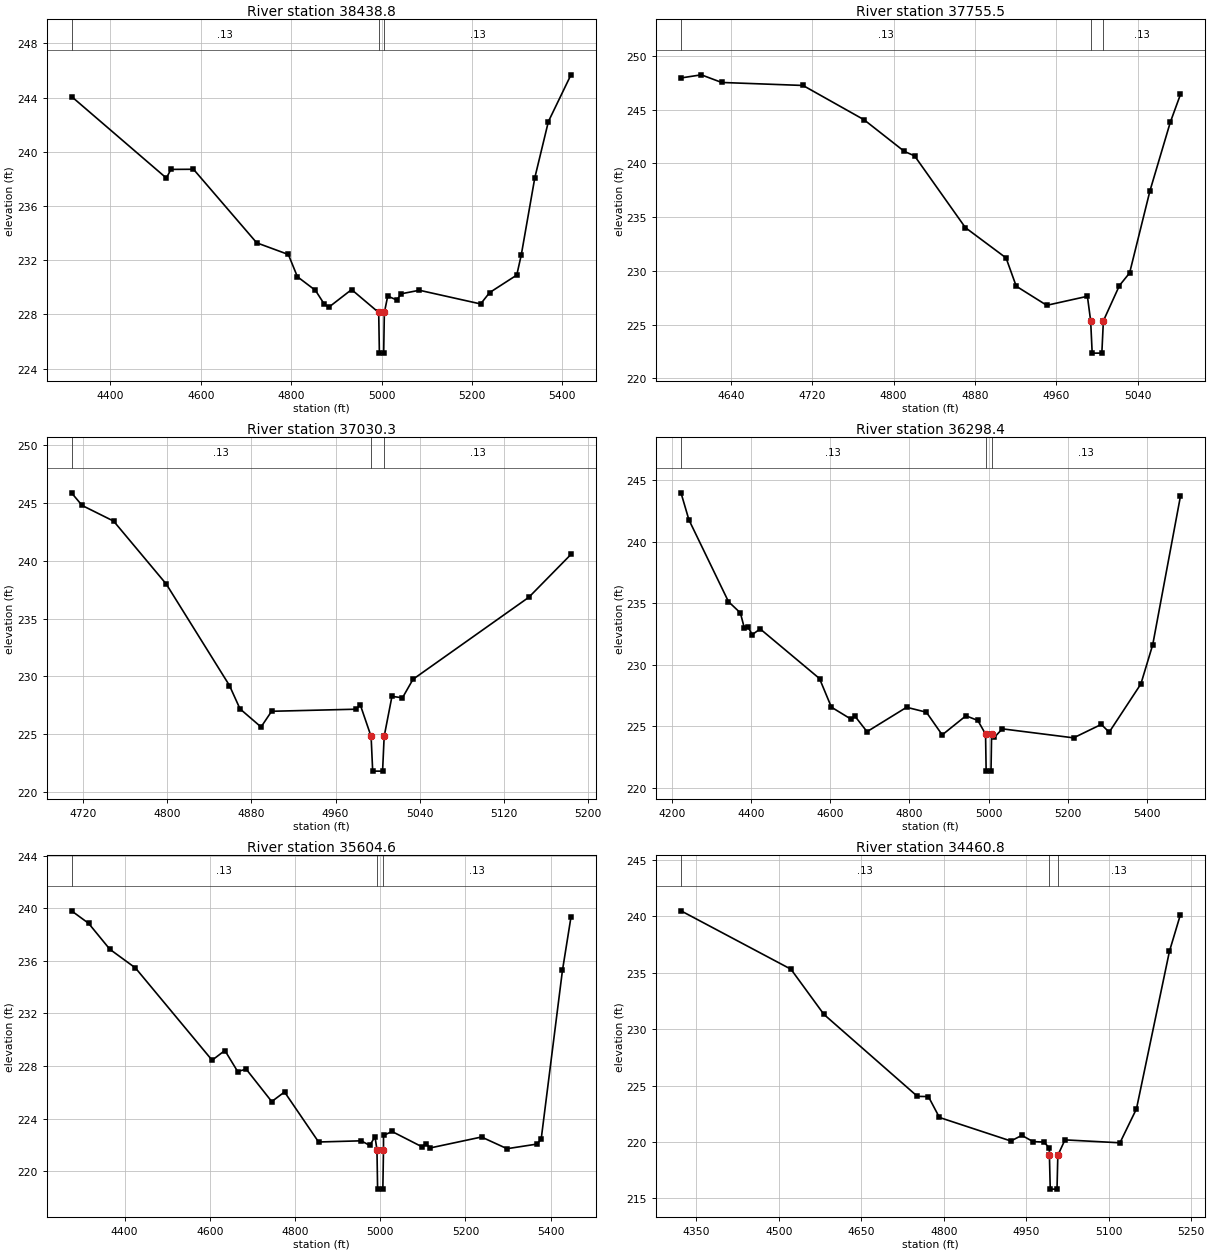
Type RM Length L Ch R = 1 ,38438.8 ,683.3,683.3,683.3
BEGIN DESCRIPTION:
Big Peachtree Creek 38.0
END DESCRIPTION:
#Sta/Elev= 27
  4313.8  244.08  4523.8  238.06  4533.8   238.7  4583.8  238.71  4723.8  233.28
  4793.8  232.42  4813.8  230.78  4853.8  229.77  4873.8  228.73  4883.8  228.54
  4933.8  229.83  4993.7  228.14  4993.8  228.14  4995.3  225.14  5004.8  225.14
  5006.3  228.14  5013.8  229.35  5033.8  229.06  5043.8  229.52  5083.8  229.78
  5219.4  228.77  5239.4  229.61  5299.4   230.9  5309.4  232.39  5339.4  238.09
  5369.4  242.23  5419.4  245.68
#Mann= 3 , 1 , 0
  4313.8     .13       0  4993.7    .044       0  5006.3     .13       0
Bank Sta=4993.7,5006.3
XS Rating Curve= 0
Exp/Cntr=.3,.1

Type RM Length L Ch R = 1 ,37755.5 ,725.2,725.2,725.2
BEGIN DESCRIPTION:
Big Peachtree Creek 37.0
END DESCRIPTION:
#Sta/Elev= 21
  4590.9  247.95  4610.9  248.24  4630.9  247.53  4710.9  247.25  4770.9  244.06
  4810.6  241.11  4820.6   240.7  4870.6  234.02  4910.6   231.2  4920.6  228.57
  4950.6  226.79  4990.6  227.63  4993.8  225.34  4995.3  222.34  5004.8  222.34
  5006.3  225.34  5022.1  228.63  5032.1   229.8  5052.1  237.44  5072.1  243.82
  5082.1  246.41
#Mann= 3 , 1 , 0
  4590.9     .13       0  4993.8    .044       0  5006.3     .13       0
Bank Sta=4993.8,5006.3
XS Rating Curve= 0
Exp/Cntr=.3,.1

Type RM Length L Ch R = 1 ,37030.3 ,731.9,731.9,731.9
BEGIN DESCRIPTION:
Big Peachtree Creek 36.0
END DESCRIPTION:
#Sta/Elev= 19
  4709.3  245.89  4719.3   244.8  4749.3  243.44  4799.3  237.99  4859.3  229.21
  4869.3  227.19  4889.3  225.62  4899.3  226.98  4979.3  227.16  4983.6  227.52
  4993.8   224.8  4995.3   221.8  5004.7   221.8  5006.2   224.8  5013.6  228.27
  5023.6  228.15  5033.6  229.75  5143.6  236.85  5183.6  240.56
#Mann= 3 , 1 , 0
  4709.3     .13       0  4993.8    .044       0  5006.2     .13       0
Bank Sta=4993.8,5006.2
XS Rating Curve= 0
Exp/Cntr=.3,.1

Type RM Length L Ch R = 1 ,36298.4 ,693.8,693.8,693.8
BEGIN DESCRIPTION:
Big Peachtree Creek 35.0
END DESCRIPTION:
#Sta/Elev= 30
  4222.9  243.95  4242.9  241.76  4342.9  235.12  4372.9  234.21  4382.9  232.99
  4392.9  233.03  4402.9  232.44  4422.9  232.91  4572.9  228.88  4602.9  226.56
  4652.9  225.58  4662.9  225.81  4692.9  224.57  4792.9  226.55  4842.9  226.15
  4882.9  224.31  4942.9  225.86  4972.9  225.48  4992.4  224.37  4993.9  221.37
  5006.2  221.37  5007.7  224.37  5014.8  224.12  5034.8   224.8  5214.8  224.07
  5284.8  225.16  5304.8  224.53  5384.8  228.44  5414.8  231.63  5484.8  243.67
#Mann= 3 , 1 , 0
  4222.9     .13       0  4992.4    .044       0  5007.7     .13       0
Bank Sta=4992.4,5007.7
XS Rating Curve= 0
Exp/Cntr=.3,.1

Type RM Length L Ch R = 1 ,35604.6 ,1143.8,1143.8,1143.8
BEGIN DESCRIPTION:
Big Peachtree Creek 34.0
END DESCRIPTION:
#Sta/Elev= 29
  4275.3  239.82  4315.3  238.87  4365.3  236.89  4425.3  235.47  4605.3  228.44
  4635.3  229.18  4665.3  227.58  4685.3  227.76  4745.3  225.29  4775.3  226.02
  4855.3  222.21  4955.3   222.3  4975.3  221.95  4987.7  222.61  4992.3  221.62
  4993.8  218.62  5006.1  218.62  5007.6  221.62  5007.7  222.71  5027.7  223.01
  5097.7  221.85  5107.7  222.06  5117.7  221.76  5237.7  222.59  5297.7   221.7
  5367.7  222.05  5377.7  222.41  5427.7  235.28  5447.7  239.34
#Mann= 3 , 1 , 0
  4275.3     .13       0  4992.3    .044       0  5007.6     .13       0
Bank Sta=4992.3,5007.6
XS Rating Curve= 0
Exp/Cntr=.3,.1

Type RM Length L Ch R = 1 ,34460.8 ,748.4,748.4,748.4
BEGIN DESCRIPTION:
Big Peachtree Creek 33.0
END DESCRIPTION:
#Sta/Elev= 20
  4322.2   240.5  4522.2  235.32  4582.2  231.31  4752.2  224.04  4772.2  224.02
  4792.2  222.17  4922.2  220.08  4942.2  220.58  4962.2  220.03  4982.2  219.98
  4992.2  219.47  4992.3  218.81  4993.8  215.81  5006.1  215.81  5007.6  218.81
  5020.6  220.18  5120.6  219.92  5150.6  222.93  5210.6  236.91  5230.6  240.17
#Mann= 3 , 1 , 0
  4322.2     .13       0  4992.3    .044       0  5007.6     .13       0
Bank Sta=4992.3,5007.6
XS Rating Curve= 0
Exp/Cntr=.3,.1

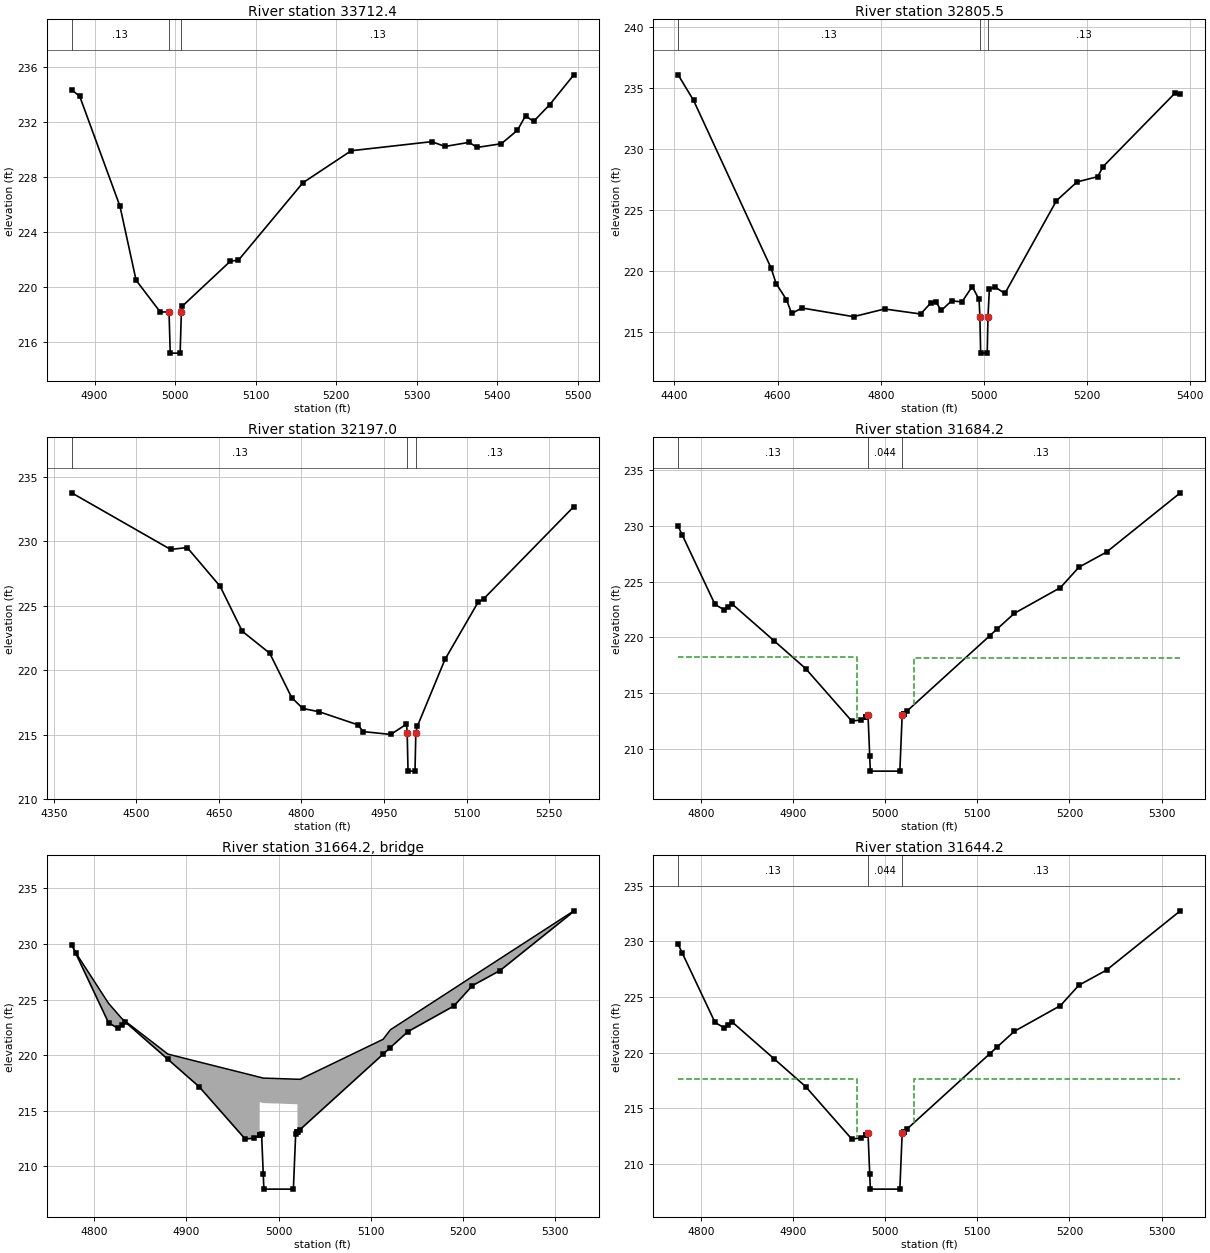
Type RM Length L Ch R = 1 ,33712.4 ,906.9,906.9,906.9
BEGIN DESCRIPTION:
Big Peachtree Creek 32.0
END DESCRIPTION:
#Sta/Elev= 24
  4871.5  234.33  4881.5  233.86  4931.5  225.86  4951.5  220.48  4981.5  218.17
  4992.4  218.18  4993.9  215.18  5006.2  215.18  5007.7  218.18  5008.6  218.58
  5068.6  221.87  5078.6  221.94  5158.6  227.57  5218.6   229.9  5318.6  230.56
    5335  230.21    5365  230.51    5375  230.14    5405  230.41    5425  231.39
    5435  232.44    5445  232.03    5465  233.25    5495  235.42
#Mann= 3 , 1 , 0
  4871.5     .13       0  4992.4    .044       0  5007.7     .13       0
Bank Sta=4992.4,5007.7
XS Rating Curve= 0
Exp/Cntr=.3,.1

Type RM Length L Ch R = 1 ,32805.5 ,608.5,608.5,608.5
BEGIN DESCRIPTION:
Big Peachtree Creek 31.0
END DESCRIPTION:
#Sta/Elev= 30
  4407.3  236.05  4437.3  233.95  4587.3  220.22  4597.3  218.93  4617.3  217.61
  4627.3  216.48  4647.3  216.93  4747.3  216.22  4807.3  216.85  4877.3  216.44
  4897.3  217.36  4907.3   217.4  4917.3  216.73  4937.3  217.52  4957.3  217.43
  4977.3  218.69  4990.5  217.63  4992.1  216.23  4993.6  213.23  5006.3  213.23
  5007.8  216.23  5010.5  218.45  5020.5  218.68  5040.5  218.12  5140.5  225.73
  5180.5  227.27  5220.5   227.7  5230.5  228.51  5370.5  234.56  5380.5  234.45
#Mann= 3 , 1 , 0
  4407.3     .13       0  4992.1    .044       0  5007.8     .13       0
Bank Sta=4992.1,5007.8
XS Rating Curve= 0
Exp/Cntr=.3,.1

Type RM Length L Ch R = 1 ,32197.0 ,512.8,512.8,512.8
BEGIN DESCRIPTION:
Big Peachtree Creek 30.0
END DESCRIPTION:
#Sta/Elev= 22
  4382.3  233.78  4562.3  229.38  4592.3  229.53  4652.3  226.51  4692.3  223.03
  4742.3  221.32  4782.3  217.87  4802.3  217.03  4832.3  216.77  4902.3  215.76
  4912.3  215.23  4962.3  215.01  4990.9  215.81  4992.2  215.16  4993.7  212.16
  5006.4  212.16  5007.9  215.16  5010.9  215.67  5060.9  220.84  5120.9  225.27
  5130.9  225.53  5295.1  232.71
#Mann= 3 , 1 , 0
  4382.3     .13       0  4992.2    .044       0  5007.9     .13       0
Bank Sta=4992.2,5007.9
XS Rating Curve= 0
Exp/Cntr=.3,.1

Type RM Length L Ch R = 1 ,31684.2 ,40,40,40
BEGIN DESCRIPTION:
Upstream Section of Bridge/Culvert/Weir
END DESCRIPTION:
#Sta/Elev= 29
  4775.5  229.99  4779.9  229.22  4815.5  222.97  4825.5  222.48  4829.9  222.77
  4833.8  223.03  4879.9  219.68  4913.8  217.21  4963.8   212.5  4973.8  212.59
 4979.41  212.89  4979.5  212.89  4979.6   212.9  4981.5     213  4983.3   209.4
    4984     208    5016     208  5018.5     213  5020.3  213.14 5020.39  213.14
  5020.5  213.15  5023.3  213.36  5113.3  220.14  5121.2  220.74  5140.2  222.17
  5190.2  224.48  5210.2  226.31  5240.2  227.67  5320.2  232.99
#Mann= 3 , 1 , 0
  4775.5     .13       0  4981.5    .044       0  5018.5     .13       0
#XS Ineff= 2 , 0
       0    4969  218.25    5031       0  218.12
Permanent Ineff=
       F       F
Bank Sta=4981.5,5018.5
XS Rating Curve= 0
Exp/Cntr=.5,.3

Type RM Length L Ch R = 3 ,31664.2 ,,,
BEGIN DESCRIPTION:
Gardner Rd_2-TOR
Structure ID: Gardner Rd_2-Bridge
Approximate Survey Structure
END DESCRIPTION:
Bridge Culvert--1,0,-1,-1, 0
Deck Dist Width WeirC Skew NumUp NumDn MinLoCord MaxHiCord MaxSubmerge Is_Ogee
10,20,2.6,0, 29, 29, , , .95, 0, 1,1,,
  4775.5  4779.9  4815.5  4825.5  4829.9  4833.8  4879.9  4913.8  4963.8  4973.8
 4979.41  4979.5  4979.6  4981.5  4983.3    4984    5016  5018.5  5020.3 5020.39
  5020.5  5023.3  5113.3  5121.2  5140.2  5190.2  5210.2  5240.2  5320.2
  229.99  229.23  224.67  223.72   223.3  223.05   220.1  219.39  218.35  218.14
  218.02  218.02  218.02  217.98  217.94  217.94  217.85  217.84  217.84  217.84
  217.84  217.83  221.43  222.29  223.31     226  227.08  228.69  232.99
  229.94  229.17  222.92  222.43  222.72  222.98  219.63  217.16  212.45  212.54
  212.84  215.77  215.77  215.73  215.69  215.69   215.6  215.59  215.59  215.59
   213.1  213.31  220.09  220.69  222.12  224.43  226.26  227.62  232.94
  4775.5  4779.9  4815.5  4825.5  4829.9  4833.8  4879.9  4913.8  4963.8  4973.8
 4979.41  4979.5  4979.6  4981.5  4983.3    4984    5016  5018.5  5020.3 5020.39
  5020.5  5023.3  5113.3  5121.2  5140.2  5190.2  5210.2  5240.2  5320.2
  229.99  229.23  224.67  223.72   223.3  223.05   220.1  219.39  218.35  218.14
  218.02  218.02  218.02  217.98  217.94  217.94  217.85  217.84  217.84  217.84
  217.84  217.83  221.43  222.29  223.31     226  227.08  228.69  232.99
  229.79  229.02  222.77  222.28  222.57  222.83  219.48  217.01   212.3  212.39
  212.69  215.62  215.62  215.58  215.54  215.54  215.45  215.44  215.44  215.44
  212.95  213.16  219.94  220.54  221.97  224.28  226.11  227.47  232.79
BR Coef= 1 , 1 , 0 ,1.25, 0 ,,,.8,0,2,0,
WSPro=,,,, 1 ,,,, 0 ,,,, 0 ,,,,-1 ,-1 ,-1 , 0 , 0 , 0 , 0 , 0
BR U #Sta/Elev= 29
  4775.5  229.94  4779.9  229.17  4815.5  222.92  4825.5  222.43  4829.9  222.72
  4833.8  222.98  4879.9  219.63  4913.8  217.16  4963.8  212.45  4973.8  212.54
 4979.41  212.84  4979.5  212.84  4979.6  212.85  4981.5  212.95  4983.3  209.35
    4984  207.95    5016  207.95  5018.5  212.95  5020.3  213.09 5020.39  213.09
  5020.5   213.1  5023.3  213.31  5113.3  220.09  5121.2  220.69  5140.2  222.12
  5190.2  224.43  5210.2  226.26  5240.2  227.62  5320.2  232.94
BR U #Mann= 3
  4775.5     .13  4981.5    .044  5018.5     .13
BR U Banks=4981.5,5018.5
BR D #Sta/Elev= 29
  4775.5  229.79  4779.9  229.02  4815.5  222.77  4825.5  222.28  4829.9  222.57
  4833.8  222.83  4879.9  219.48  4913.8  217.01  4963.8   212.3  4973.8  212.39
 4979.41  212.69  4979.5  212.69  4979.6   212.7  4981.5   212.8  4983.3   209.2
    4984   207.8    5016   207.8  5018.5   212.8  5020.3  212.94 5020.39  212.94
  5020.5  212.95  5023.3  213.16  5113.3  219.94  5121.2  220.54  5140.2  221.97
  5190.2  224.28  5210.2  226.11  5240.2  227.47  5320.2  232.79
BR D #Mann= 3
  4775.5     .13  4981.5    .044  5018.5     .13
BR D Banks=4981.5,5018.5
BC Design=,, 0 ,, 0 ,,,,,,

Type RM Length L Ch R = 1 ,31644.2 ,245.3,245.3,245.3
BEGIN DESCRIPTION:
Downstream Section of Bridge/Culvert/Weir
END DESCRIPTION:
#Sta/Elev= 29
  4775.5  229.74  4779.9  228.97  4815.5  222.72  4825.5  222.23  4829.9  222.52
  4833.8  222.78  4879.9  219.43  4913.8  216.96  4963.8  212.25  4973.8  212.34
 4979.41  212.64  4979.5  212.64  4979.6  212.65  4981.5  212.75  4983.3  209.15
    4984  207.75    5016  207.75  5018.5  212.75  5020.3  212.89 5020.39  212.89
  5020.5   212.9  5023.3  213.11  5113.3  219.89  5121.2  220.49  5140.2  221.92
  5190.2  224.23  5210.2  226.06  5240.2  227.42  5320.2  232.74
#Mann= 3 , 1 , 0
  4775.5     .13       0  4981.5    .044       0  5018.5     .13       0
#XS Ineff= 2 , 0
       0    4969  217.66    5031       0  217.66
Permanent Ineff=
       F       F
Bank Sta=4981.5,5018.5
XS Rating Curve= 0
Exp/Cntr=.5,.3

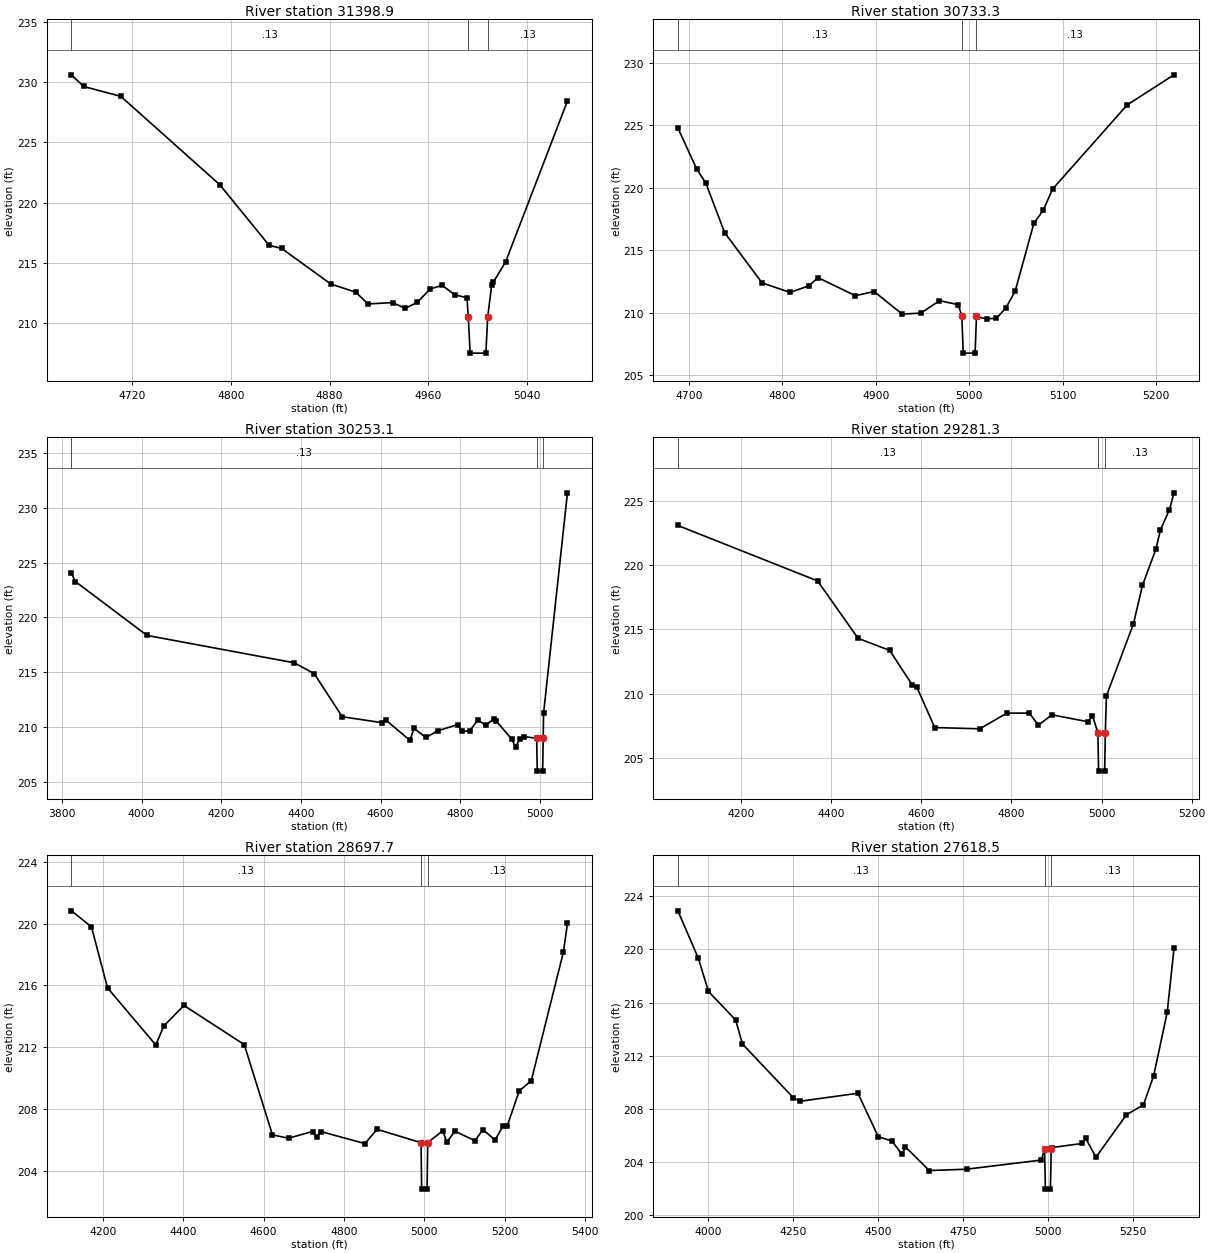
Type RM Length L Ch R = 1 ,31398.9 ,665.6,665.6,665.6
BEGIN DESCRIPTION:
Big Peachtree Creek 29.0
END DESCRIPTION:
#Sta/Elev= 24
  4671.1  230.62  4681.1  229.65  4711.1  228.83  4791.1  221.49  4831.1  216.44
  4841.1  216.19  4881.1  213.22  4901.1  212.55  4911.1  211.57  4931.1  211.68
  4941.1   211.2  4951.1  211.71  4961.1   212.8  4971.1  213.12  4981.1  212.33
  4991.1  212.09  4992.2  210.48  4993.7  207.48  5006.4  207.48  5007.9  210.48
  5011.1  213.15  5012.4  213.37  5022.4  215.07  5072.4  228.45
#Mann= 3 , 1 , 0
  4671.1     .13       0  4992.2    .044       0  5007.9     .13       0
Bank Sta=4992.2,5007.9
XS Rating Curve= 0
Exp/Cntr=.3,.1

Type RM Length L Ch R = 1 ,30733.3 ,480.2,480.2,480.2
BEGIN DESCRIPTION:
Big Peachtree Creek 28.0
END DESCRIPTION:
#Sta/Elev= 28
  4688.2  224.77  4708.2  221.51  4718.2  220.34  4738.2   216.4  4778.2  212.38
  4808.2  211.61  4828.2  212.13  4838.2  212.79  4878.2  211.35  4898.2  211.68
  4928.2  209.88  4948.2  209.95  4968.2  210.95  4988.2  210.63  4992.1  209.75
  4993.6  206.75  5006.3  206.75  5007.8  209.75  5008.2  209.65  5019.2   209.5
  5029.2  209.54  5039.2  210.36  5049.2  211.71  5069.2  217.14  5079.2  218.18
  5089.2  219.88  5169.2  226.63  5219.2  229.03
#Mann= 3 , 1 , 0
  4688.2     .13       0  4992.1    .044       0  5007.8     .13       0
Bank Sta=4992.1,5007.8
XS Rating Curve= 0
Exp/Cntr=.3,.1

Type RM Length L Ch R = 1 ,30253.1 ,971.8,971.8,971.8
BEGIN DESCRIPTION:
Big Peachtree Creek 27.0
END DESCRIPTION:
#Sta/Elev= 29
  3823.7  224.04  3833.7  223.28  4013.7  218.36  4383.7  215.86  4433.7  214.86
  4503.7  210.94  4603.7   210.4  4613.7  210.62  4673.7  208.79  4683.7  209.88
  4713.7  209.05  4743.7  209.66  4793.7  210.23  4803.7  209.62  4823.7  209.63
  4843.7  210.64  4863.7  210.18  4883.7  210.71  4889.1  210.59  4929.1  208.91
  4939.1  208.15  4949.1  208.93  4959.1  209.13  4991.8  208.98  4993.3  205.98
  5006.8  205.98  5008.3  208.98  5009.1  211.24  5069.1  231.37
#Mann= 3 , 1 , 0
  3823.7     .13       0  4991.8    .044       0  5008.3     .13       0
Bank Sta=4991.8,5008.3
XS Rating Curve= 0
Exp/Cntr=.3,.1

Type RM Length L Ch R = 1 ,29281.3 ,583.6,583.6,583.6
BEGIN DESCRIPTION:
Big Peachtree Creek 26.0
END DESCRIPTION:
#Sta/Elev= 25
  4059.7  223.08  4369.7  218.77  4459.7   214.3  4529.7  213.37  4579.7  210.69
  4589.7  210.53  4629.7  207.37  4729.7  207.27  4789.7  208.49  4839.7  208.49
  4859.7  207.55  4889.7  208.36  4969.7  207.82  4979.7  208.29  4991.8  206.98
  4993.3  203.98  5006.8  203.98  5008.3  206.98  5010.7  209.83  5070.7  215.43
  5090.7  218.42  5120.7  221.26  5130.7  222.74  5150.7  224.32  5160.7  225.62
#Mann= 3 , 1 , 0
  4059.7     .13       0  4991.8    .044       0  5008.3     .13       0
Bank Sta=4991.8,5008.3
XS Rating Curve= 0
Exp/Cntr=.3,.1

Type RM Length L Ch R = 1 ,28697.7 ,1079.2,1079.2,1079.2
BEGIN DESCRIPTION:
Big Peachtree Creek 25.0
END DESCRIPTION:
#Sta/Elev= 30
  4122.2  220.82  4172.2  219.79  4212.2  215.84  4332.2  212.16  4352.2  213.39
  4402.2  214.71  4552.2  212.18  4622.2  206.35  4662.2  206.14  4722.2  206.57
  4732.2  206.21  4742.2  206.57  4852.2  205.79  4882.2  206.71  4991.7  205.85
  4993.2  202.85  5006.7  202.85  5008.2  205.85  5045.7  206.62  5055.7  205.88
  5075.7  206.59  5125.7  205.98  5145.7  206.69  5175.7  206.02  5195.7  206.94
  5205.7   206.9  5235.7  209.19  5265.7  209.85  5345.7  218.16  5355.7  220.01
#Mann= 3 , 1 , 0
  4122.2     .13       0  4991.7    .044       0  5008.2     .13       0
Bank Sta=4991.7,5008.2
XS Rating Curve= 0
Exp/Cntr=.3,.1

Type RM Length L Ch R = 1 ,27618.5 ,494.4,494.4,494.4
BEGIN DESCRIPTION:
Big Peachtree Creek 24.0
END DESCRIPTION:
#Sta/Elev= 28
  3910.7  222.91  3970.7  219.35  4000.7  216.84  4080.7  214.69  4100.7  212.88
  4250.7  208.83  4270.7  208.57  4440.7  209.17  4500.7   205.9  4540.7  205.57
  4570.7  204.57  4580.7  205.13  4650.7  203.35  4760.7  203.45  4980.7  204.14
  4990.2  204.95  4992.7  201.95  5007.4  201.95  5009.9  204.95  5011.3  205.08
  5101.3  205.39  5111.3  205.79  5141.3  204.35  5231.3  207.55  5281.3   208.3
  5311.3  210.47  5351.3  215.26  5371.3  220.09
#Mann= 3 , 1 , 0
  3910.7     .13       0  4990.2    .044       0  5009.9     .13       0
Bank Sta=4990.2,5009.9
XS Rating Curve= 0
Exp/Cntr=.3,.1

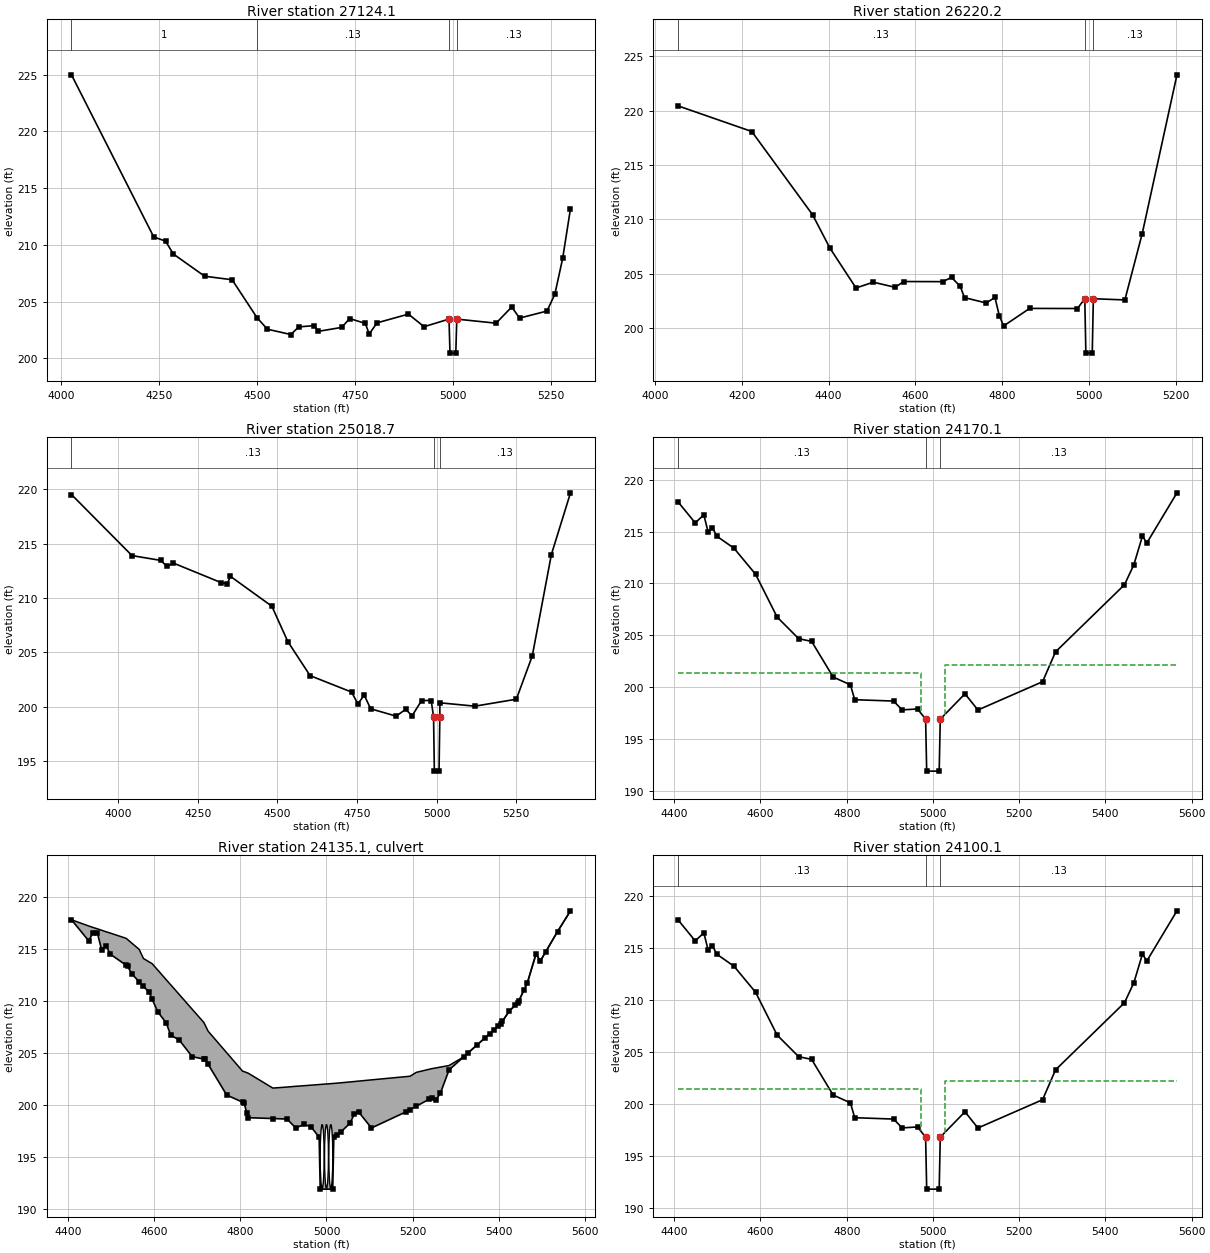
Type RM Length L Ch R = 1 ,27124.1 ,903.9,903.9,903.9
BEGIN DESCRIPTION:
Big Peachtree Creek 23.0
END DESCRIPTION:
#Sta/Elev= 30
  4026.4  224.99  4236.4  210.69  4266.4  210.33  4286.4  209.19  4366.4  207.23
  4436.4  206.92  4499.9  203.58  4526.4  202.56  4586.4  202.09  4606.4  202.76
  4646.4  202.88  4656.4  202.37  4716.4  202.72  4736.4   203.5  4776.4  203.07
  4786.4  202.14  4806.4  203.12  4886.4  203.89  4926.4  202.78  4990.1  203.45
  4992.6  200.45  5007.4  200.45  5009.9  203.45  5110.2  203.09  5150.2  204.52
  5170.2  203.54  5240.2  204.16  5260.2  205.64  5280.2   208.8  5300.2   213.2
#Mann= 4 , 1 , 0
  4026.4       1       0  4499.9     .13       0  4990.1    .044       0
  5009.9     .13       0
Bank Sta=4990.1,5009.9
XS Rating Curve= 0
Exp/Cntr=.3,.1

Type RM Length L Ch R = 1 ,26220.2 ,1201.5,1201.5,1201.5
BEGIN DESCRIPTION:
Big Peachtree Creek 22.0
END DESCRIPTION:
#Sta/Elev= 25
  4053.2  220.44  4223.2  218.08  4363.2  210.43  4403.2  207.36  4463.2   203.7
  4503.2  204.23  4553.2  203.76  4573.2  204.29  4663.2  204.28  4683.2  204.67
  4703.2  203.85  4713.2  202.81  4763.2  202.32  4783.2  202.83  4793.2  201.16
  4803.2  200.21  4863.2  201.82  4973.2  201.81  4990.1  202.71  4992.6  197.71
  5007.3  197.71  5009.8  202.71  5082.4   202.6  5122.4   208.7  5202.4  223.29
#Mann= 3 , 1 , 0
  4053.2     .13       0  4990.1    .044       0  5009.8     .13       0
Bank Sta=4990.1,5009.8
XS Rating Curve= 0
Exp/Cntr=.3,.1

Type RM Length L Ch R = 1 ,25018.7 ,848.6,848.6,848.6
BEGIN DESCRIPTION:
Big Peachtree Creek 21.0
END DESCRIPTION:
#Sta/Elev= 30
  3853.8  219.53  4043.8  213.91  4133.8  213.47  4153.8  212.91  4173.8  213.22
  4323.8  211.42  4342.7  211.32  4352.7     212  4482.7  209.25  4532.7     206
  4602.7  202.86  4732.7  201.35  4752.7  200.27  4772.7  201.06  4792.7  199.81
  4872.7  199.13  4902.7  199.76  4922.7  199.16  4952.7  200.57  4982.7  200.57
  4990.2  199.07  4992.7  194.07  5007.4  194.07  5009.9  199.07    5010  200.36
    5120  200.05    5250  200.69    5300  204.67    5360  214.01    5420  219.69
#Mann= 3 , 1 , 0
  3853.8     .13       0  4990.2    .044       0  5009.9     .13       0
Bank Sta=4990.2,5009.9
XS Rating Curve= 0
Exp/Cntr=.5,.3

Type RM Length L Ch R = 1 ,24170.1 ,70,70,70
BEGIN DESCRIPTION:
Upstream Section of Bridge/Culvert/Weir
END DESCRIPTION:
#Sta/Elev= 30
  4408.6  217.86  4448.6  215.83  4468.6   216.6  4478.6  214.95  4488.6  215.37
  4498.6  214.55  4538.6  213.39  4588.6  210.89  4638.6  206.77  4688.6  204.69
  4718.6  204.43  4768.6     201  4808.6  200.25  4818.6  198.82  4908.6  198.69
  4928.6  197.84  4964.3  197.93    4983  196.95  4985.5  191.95  5014.5  191.95
    5017  196.95  5074.3  199.39  5104.3  197.83  5254.3  200.55  5284.3  203.42
  5444.3  209.88    5466   211.8    5486  214.57    5496  213.89    5566  218.72
#Mann= 3 , 1 , 0
  4408.6     .13       0    4983    .044       0    5017     .13       0
#XS Ineff= 2 , 0
       0    4972  201.43    5027       0   202.2
Permanent Ineff=
       F       F
Bank Sta=4983,5017
XS Rating Curve= 0
Exp/Cntr=.5,.3

Type RM Length L Ch R = 2 ,24135.1 ,,,
BEGIN DESCRIPTION:
Rommie Daniels Rd-TOR
Structure ID: Rommie Daniels Rd-Culvert
Approximate Survey Structure
END DESCRIPTION:
Bridge Culvert--1,0,-1,-1, 0
Deck Dist Width WeirC Skew NumUp NumDn MinLoCord MaxHiCord MaxSubmerge Is_Ogee
10,50,3,0, 55, 55, , , .95, 0, 1,1,,
  4408.6  4448.6  4458.6  4468.6  4478.6  4488.6  4498.6  4535.6  4538.6  4548.6
  4565.6  4575.6  4588.6  4595.6  4608.6  4628.6  4638.6  4658.6  4688.6  4715.6
  4718.6  4725.6  4768.6  4805.6  4808.6  4818.6  4875.6  4908.6  4928.6  4948.6
  4964.3    4983  4985.5  5014.5    5017  5034.3  5054.3  5064.3  5074.3  5104.3
    5194  5208.2  5244.3  5254.3  5264.3  5284.3  5318.2  5404.3  5424.3  5444.3
    5466    5486    5496    5536    5566
  217.84  217.24   217.1  216.97  216.83  216.69  216.56  216.05  215.94  215.59
  214.99  214.11  213.79  213.62  213.01  212.06  211.59  210.65  209.23  207.96
  207.71  207.12  205.05  203.27  203.24  203.08  201.65  201.75  201.82  201.88
  201.93  201.99     202  202.09   202.1  202.16  202.24  202.28  202.32  202.44
  202.79  203.16  203.52  203.59  203.67  203.82  204.65  207.84  209.08  209.86
  211.78  214.55  213.87  216.71   218.7
  217.84  215.81   216.6  216.58  214.93  215.35  214.53  213.46  213.37  212.63
  211.88  211.44  210.87  210.21  208.99   207.9  206.75  206.27  204.67  204.44
  204.41  203.93  200.98  200.29  200.23   198.8  198.72  198.67  197.82  198.15
  197.91  196.93  191.93  191.93  196.93  197.46  198.26  199.12  199.37  197.81
  199.58   199.9  200.72  200.53  201.16   203.4  204.65  207.84  209.08  209.86
  211.78  214.55  213.87  216.71   218.7
  4408.6  4448.6  4458.6  4468.6  4478.6  4488.6  4498.6  4535.6  4538.6  4548.6
  4565.6  4575.6  4588.6  4595.6  4608.6  4628.6  4638.6  4658.6  4688.6  4715.6
  4718.6  4725.6  4768.6  4805.6  4808.6  4818.6  4875.6  4908.6  4928.6  4948.6
  4964.3    4983  4985.5  5014.5    5017  5034.3  5054.3  5064.3  5074.3  5104.3
    5194  5208.2  5244.3  5254.3  5264.3  5284.3  5318.2  5404.3  5424.3  5444.3
    5466    5486    5496    5536    5566
  217.79  217.24   217.1  216.97  216.83  216.69  216.56  216.05  215.94  215.59
  214.99  214.11  213.79  213.62  213.01  212.06  211.59  210.65  209.23  207.96
  207.71  207.12  205.05  203.27  203.24  203.08  201.65  201.75  201.82  201.88
  201.93  201.99     202  202.09   202.1  202.16  202.24  202.28  202.32  202.44
  202.79  203.16  203.52  203.59  203.67  203.82  204.61   207.8  209.04  209.82
  211.74  214.51  213.83  216.67  218.65
  217.73   215.7  216.49  216.47  214.82  215.24  214.42  213.35  213.26  212.52
  211.77  211.33  210.76   210.1  208.88  207.79  206.64  206.16  204.56  204.33
   204.3  203.82  200.87  200.18  200.12  198.69  198.61  198.56  197.71  198.04
   197.8  196.82  191.82  191.82  196.82  197.35  198.15  199.01  199.26   197.7
  199.47  199.79  200.61  200.42  201.05  203.29  204.54  207.73  208.97  209.75
  211.67  214.44  213.76   216.6  218.59
BR Coef= 1 , 0 , 0 ,1.25, 0 ,,,.8,-1,2,0,
WSPro=,,,, 1 ,,,, 0 ,,,, 0 ,,,,-1 ,-1 ,-1 , 0 , 0 , 0 , 0 , 0
Culvert=3,6.14,9,50,.024,.4,1,34,1,192,4990.04,191.75,4990.04,Culvert #1  , 0 ,10
Culvert Bottom n=.024
Culvert=3,6.14,9,50,.024,.4,1,34,1,192,5000.04,191.75,5000.04,Culvert #2  , 0 ,10
Culvert Bottom n=.024
Culvert=3,6.14,9,50,.024,.4,1,34,1,192,5010.04,191.75,5010.04,Culvert #3  , 0 ,10
Culvert Bottom n=.024
BR U #Sta/Elev= 70
  4408.6  217.84  4448.6  215.81  4458.6   216.6  4468.6  216.58  4478.6  214.93
  4488.6  215.35  4498.6  214.53  4535.6  213.46  4538.6  213.37  4548.6  212.63
  4565.6  211.88  4575.6  211.44  4588.6  210.87  4595.6  210.21  4608.6  208.99
  4628.6   207.9  4638.6  206.75  4658.6  206.27  4688.6  204.67  4715.6  204.44
  4718.6  204.41  4725.6  203.93  4768.6  200.98  4805.6  200.29  4808.6  200.23
  4815.6  199.23  4818.6   198.8  4875.6  198.72  4908.6  198.67  4928.6  197.82
  4948.6  198.15  4964.3  197.91    4983  196.93  4985.5  191.93  5014.5  191.93
    5017  196.93    5024  197.14  5034.3  197.46  5054.3  198.26  5064.3  199.12
  5074.3  199.37  5104.3  197.81  5184.3  199.36    5194  199.58  5208.2   199.9
  5238.2  200.58  5244.3  200.72  5254.3  200.53  5264.3  201.16  5284.3   203.4
  5318.2  204.65  5328.2  205.02  5348.2  205.76  5368.2   206.5  5378.2  206.87
  5388.2  207.24  5398.2  207.61  5404.3  207.84  5408.2  208.08  5424.3  209.08
  5438.2  209.62  5444.3  209.86    5446  210.03  5458.2   211.1    5466  211.78
    5486  214.55    5496  213.87  5508.2  214.74    5536  216.71    5566   218.7
BR U #Mann= 3
  4408.6     .13    4983    .044    5017     .13
BR U Banks=4983,5017
BR D #Sta/Elev= 70
  4408.6  217.73  4448.6   215.7  4458.6  216.49  4468.6  216.47  4478.6  214.82
  4488.6  215.24  4498.6  214.42  4535.6  213.35  4538.6  213.26  4548.6  212.52
  4565.6  211.77  4575.6  211.33  4588.6  210.76  4595.6   210.1  4608.6  208.88
  4628.6  207.79  4638.6  206.64  4658.6  206.16  4688.6  204.56  4715.6  204.33
  4718.6   204.3  4725.6  203.82  4768.6  200.87  4805.6  200.18  4808.6  200.12
  4815.6  199.12  4818.6  198.69  4875.6  198.61  4908.6  198.56  4928.6  197.71
  4948.6  198.04  4964.3   197.8    4983  196.82  4985.5  191.82  5014.5  191.82
    5017  196.82    5024  197.03  5034.3  197.35  5054.3  198.15  5064.3  199.01
  5074.3  199.26  5104.3   197.7  5184.3  199.25    5194  199.47  5208.2  199.79
  5238.2  200.47  5244.3  200.61  5254.3  200.42  5264.3  201.05  5284.3  203.29
  5318.2  204.54  5328.2  204.91  5348.2  205.65  5368.2  206.39  5378.2  206.76
  5388.2  207.13  5398.2   207.5  5404.3  207.73  5408.2  207.97  5424.3  208.97
  5438.2  209.51  5444.3  209.75    5446  209.92  5458.2  210.99    5466  211.67
    5486  214.44    5496  213.76  5508.2  214.63    5536   216.6    5566  218.59
BR D #Mann= 3
  4408.6     .13    4983    .044    5017     .13
BR D Banks=4983,5017
BC Design=,, 0 ,, 0 ,,,,,,

Type RM Length L Ch R = 1 ,24100.1 ,745.4,745.4,745.4
BEGIN DESCRIPTION:
Downstream Section of Bridge/Culvert/Weir
END DESCRIPTION:
#Sta/Elev= 30
  4408.6  217.71  4448.6  215.68  4468.6  216.45  4478.6   214.8  4488.6  215.22
  4498.6   214.4  4538.6  213.24  4588.6  210.74  4638.6  206.62  4688.6  204.54
  4718.6  204.28  4768.6  200.85  4808.6   200.1  4818.6  198.67  4908.6  198.54
  4928.6  197.69  4964.3  197.78    4983   196.8  4985.5   191.8  5014.5   191.8
    5017   196.8  5074.3  199.24  5104.3  197.68  5254.3   200.4  5284.3  203.27
  5444.3  209.73    5466  211.65    5486  214.42    5496  213.74    5566  218.57
#Mann= 3 , 1 , 0
  4408.6     .13       0    4983    .044       0    5017     .13       0
#XS Ineff= 2 , 0
       0    4972  201.43    5027       0   202.2
Permanent Ineff=
       F       F
Bank Sta=4983,5017
XS Rating Curve= 0
Exp/Cntr=.5,.3