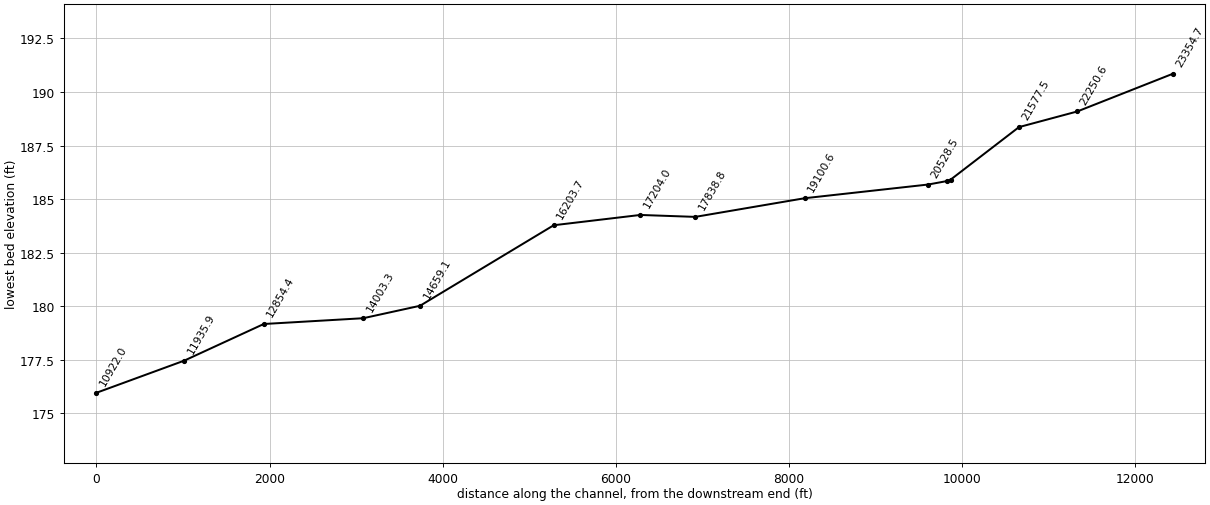
HEC-RAS study 020911_big_peachtree_creek.prj: BIG_PEACHTREE_CREEK

--- 020911_big_peachtree_creek.g01 (geometry) --- (continued)

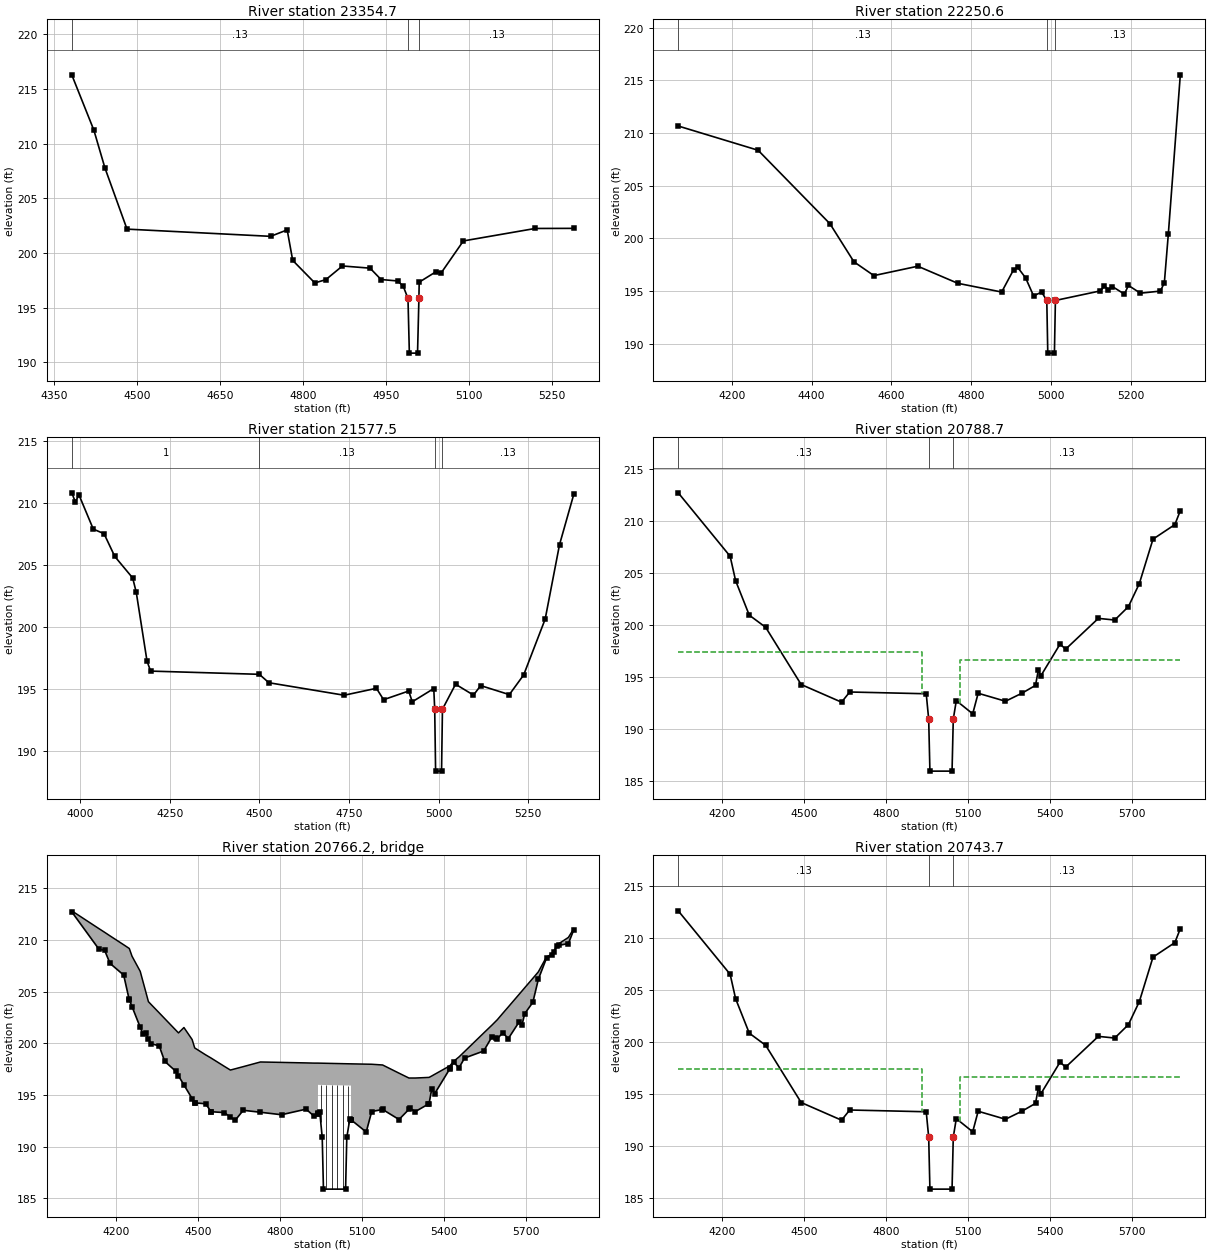
Type RM Length L Ch R = 1 ,23354.7 ,1104.1,1104.1,1104.1
BEGIN DESCRIPTION:
Big Peachtree Creek 20.0
END DESCRIPTION:
#Sta/Elev= 24
  4381.4   216.3  4421.4  211.24  4441.4  207.79  4481.4  202.19  4741.4  201.53
  4771.4  202.12  4781.4  199.33  4821.4  197.27  4841.4  197.57  4871.4  198.82
  4921.4  198.62  4941.4  197.58  4971.4  197.45  4981.4  196.98  4990.1  195.85
  4992.6  190.85  5007.4  190.85  5009.9  195.85  5010.4  197.34  5040.4  198.28
  5050.4   198.2  5090.4  201.11  5220.4  202.25  5290.4  202.26
#Mann= 3 , 1 , 0
  4381.4     .13       0  4990.1    .044       0  5009.9     .13       0
Bank Sta=4990.1,5009.9
XS Rating Curve= 0
Exp/Cntr=.3,.1

Type RM Length L Ch R = 1 ,22250.6 ,673.1,673.1,673.1
BEGIN DESCRIPTION:
Big Peachtree Creek 19.0
END DESCRIPTION:
#Sta/Elev= 28
  4066.2  210.65  4266.2  208.35  4446.2  201.37  4506.2  197.76  4556.2  196.45
  4666.2  197.34  4766.2  195.72  4876.2  194.89  4906.2  197.02  4916.2  197.24
  4936.2  196.23  4956.2  194.52  4976.2  194.89  4989.2  194.09  4991.7  189.09
  5008.3  189.09  5010.8  194.09  5123.6     195  5133.6  195.47  5143.6  195.12
  5153.6  195.41  5183.6  194.69  5193.6  195.52  5223.6  194.78  5273.6  194.98
  5283.6  195.76  5293.6   200.4  5323.6  215.51
#Mann= 3 , 1 , 0
  4066.2     .13       0  4989.2    .044       0  5010.8     .13       0
Bank Sta=4989.2,5010.8
XS Rating Curve= 0
Exp/Cntr=.3,.1

Type RM Length L Ch R = 1 ,21577.5 ,788.8,788.8,788.8
BEGIN DESCRIPTION:
Big Peachtree Creek 18.0
END DESCRIPTION:
#Sta/Elev= 30
  3976.6  210.84  3986.6   210.1  3996.6  210.68  4036.6  207.91  4066.6  207.54
  4096.6   205.7  4146.6  203.96  4156.6  202.79  4186.6  197.24  4196.6  196.44
  4499.9  196.18  4526.6   195.5  4736.6  194.49  4826.6  195.05  4846.6  194.13
  4916.6  194.83  4926.6  193.96  4986.6  195.03  4989.2  193.36  4991.7  188.36
  5008.3  188.36  5010.8  193.36  5047.4  195.38  5097.4   194.5  5117.4  195.27
  5197.4  194.54  5237.4  196.13  5297.4  200.64  5337.4  206.65  5377.4  210.74
#Mann= 4 , 1 , 0
  3976.6       1       0  4499.9     .13       0  4989.2    .044       0
  5010.8     .13       0
Bank Sta=4989.2,5010.8
XS Rating Curve= 0
Exp/Cntr=.3,.1

Type RM Length L Ch R = 1 ,20788.7 ,45,45,45
BEGIN DESCRIPTION:
Upstream Section of Bridge/Culvert/Weir
END DESCRIPTION:
#Sta/Elev= 30
  4038.2  212.71  4228.2   206.6  4248.2  204.25  4298.2  200.93  4358.2  199.76
  4488.2  194.25    4636  192.55    4666  193.53    4946  193.36    4955  190.91
  4959.5  185.91  5040.5  185.91    5045  190.91  5056.1   192.7  5116.1  191.43
  5136.1  193.41  5236.1  192.64  5296.1  193.41  5346.1  194.17  5356.1  195.61
  5366.1  195.11  5436.1  198.15  5456.1  197.65  5576.1  200.62  5636.1  200.46
  5686.1  201.75  5726.1  203.97  5776.1  208.25  5856.1  209.65  5876.1  210.99
#Mann= 3 , 1 , 0
  4038.2     .13       0    4955    .044       0    5045     .13       0
#XS Ineff= 2 , 0
       0    4929  197.37    5071       0  196.63
Permanent Ineff=
       F       F
Bank Sta=4955,5045
XS Rating Curve= 0
Exp/Cntr=.5,.3

Type RM Length L Ch R = 3 ,20766.2 ,,,
BEGIN DESCRIPTION:
Lancaster Store Rd-TOR
Structure ID: Lancaster Store Rd-Bridge
Approximate Survey Structure
END DESCRIPTION:
Bridge Culvert--1,0,-1,-1, 0
Deck Dist Width WeirC Skew NumUp NumDn MinLoCord MaxHiCord MaxSubmerge Is_Ogee
10,25,2.6,0, 60, 60, , , .95, 0, 1,1,,
  4038.2  4138.2  4158.2  4178.2  4228.2  4248.8  4258.8  4288.8  4298.2  4308.2
  4318.8  4328.2  4358.2  4378.2  4428.8  4448.8  4478.8  4488.2  4528.2  4548.2
    4596  4618.8    4636    4666  4728.8    4806    4896    4926 4939.41  4939.5
 5060.39  5060.5  5116.1  5136.1  5176.1  5236.1  5272.3  5296.1  5346.1  5356.1
  5366.1  5422.3  5436.1  5456.1  5476.1  5546.1  5576.1  5596.1  5616.1  5636.1
  5676.1  5686.1  5696.1  5726.1  5746.1  5776.1  5796.1  5816.1  5856.1  5876.1
   212.8  211.07  210.73  210.38  209.52  209.16  208.41  206.95  206.03  205.06
  204.02  203.76  202.94  202.39     201  201.52  200.36  199.55  198.88  198.57
  197.78  197.41  197.53  197.74  198.19  198.15   198.1  198.08  198.08  198.08
  198.01  198.01  197.98  197.97   197.9  197.11  196.64  196.64   196.7  196.84
  196.99  197.82  198.25  198.69   199.2  200.99  201.75  202.28   202.9  203.51
  204.74  205.05  205.36  206.28   206.9  208.35  208.61  209.54  210.23  211.08
   212.7  209.07     209  207.72  206.59   204.2  203.54  201.54  200.92  200.97
  200.43  199.96  199.75  198.26  196.85  195.97  194.65  194.24  194.15  193.38
   193.3  192.87  192.54  193.52  193.33  193.09  193.63  192.93  193.21  195.98
  195.91   192.6  191.42   193.4   193.6  192.63  193.61   193.4  194.16   195.6
   195.1  197.54  198.14  197.64  198.57  199.25  200.61  200.44  201.02  200.45
  202.07  201.74  202.85  203.96  206.18  208.24   208.5  209.43  209.64  210.98
  4038.2  4138.2  4158.2  4178.2  4228.2  4248.8  4258.8  4288.8  4298.2  4308.2
  4318.8  4328.2  4358.2  4378.2  4428.8  4448.8  4478.8  4488.2  4528.2  4548.2
    4596  4618.8    4636    4666  4728.8    4806    4896    4926 4939.41  4939.5
 5060.39  5060.5  5116.1  5136.1  5176.1  5236.1  5272.3  5296.1  5346.1  5356.1
  5366.1  5422.3  5436.1  5456.1  5476.1  5546.1  5576.1  5596.1  5616.1  5636.1
  5676.1  5686.1  5696.1  5726.1  5746.1  5776.1  5796.1  5816.1  5856.1  5876.1
   212.8  211.07  210.73  210.38  209.52  209.16  208.41  206.95  206.03  205.06
  204.02  203.76  202.94  202.39     201  201.52  200.36  199.55  198.88  198.57
  197.78  197.41  197.53  197.74  198.19  198.15   198.1  198.08  198.08  198.08
  198.01  198.01  197.98  197.97   197.9  197.11  196.64  196.64   196.7  196.84
  196.99  197.82  198.25  198.69   199.2  200.99  201.75  202.28   202.9  203.51
  204.74  205.05  205.36  206.28   206.9  208.35  208.61  209.54  210.23  211.08
  212.65  209.02  208.95  207.67  206.54  204.15  203.49  201.49  200.87  200.92
  200.38  199.91   199.7  198.21   196.8  195.92   194.6  194.19   194.1  193.33
  193.25  192.82  192.49  193.47  193.28  193.04  193.58  192.88  193.16  195.93
  195.86  192.55  191.37  193.35  193.55  192.58  193.56  193.35  194.11  195.55
  195.05  197.49  198.09  197.59  198.52   199.2  200.56  200.39  200.97   200.4
  202.02  201.69   202.8  203.91  206.13  208.19  208.45  209.38  209.59  210.93
Pier Skew, UpSta & Num, DnSta & Num=  ,4949.5, 2 ,4949.5, 2 , 0 , 0 , 0 ,,
       1       1
  191.26  196.97
       1       1
  191.21  196.92
Pier Skew, UpSta & Num, DnSta & Num=  ,4969.7, 2 ,4969.7, 2 , 0 , 0 , 0 ,,
       1       1
   184.9  196.96
       1       1
  184.85  196.91
Pier Skew, UpSta & Num, DnSta & Num=  ,4989.9, 2 ,4989.9, 2 , 0 , 0 , 0 ,,
       1       1
   184.9  196.95
       1       1
  184.85   196.9
Pier Skew, UpSta & Num, DnSta & Num=  ,5010, 2 ,5010, 2 , 0 , 0 , 0 ,,
       1       1
   184.9  196.94
       1       1
  184.85  196.89
Pier Skew, UpSta & Num, DnSta & Num=  ,5030.2, 2 ,5030.2, 2 , 0 , 0 , 0 ,,
       1       1
   184.9  196.93
       1       1
  184.85  196.88
Pier Skew, UpSta & Num, DnSta & Num=  ,5050.4, 2 ,5050.4, 2 , 0 , 0 , 0 ,,
       1       1
  190.69  196.92
       1       1
  190.64  196.87
BR Coef= 1 , 1 , 0 ,1.25, 0 ,,,.8,0,2,0,
WSPro=,,,, 1 ,,,, 0 ,,,, 0 ,,,,-1 ,-1 ,-1 , 0 , 0 , 0 , 0 , 0
BR U #Sta/Elev= 79
  4038.2   212.7  4138.2  209.07  4158.2     209  4178.2  207.72  4228.2  206.59
  4248.2  204.24  4248.8   204.2  4258.8  203.54  4288.8  201.54  4298.2  200.92
  4308.2  200.97  4318.8  200.43  4328.2  199.96  4358.2  199.75  4378.2  198.26
  4418.2  197.31  4428.8  196.85  4448.8  195.97  4478.8  194.65  4488.2  194.24
  4488.8  194.24  4528.2  194.15  4548.2  193.38  4548.8  193.38    4596   193.3
  4618.8  192.87    4636  192.54    4666  193.52  4728.8  193.33    4806  193.09
    4896  193.63    4926  192.93 4939.41  193.21  4939.5  193.21  4939.6  193.22
    4946  193.35    4955   190.9  4959.5   185.9  5040.5   185.9    5045   190.9
  5056.1  192.69  5060.3   192.6 5060.39   192.6  5060.5   192.6  5116.1  191.42
  5136.1   193.4  5172.3  193.58  5176.1   193.6  5236.1  192.63  5272.3  193.61
  5276.1  193.71  5296.1   193.4  5342.3   194.1  5346.1  194.16  5356.1   195.6
  5366.1   195.1  5422.3  197.54  5422.8  197.56  5436.1  198.14  5456.1  197.64
  5476.1  198.57  5546.1  199.25  5576.1  200.61  5592.8  200.47  5596.1  200.44
  5616.1  201.02  5636.1  200.45  5676.1  202.07  5686.1  201.74  5696.1  202.85
  5726.1  203.96  5746.1  206.18  5776.1  208.24  5796.1   208.5  5802.8  208.81
  5816.1  209.43  5822.8  209.47  5856.1  209.64  5876.1  210.98
BR U #Mann= 3
  4038.2     .13    4955    .044    5045     .13
BR U Banks=4955,5045
BR D #Sta/Elev= 79
  4038.2  212.65  4138.2  209.02  4158.2  208.95  4178.2  207.67  4228.2  206.54
  4248.2  204.19  4248.8  204.15  4258.8  203.49  4288.8  201.49  4298.2  200.87
  4308.2  200.92  4318.8  200.38  4328.2  199.91  4358.2   199.7  4378.2  198.21
  4418.2  197.26  4428.8   196.8  4448.8  195.92  4478.8   194.6  4488.2  194.19
  4488.8  194.19  4528.2   194.1  4548.2  193.33  4548.8  193.33    4596  193.25
  4618.8  192.82    4636  192.49    4666  193.47  4728.8  193.28    4806  193.04
    4896  193.58    4926  192.88 4939.41  193.16  4939.5  193.16  4939.6  193.17
    4946   193.3    4955  190.85  4959.5  185.85  5040.5  185.85    5045  190.85
  5056.1  192.64  5060.3  192.55 5060.39  192.55  5060.5  192.55  5116.1  191.37
  5136.1  193.35  5172.3  193.53  5176.1  193.55  5236.1  192.58  5272.3  193.56
  5276.1  193.66  5296.1  193.35  5342.3  194.05  5346.1  194.11  5356.1  195.55
  5366.1  195.05  5422.3  197.49  5422.8  197.51  5436.1  198.09  5456.1  197.59
  5476.1  198.52  5546.1   199.2  5576.1  200.56  5592.8  200.42  5596.1  200.39
  5616.1  200.97  5636.1   200.4  5676.1  202.02  5686.1  201.69  5696.1   202.8
  5726.1  203.91  5746.1  206.13  5776.1  208.19  5796.1  208.45  5802.8  208.76
  5816.1  209.38  5822.8  209.42  5856.1  209.59  5876.1  210.93
BR D #Mann= 3
  4038.2     .13    4955    .044    5045     .13
BR D Banks=4955,5045
BC Design=,, 0 ,, 0 ,,,,,,

Type RM Length L Ch R = 1 ,20743.7 ,215.2,215.2,215.2
BEGIN DESCRIPTION:
Downstream Section of Bridge/Culvert/Weir
END DESCRIPTION:
#Sta/Elev= 30
  4038.2  212.64  4228.2  206.53  4248.2  204.18  4298.2  200.86  4358.2  199.69
  4488.2  194.18    4636  192.48    4666  193.46    4946  193.29    4955  190.84
  4959.5  185.84  5040.5  185.84    5045  190.84  5056.1  192.63  5116.1  191.36
  5136.1  193.34  5236.1  192.57  5296.1  193.34  5346.1   194.1  5356.1  195.54
  5366.1  195.04  5436.1  198.08  5456.1  197.58  5576.1  200.55  5636.1  200.39
  5686.1  201.68  5726.1   203.9  5776.1  208.18  5856.1  209.58  5876.1  210.92
#Mann= 3 , 1 , 0
  4038.2     .13       0    4955    .044       0    5045     .13       0
#XS Ineff= 2 , 0
       0    4929  197.37    5071       0  196.63
Permanent Ineff=
       F       F
Bank Sta=4955,5045
XS Rating Curve= 0
Exp/Cntr=.5,.3

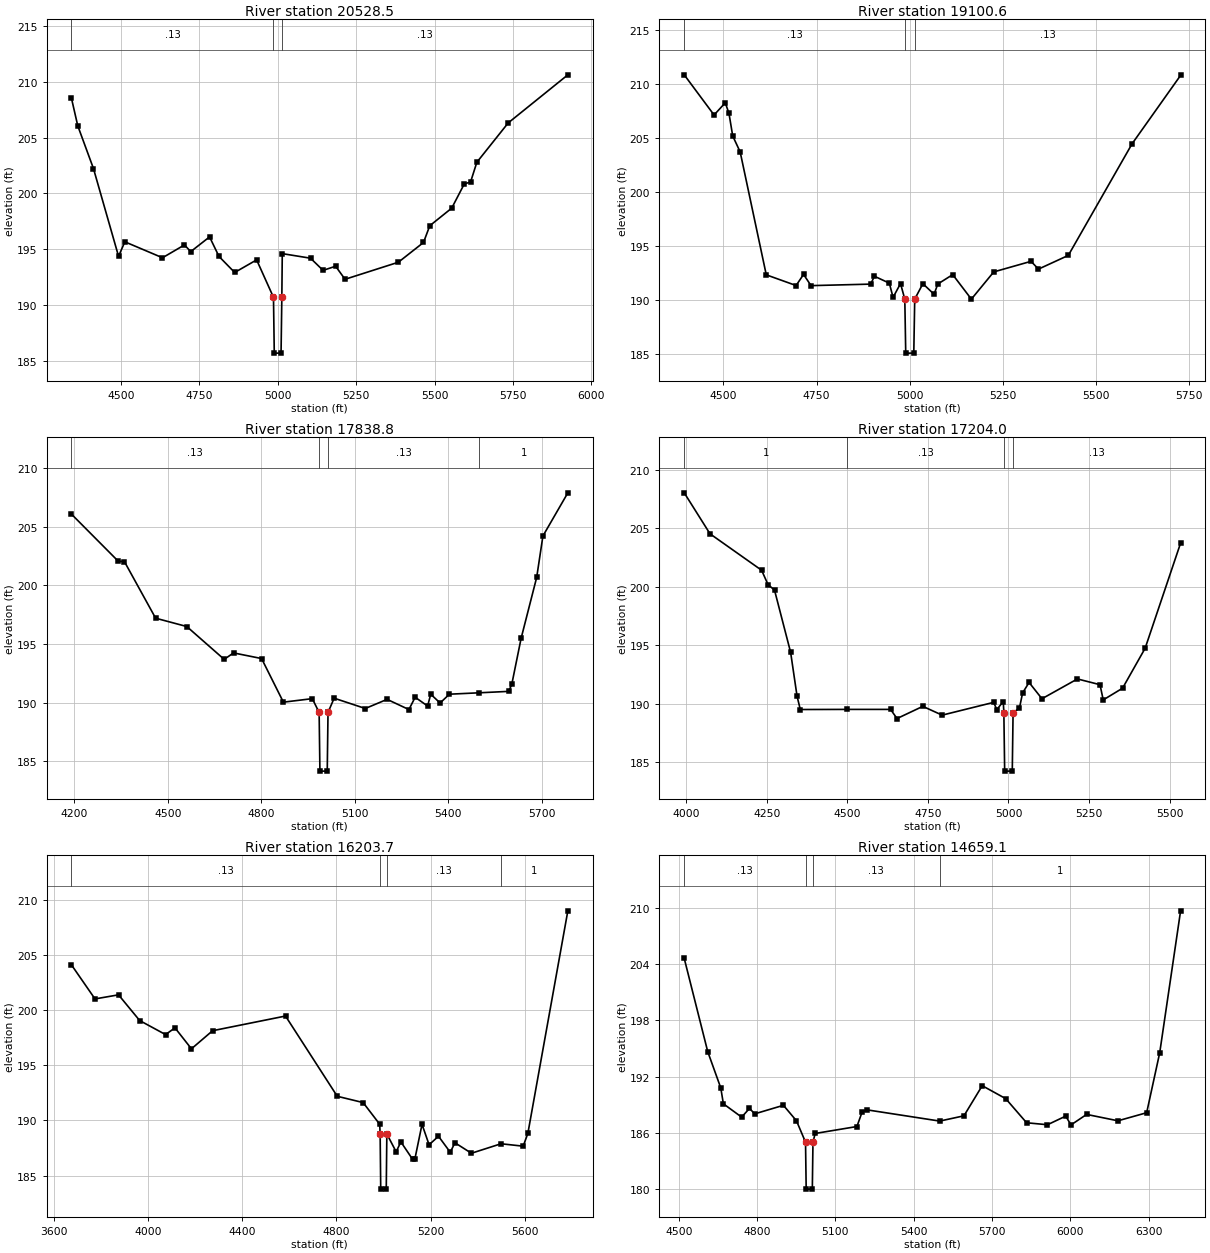
Type RM Length L Ch R = 1 ,20528.5 ,1427.9,1427.9,1427.9
BEGIN DESCRIPTION:
Big Peachtree Creek 17.0
END DESCRIPTION:
#Sta/Elev= 30
    4343  208.52    4363  206.06    4413  202.23    4493  194.36    4513  195.66
    4633  194.23    4703  195.38    4723  194.78    4783   196.1    4813  194.35
    4863  192.91    4933  194.04  4986.7  190.68  4989.2  185.68  5010.8  185.68
  5013.3  190.68  5014.7   194.6  5104.7  194.19  5144.7   193.1  5184.7  193.47
  5214.7   192.3  5384.7  193.83  5464.7   195.6  5484.7   197.1  5554.7  198.68
  5594.7  200.85  5614.7  201.02  5634.7  202.79  5734.7  206.32  5924.7  210.63
#Mann= 3 , 1 , 0
    4343     .13       0  4986.7    .044       0  5013.3     .13       0
Bank Sta=4986.7,5013.3
XS Rating Curve= 0
Exp/Cntr=.3,.1

Type RM Length L Ch R = 1 ,19100.6 ,1261.8,1261.8,1261.8
BEGIN DESCRIPTION:
Big Peachtree Creek 16.0
END DESCRIPTION:
#Sta/Elev= 30
  4395.2  210.81  4475.2  207.09  4505.2  208.22  4515.2  207.24  4525.2  205.15
  4545.2  203.67  4615.2  192.29  4695.2   191.3  4715.2  192.33  4735.2  191.29
  4895.2  191.43  4905.2  192.16  4945.2  191.52  4955.2   190.2  4975.2  191.48
  4986.7  190.04  4989.2  185.04  5010.8  185.04  5013.3  190.04  5035.2  191.47
  5065.2  190.49  5075.2  191.44  5115.2  192.31  5165.2  190.04  5225.2  192.56
  5325.2  193.54  5345.2  192.82  5425.2  194.09  5596.3  204.43  5726.3  210.76
#Mann= 3 , 1 , 0
  4395.2     .13       0  4986.7    .044       0  5013.3     .13       0
Bank Sta=4986.7,5013.3
XS Rating Curve= 0
Exp/Cntr=.3,.1

Type RM Length L Ch R = 1 ,17838.8 ,634.8,634.8,634.8
BEGIN DESCRIPTION:
Big Peachtree Creek 15.0
END DESCRIPTION:
#Sta/Elev= 30
    4191  206.08    4341  202.07    4361  202.03    4461  197.21    4561   196.5
    4681   193.7    4711  194.25    4801  193.77    4871  190.05  4963.8  190.35
  4985.7  189.17  4988.2  184.17  5011.7  184.17  5014.2  189.17  5033.8  190.39
  5133.8  189.51  5203.8  190.29  5273.8  189.42  5293.8  190.47  5333.8  189.72
  5343.8  190.73  5373.8  189.98  5403.8  190.73  5499.9  190.85  5593.8  190.97
  5603.8  191.56  5633.8  195.49  5683.8  200.69  5703.8  204.22  5783.8   207.9
#Mann= 4 , 1 , 0
    4191     .13       0  4985.7    .044       0  5014.2     .13       0
  5499.9       1       0
Bank Sta=4985.7,5014.2
XS Rating Curve= 0
Exp/Cntr=.3,.1

Type RM Length L Ch R = 1 ,17204.0 ,1000.3,1000.3,1000.3
BEGIN DESCRIPTION:
Big Peachtree Creek 14.0
END DESCRIPTION:
#Sta/Elev= 30
  3994.3  208.02  4074.3  204.52  4234.3  201.41  4254.3  200.18  4274.3  199.72
  4324.3   194.4  4344.3  190.65  4354.3  189.52  4499.9  189.53  4634.3  189.53
  4654.3  188.75  4734.3  189.79  4794.3  189.04  4953.9  190.13  4963.9  189.52
  4983.9   190.2  4985.7  189.26  4988.2  184.26  5011.8  184.26  5014.3  189.26
  5033.9  189.63  5043.9  190.94  5063.9  191.83  5103.9  190.44  5213.9  192.13
  5283.9  191.64  5293.9  190.34  5353.9  191.34  5423.9  194.75  5533.9  203.73
#Mann= 4 , 1 , 0
  3994.3       1       0  4499.9     .13       0  4985.7    .044       0
  5014.3     .13       0
Bank Sta=4985.7,5014.3
XS Rating Curve= 0
Exp/Cntr=.3,.1

Type RM Length L Ch R = 1 ,16203.7 ,1544.6,1544.6,1544.6
BEGIN DESCRIPTION:
Big Peachtree Creek 13.0
END DESCRIPTION:
#Sta/Elev= 30
  3673.5  204.09  3773.5  201.01  3873.5  201.38  3963.5  199.05  4073.5  197.78
  4113.5  198.39  4183.5  196.49  4273.5  198.13  4583.5  199.46  4803.5  192.19
  4913.5  191.62  4983.9  189.66  4985.8  188.78  4988.3  183.78  5011.8  183.78
  5014.3  188.78  5053.9  187.16  5073.9  188.06  5123.9  186.48  5133.9  186.55
  5163.9  189.65  5193.9   187.8  5233.9  188.57  5283.9  187.12  5303.9  187.98
  5373.9  187.03  5499.9  187.89  5593.9  187.67  5613.9  188.83  5783.9  208.99
#Mann= 4 , 1 , 0
  3673.5     .13       0  4985.8    .044       0  5014.3     .13       0
  5499.9       1       0
Bank Sta=4985.8,5014.3
XS Rating Curve= 0
Exp/Cntr=.3,.1

Type RM Length L Ch R = 1 ,14659.1 ,655.8,655.8,655.8
BEGIN DESCRIPTION:
Big Peachtree Creek 12.0
END DESCRIPTION:
#Sta/Elev= 30
  4521.1   204.6  4611.1  194.67  4661.1   190.8  4671.1  189.11  4741.1  187.69
  4771.1  188.62  4791.1  188.04  4901.1  188.95  4951.1   187.3  4985.8  185.02
  4988.3  180.02  5011.8  180.02  5014.3  185.02  5022.7  185.95  5182.7  186.69
  5202.7  188.25  5222.7  188.46  5499.9  187.27  5592.7  187.83  5662.7  191.04
  5752.7  189.66  5832.7  187.09  5912.7  186.88  5982.7   187.8  6002.7  186.86
  6062.7  187.98  6182.7   187.3  6292.7  188.16  6342.7  194.55  6422.7  209.67
#Mann= 4 , 1 , 0
  4521.1     .13       0  4985.8    .044       0  5014.3     .13       0
  5499.9       1       0
Bank Sta=4985.8,5014.3
XS Rating Curve= 0
Exp/Cntr=.3,.1

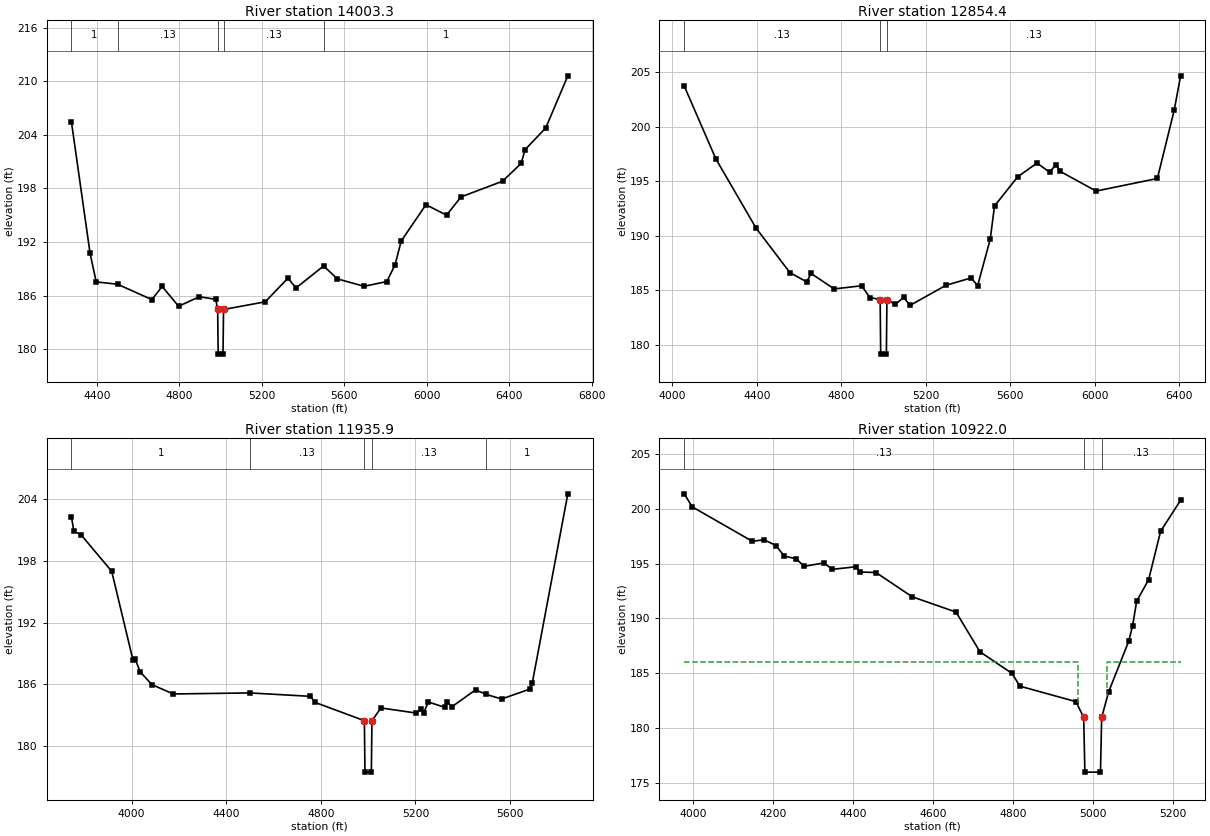
Type RM Length L Ch R = 1 ,14003.3 ,1148.9,1148.9,1148.9
BEGIN DESCRIPTION:
Big Peachtree Creek 11.0
END DESCRIPTION:
#Sta/Elev= 30
  4276.4  205.42  4366.4  190.76  4396.4  187.53  4499.9  187.27  4666.4  185.55
  4716.4  187.02  4796.4   184.8  4896.4  185.87  4976.4  185.58  4985.8  184.44
  4988.3  179.44  5011.8  179.44  5014.3  184.44  5216.5   185.3  5326.5  187.94
  5366.5  186.86  5499.9  189.32  5566.5  187.87  5696.5  187.04  5806.5  187.57
  5846.5  189.44  5876.5  192.11  5996.5  196.18  6096.5  195.01  6166.5  197.05
  6368.1  198.81  6458.1   200.8  6478.1  202.36  6578.1  204.79  6685.1  210.62
#Mann= 5 , 1 , 0
  4276.4       1       0  4499.9     .13       0  4985.8    .044       0
  5014.3     .13       0  5499.9       1       0
Bank Sta=4985.8,5014.3
XS Rating Curve= 0
Exp/Cntr=.3,.1

Type RM Length L Ch R = 1 ,12854.4 ,918.5,918.5,918.5
BEGIN DESCRIPTION:
Big Peachtree Creek 10.0
END DESCRIPTION:
#Sta/Elev= 30
  4056.5  203.71  4206.5  197.03  4396.5  190.71  4556.5  186.64  4636.5  185.78
  4656.5  186.56  4766.5  185.14  4896.5  185.43  4935.4  184.35    4984  184.17
  4986.5  179.17  5013.5  179.17    5016  184.17  5055.4  183.72  5095.4  184.37
  5125.4  183.63  5295.4  185.47  5415.4  186.15  5445.4  185.43  5505.4  189.71
  5525.4  192.73  5635.4  195.41  5726.5  196.66  5786.5  195.83  5816.5  196.53
  5836.5   195.9  6006.5   194.1  6296.5  195.25  6376.5  201.53  6406.5  204.65
#Mann= 3 , 1 , 0
  4056.5     .13       0    4984    .044       0    5016     .13       0
Bank Sta=4984,5016
XS Rating Curve= 0
Exp/Cntr=.3,.1

Type RM Length L Ch R = 1 ,11935.9 ,1013.9,1013.9,1013.9
BEGIN DESCRIPTION:
Big Peachtree Creek 9.0
END DESCRIPTION:
#Sta/Elev= 30
  3745.8  202.26  3755.8  200.88  3785.8  200.55  3915.8  196.99  4005.8  188.35
  4015.8  188.42  4035.8  187.22  4085.8  185.97  4175.8  185.06  4499.9  185.16
  4755.8  184.83  4775.8  184.24    4984  182.46  4986.5  177.46  5013.5  177.46
    5016  182.46  5054.1   183.7  5204.1   183.2  5224.1  183.56  5234.1  183.18
  5254.1  184.28  5324.1  183.76  5334.1   184.3  5354.1  183.82  5454.1  185.46
  5499.9  185.01  5564.1  184.57  5684.1  185.54  5694.1  186.16  5844.1  204.52
#Mann= 5 , 1 , 0
  3745.8       1       0  4499.9     .13       0    4984    .044       0
    5016     .13       0  5499.9       1       0
Bank Sta=4984,5016
XS Rating Curve= 0
Exp/Cntr=.3,.1

Type RM Length L Ch R = 1 ,10922.0 ,45,45,45
BEGIN DESCRIPTION:
Upstream Section of Bridge/Culvert/Weir
END DESCRIPTION:
#Sta/Elev= 30
    3978  201.38    3998  200.19    4148  197.05    4178  197.18    4208  196.65
    4228  195.69    4258  195.45    4278  194.76    4328  195.07    4348  194.48
    4408  194.72    4418  194.24    4458  194.19    4548  191.98    4658  190.58
    4718  186.95    4798  184.98    4818  183.81    4958   182.4  4977.5  180.96
  4980.5  175.96  5019.5  175.96  5022.5  180.96    5040   183.3    5090   187.9
    5100  189.34    5110  191.56    5140  193.54    5170  197.96    5220  200.79
#Mann= 3 , 1 , 0
    3978     .13       0  4977.5    .044       0  5022.5     .13       0
#XS Ineff= 2 , 0
       0    4963  186.05    5037       0  186.05
Permanent Ineff=
       F       F
Bank Sta=4977.5,5022.5
XS Rating Curve= 0
Exp/Cntr=.5,.3