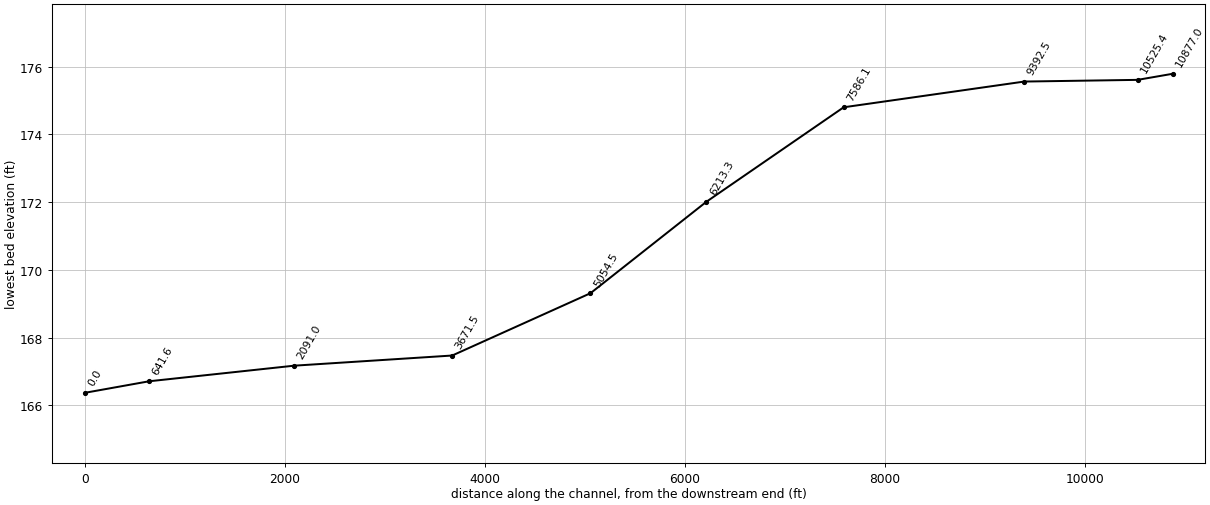
HEC-RAS study 020911_big_peachtree_creek.prj: BIG_PEACHTREE_CREEK

--- 020911_big_peachtree_creek.g01 (geometry) --- (continued)

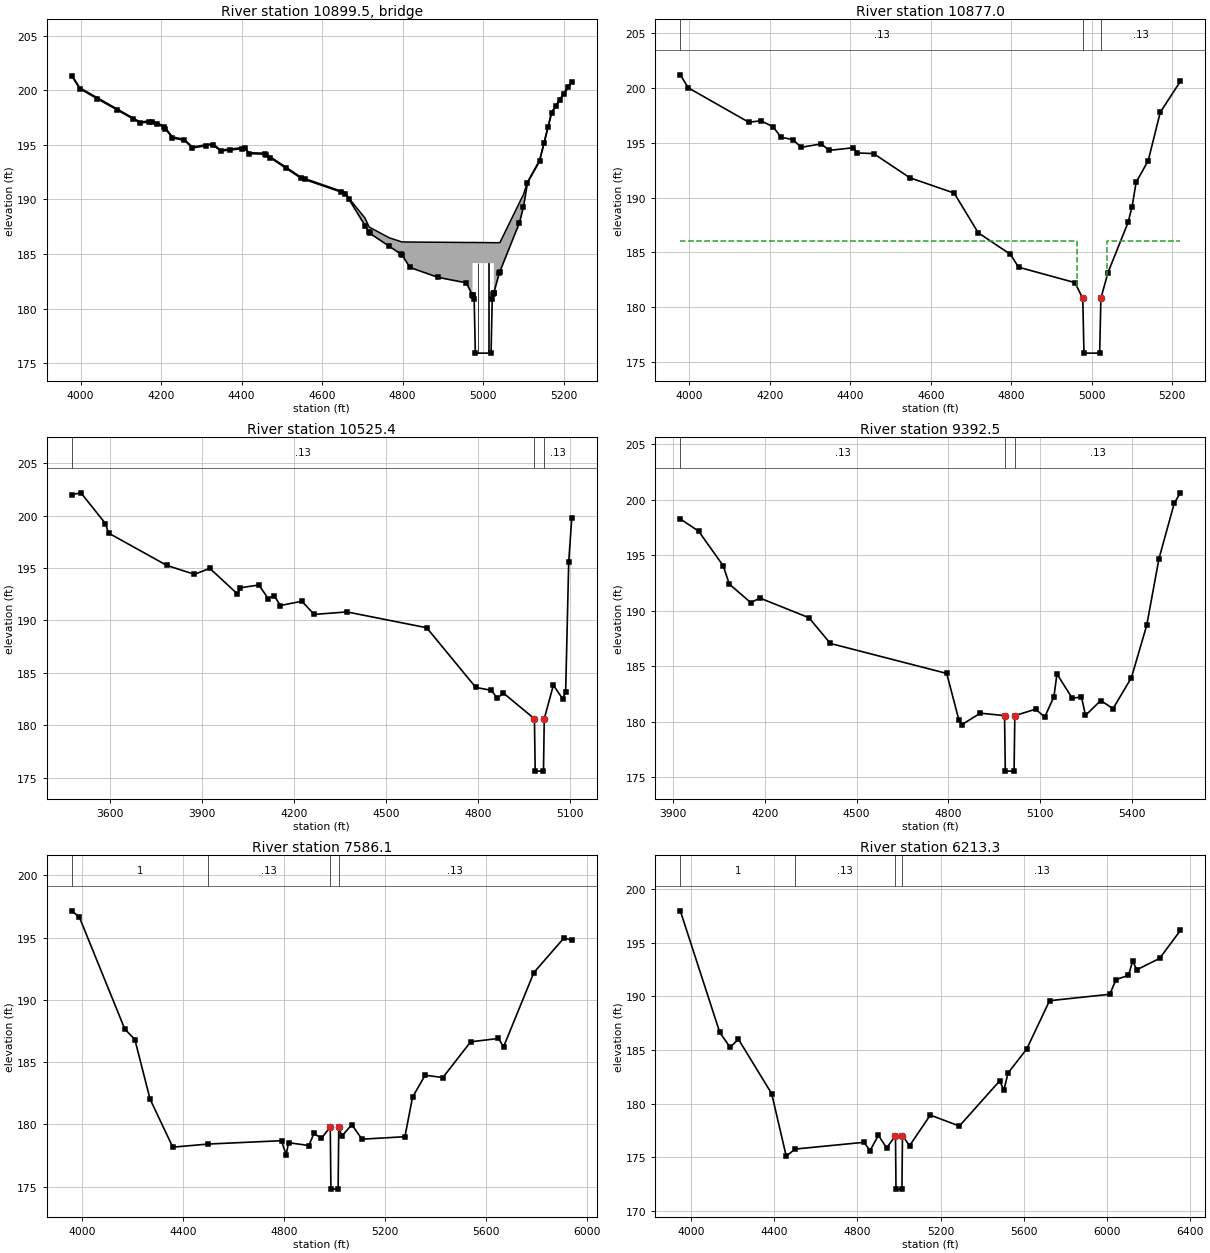
Type RM Length L Ch R = 3 ,10899.5 ,,,
BEGIN DESCRIPTION:
Edwards Rd-TOR
Structure ID: Edwards Rd-Bridge
Approximate Survey Structure
END DESCRIPTION:
Bridge Culvert--1,0,-1,-1, 0
Deck Dist Width WeirC Skew NumUp NumDn MinLoCord MaxHiCord MaxSubmerge Is_Ogee
10,25,2.6,0, 38, 38, , , .95, 0, 1,1,,
    3978    3998    4148    4178    4208    4228    4258    4278    4328    4348
    4408    4418    4458    4548    4658  4666.6  4706.6  4716.6    4718  4766.6
    4798    4818    4888    4958 4973.41  4973.5  5025.5 5026.39  5026.5    5040
  5041.4    5090    5100    5110    5140    5170  5211.4    5220
  201.42  200.24   197.1  197.23   196.7  195.74   195.5  194.81  195.12  194.53
  194.77  194.29  194.24  192.03  190.63  190.11  188.29  187.48  187.45  186.49
  186.11   186.1  186.08  186.06  186.06  186.06  186.04  186.04  186.04  186.04
  186.04  189.71  190.46  191.61  193.59  198.01   200.4  200.83
  201.34  200.15  197.01  197.14  196.61  195.65  195.41  194.72  195.03  194.44
  194.68   194.2  194.15  191.94  190.54  190.02   187.6  186.99  186.91  185.71
  184.94  183.77  182.86  182.36  181.22  184.18  184.16  184.16  181.45  183.26
  183.39  187.86   189.3  191.52   193.5  197.92  200.26  200.75
    3978    3998    4148    4178    4208    4228    4258    4278    4328    4348
    4408    4418    4458    4548    4658  4666.6  4706.6  4716.6    4718  4766.6
    4798    4818    4888    4958 4973.41  4973.5  5025.5 5026.39  5026.5    5040
  5041.4    5090    5100    5110    5140    5170  5211.4    5220
  201.42  200.24   197.1  197.23   196.7  195.74   195.5  194.81  195.12  194.53
  194.77  194.29  194.24  192.03  190.63  190.11  188.29  187.48  187.45  186.49
  186.11   186.1  186.08  186.06  186.06  186.06  186.04  186.04  186.04  186.04
  186.04  189.71  190.46  191.61  193.59  198.01   200.4  200.83
  201.25  200.06  196.92  197.05  196.52  195.56  195.32  194.63  194.94  194.35
  194.59  194.11  194.06  191.85  190.45  189.93  187.51   186.9  186.82  185.62
  184.85  183.68  182.77  182.27  181.13  184.09  184.07  184.07  181.36  183.17
   183.3  187.77  189.21  191.43  193.41  197.83  200.17  200.66
Pier Skew, UpSta & Num, DnSta & Num=  ,4987.2, 2 ,4987.2, 2 , 0 , 0 , 0 ,,
       1       1
  174.92  185.18
       1       1
  174.83  185.09
Pier Skew, UpSta & Num, DnSta & Num=  ,5012.7, 2 ,5012.7, 2 , 0 , 0 , 0 ,,
       1       1
  174.92  185.17
       1       1
  174.83  185.08
Abutment Skew #Up #Dn= , 2 , 2
  4973.3  4974.5
  184.18  181.14
  4973.3  4974.5
  184.09  181.05
Abutment Skew #Up #Dn= , 2 , 2
  5025.5 5026.59
  181.32  184.16
  5025.5 5026.59
  181.23  184.07
BR Coef= 1 , 1 , 0 ,1.25, 0 ,,,.8,0,2,0,
WSPro=,,,, 1 ,,,, 0 ,,,, 0 ,,,,-1 ,-1 ,-1 , 0 , 0 , 0 , 0 , 0
BR U #Sta/Elev= 63
    3978  201.34    3998  200.15  4040.8  199.25  4090.8  198.21  4130.8  197.37
    4148  197.01  4170.8  197.11    4178  197.14  4190.8  196.91    4208  196.61
  4210.8  196.48    4228  195.65    4258  195.41    4278  194.72  4310.8  194.92
    4328  195.03    4348  194.44  4370.8  194.53  4400.8  194.65    4408  194.68
    4418   194.2    4458  194.15  4460.8  194.08  4470.8  193.84  4510.8  192.85
    4548  191.94  4556.6  191.83  4646.6  190.69    4658  190.54  4666.6  190.02
  4706.6   187.6  4716.6  186.99    4718  186.91  4766.6  185.71  4796.6  184.97
    4798  184.94    4818  183.77    4888  182.86    4958  182.36 4973.41  181.22
  4973.5  181.22  4974.5  181.14  4977.5  180.92  4980.5  175.92  5019.5  175.92
  5022.5  180.92  5025.5  181.32 5026.39  181.44  5026.5  181.45    5040  183.26
  5041.4  183.39    5090  187.86    5100   189.3    5110  191.52    5140   193.5
  5151.4  195.18  5161.4  196.65    5170  197.92  5181.4  198.57  5191.4  199.13
  5201.4   199.7  5211.4  200.26    5220  200.75
BR U #Mann= 3
    3978     .13  4977.5    .044  5022.5     .13
BR U Banks=4977.5,5022.5
BR D #Sta/Elev= 63
    3978  201.25    3998  200.06  4040.8  199.16  4090.8  198.12  4130.8  197.28
    4148  196.92  4170.8  197.02    4178  197.05  4190.8  196.82    4208  196.52
  4210.8  196.39    4228  195.56    4258  195.32    4278  194.63  4310.8  194.83
    4328  194.94    4348  194.35  4370.8  194.44  4400.8  194.56    4408  194.59
    4418  194.11    4458  194.06  4460.8  193.99  4470.8  193.75  4510.8  192.76
    4548  191.85  4556.6  191.74  4646.6   190.6    4658  190.45  4666.6  189.93
  4706.6  187.51  4716.6   186.9    4718  186.82  4766.6  185.62  4796.6  184.88
    4798  184.85    4818  183.68    4888  182.77    4958  182.27 4973.41  181.13
  4973.5  181.13  4974.5  181.05  4977.5  180.83  4980.5  175.83  5019.5  175.83
  5022.5  180.83  5025.5  181.23 5026.39  181.35  5026.5  181.36    5040  183.17
  5041.4   183.3    5090  187.77    5100  189.21    5110  191.43    5140  193.41
  5151.4  195.09  5161.4  196.56    5170  197.83  5181.4  198.48  5191.4  199.04
  5201.4  199.61  5211.4  200.17    5220  200.66
BR D #Mann= 3
    3978     .13  4977.5    .044  5022.5     .13
BR D Banks=4977.5,5022.5
BC Design=,, 0 ,, 0 ,,,,,,

Type RM Length L Ch R = 1 ,10877.0 ,351.6,351.6,351.6
BEGIN DESCRIPTION:
Downstream Section of Bridge/Culvert/Weir
END DESCRIPTION:
#Sta/Elev= 30
    3978  201.21    3998  200.02    4148  196.88    4178  197.01    4208  196.48
    4228  195.52    4258  195.28    4278  194.59    4328   194.9    4348  194.31
    4408  194.55    4418  194.07    4458  194.02    4548  191.81    4658  190.41
    4718  186.78    4798  184.81    4818  183.64    4958  182.23  4977.5  180.79
  4980.5  175.79  5019.5  175.79  5022.5  180.79    5040  183.13    5090  187.73
    5100  189.17    5110  191.39    5140  193.37    5170  197.79    5220  200.62
#Mann= 3 , 1 , 0
    3978     .13       0  4977.5    .044       0  5022.5     .13       0
#XS Ineff= 2 , 0
       0    4963  186.05    5037       0  186.05
Permanent Ineff=
       F       F
Bank Sta=4977.5,5022.5
XS Rating Curve= 0
Exp/Cntr=.5,.3

Type RM Length L Ch R = 1 ,10525.4 ,1132.9,1132.9,1132.9
BEGIN DESCRIPTION:
Big Peachtree Creek 8.0
END DESCRIPTION:
#Sta/Elev= 30
  3476.3     202  3506.3  202.18  3586.3  199.25  3596.3  198.34  3786.3  195.25
  3876.3   194.4  3926.3  194.97  4016.3  192.53  4026.3  193.12  4086.3  193.38
  4116.3  192.09  4136.3  192.36  4156.3  191.42  4226.3  191.83  4266.3  190.57
    4373  190.81    4633   189.3    4793   183.6    4843  183.33    4863  182.59
    4883  183.06    4984  180.61  4986.5  175.61  5013.5  175.61    5016  180.61
  5045.7  183.81  5075.7  182.53  5085.7  183.13  5095.7  195.58  5105.7   199.8
#Mann= 3 , 1 , 0
  3476.3     .13       0    4984    .044       0    5016     .13       0
Bank Sta=4984,5016
XS Rating Curve= 0
Exp/Cntr=.3,.1

Type RM Length L Ch R = 1 ,9392.5  ,1806.4,1806.4,1806.4
BEGIN DESCRIPTION:
Big Peachtree Creek 7.0
END DESCRIPTION:
#Sta/Elev= 30
  3924.4  198.28  3984.4  197.17  4064.4  194.06  4084.4  192.41  4154.4  190.74
  4184.4  191.15  4344.4  189.38  4414.4  187.06  4794.4  184.36  4834.4  180.14
  4844.4  179.76  4904.4  180.78  4983.2  180.56  4985.7  175.56  5014.3  175.56
  5016.8  180.56  5084.4  181.14  5114.4  180.43  5144.4  182.26  5154.4  184.31
  5204.4  182.12  5234.4  182.25  5247.5  180.58  5297.5  181.92  5337.5  181.19
  5397.5  183.98  5447.5   188.7  5487.5   194.7  5537.5   199.7  5557.5  200.63
#Mann= 3 , 1 , 0
  3924.4     .13       0  4983.2    .044       0  5016.8     .13       0
Bank Sta=4983.2,5016.8
XS Rating Curve= 0
Exp/Cntr=.3,.1

Type RM Length L Ch R = 1 ,7586.1  ,1372.8,1372.8,1372.8
BEGIN DESCRIPTION:
Big Peachtree Creek 6.0
END DESCRIPTION:
#Sta/Elev= 30
  3960.3  197.15  3990.3  196.66  4170.3  187.66  4210.3  186.81  4270.3  182.03
  4360.3  178.17  4499.9  178.42  4790.3  178.69  4808.5  177.57  4818.5  178.53
  4898.5   178.3  4918.5  179.27  4948.5  178.88  4983.2   179.8  4985.7   174.8
  5014.3   174.8  5016.8   179.8  5028.5  179.05  5068.5  179.98  5108.5  178.81
  5278.5  179.01  5308.5  182.18  5358.5  183.95  5428.5  183.76  5538.5  186.63
  5648.5   186.9  5668.5  186.22  5788.5  192.19  5908.5  194.99  5938.5  194.78
#Mann= 4 , 1 , 0
  3960.3       1       0  4499.9     .13       0  4983.2    .044       0
  5016.8     .13       0
Bank Sta=4983.2,5016.8
XS Rating Curve= 0
Exp/Cntr=.3,.1

Type RM Length L Ch R = 1 ,6213.3  ,1158.8,1158.8,1158.8
BEGIN DESCRIPTION:
Big Peachtree Creek 5.0
END DESCRIPTION:
#Sta/Elev= 30
  3947.1  197.99  4137.1  186.64  4187.1  185.25  4227.1     186  4387.1  180.92
  4457.1  175.09  4499.9  175.75  4830.9  176.38  4860.9  175.61  4900.9  177.03
  4940.9  175.85  4983.2  177.01  4985.7  172.01  5014.3  172.01  5016.8  177.01
  5050.9  176.06  5150.9  178.92  5290.9   177.9  5485.1  182.12  5505.1  181.24
  5525.1  182.85  5615.1  185.09  5725.1   189.6  6015.1   190.2  6045.1  191.57
  6105.1  191.97  6125.1   193.3  6145.1  192.49  6255.1  193.55  6355.1  196.16
#Mann= 4 , 1 , 0
  3947.1       1       0  4499.9     .13       0  4983.2    .044       0
  5016.8     .13       0
Bank Sta=4983.2,5016.8
XS Rating Curve= 0
Exp/Cntr=.3,.1

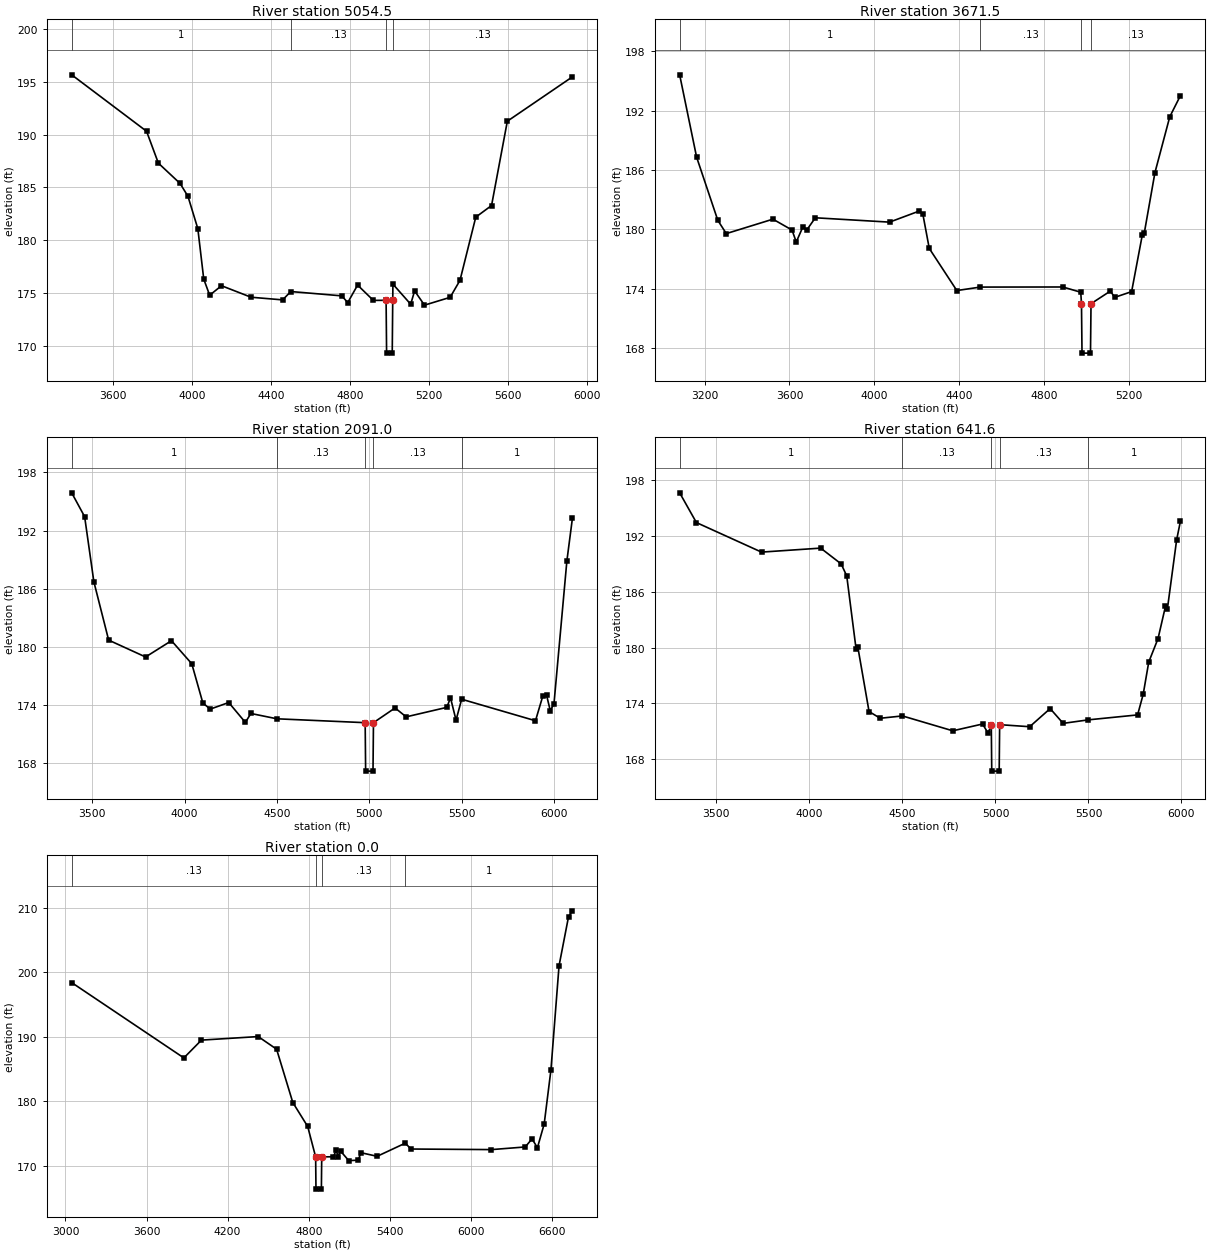
Type RM Length L Ch R = 1 ,5054.5  ,1383,1383,1383
BEGIN DESCRIPTION:
Big Peachtree Creek 4.0
END DESCRIPTION:
#Sta/Elev= 30
  3389.3  195.65  3768.7  190.31  3828.7  187.29  3938.7  185.37  3978.7  184.15
  4028.7  181.09  4058.7  176.32  4088.7  174.79  4148.7  175.69  4298.7   174.6
  4458.7  174.35  4499.9  175.14  4758.7  174.73  4788.7  174.09  4838.7  175.75
  4918.7   174.3  4983.2  174.31  4985.7  169.31  5014.3  169.31  5016.8  174.31
  5017.8  175.84  5107.8  173.94  5127.8   175.2  5177.8  173.85  5307.8  174.59
  5357.8   176.2  5437.8  182.18  5517.8  183.28  5597.8  191.26  5927.8  195.46
#Mann= 4 , 1 , 0
  3389.3       1       0  4499.9     .13       0  4983.2    .044       0
  5016.8     .13       0
Bank Sta=4983.2,5016.8
XS Rating Curve= 0
Exp/Cntr=.3,.1

Type RM Length L Ch R = 1 ,3671.5  ,1580.5,1580.5,1580.5
BEGIN DESCRIPTION:
Big Peachtree Creek 3.0
END DESCRIPTION:
#Sta/Elev= 30
  3082.1  195.62  3162.1  187.29  3262.1   180.9  3302.1  179.56  3522.1  181.02
  3612.1  179.92  3632.1  178.71  3662.1  180.18  3682.1  179.94  3722.1  181.16
  4072.1  180.72  4212.1  181.84  4229.5   181.5  4259.5  178.06  4389.5   173.8
  4499.9  174.15  4889.5  174.16    4974  173.63  4977.5  172.47    4980  167.47
    5020  167.47  5022.5  172.47    5114  173.75    5134  173.11    5214  173.69
    5264  179.38    5274  179.65    5324  185.73    5394  191.38    5444  193.51
#Mann= 4 , 1 , 0
  3082.1       1       0  4499.9     .13       0  4977.5    .044       0
  5022.5     .13       0
Bank Sta=4977.5,5022.5
XS Rating Curve= 0
Exp/Cntr=.3,.1

Type RM Length L Ch R = 1 ,2091.0  ,1449.4,1449.4,1449.4
BEGIN DESCRIPTION:
Big Peachtree Creek 2.0
END DESCRIPTION:
#Sta/Elev= 30
    3389  195.89    3459  193.43    3509  186.71    3589  180.69    3789  178.95
    3929  180.63    4039  178.25    4099   174.2    4139  173.57    4239  174.25
    4329   172.2    4359  173.12  4499.9  172.57  4977.6  172.17  4980.1  167.17
    5020  167.17  5022.5  172.17  5139.5  173.69  5199.5  172.77  5419.5  173.75
  5439.5  174.74  5469.5  172.43  5499.9  174.59  5899.5  172.37  5939.5  174.94
  5959.5  175.01  5979.5  173.42  5999.5  174.09  6069.5  188.87  6099.5  193.27
#Mann= 5 , 1 , 0
    3389       1       0  4499.9     .13       0  4977.6    .044       0
  5022.5     .13       0  5499.9       1       0
Bank Sta=4977.6,5022.5
XS Rating Curve= 0
Exp/Cntr=.3,.1

Type RM Length L Ch R = 1 ,641.6   ,641.59,641.59,641.59
BEGIN DESCRIPTION:
Big Peachtree Creek 1.0
END DESCRIPTION:
#Sta/Elev= 30
  3302.4  196.66  3392.4  193.46  3742.4  190.28  4060.5  190.71  4170.5  189.01
  4200.5  187.72  4250.5  179.89  4260.5  180.02  4320.5  173.12  4380.5   172.4
  4499.9  172.65  4770.5  171.05  4930.5  171.78  4960.5   170.8  4977.5  171.71
    4980  166.71    5020  166.71  5022.5  171.71    5184  171.49    5294  173.44
    5364  171.85  5499.9  172.23    5764  172.76    5794  174.97    5824  178.45
    5874  180.98    5914  184.46    5924  184.14    5974  191.61    5994  193.58
#Mann= 5 , 1 , 0
  3302.4       1       0  4499.9     .13       0  4977.5    .044       0
  5022.5     .13       0  5499.9       1       0
Bank Sta=4977.5,5022.5
XS Rating Curve= 0
Exp/Cntr=.3,.1

Type RM Length L Ch R = 1 ,0.0     ,0,0,0
BEGIN DESCRIPTION:
Big Peachtree Creek 0.5
END DESCRIPTION:
#Sta/Elev= 30
  3046.2   198.4  3876.2  186.72  4006.2  189.48  4426.2  190.03  4562.4  188.07
  4682.4   179.8  4792.4  176.09  4851.3  171.37  4853.8  166.37  4893.8  166.37
  4896.3  171.37  4982.4  171.39  5003.8   172.4  5016.5  171.41  5036.5  172.25
  5096.5  170.79  5166.5  170.86  5186.5  172.02  5306.5  171.46  5514.9   173.5
  5556.5  172.59  6152.5   172.5  6402.5  172.91  6452.5  174.17  6492.5  172.79
  6542.5  176.47  6592.5  184.86  6652.5  201.01  6722.5   208.6  6751.5  209.53
#Mann= 4 , 1 , 0
  3046.2     .13       0  4851.3    .044       0  4896.3     .13       0
  5514.9       1       0
Bank Sta=4851.3,4896.3
XS Rating Curve= 0
Exp/Cntr=.3,.1

Chan Stop Cuts=-1