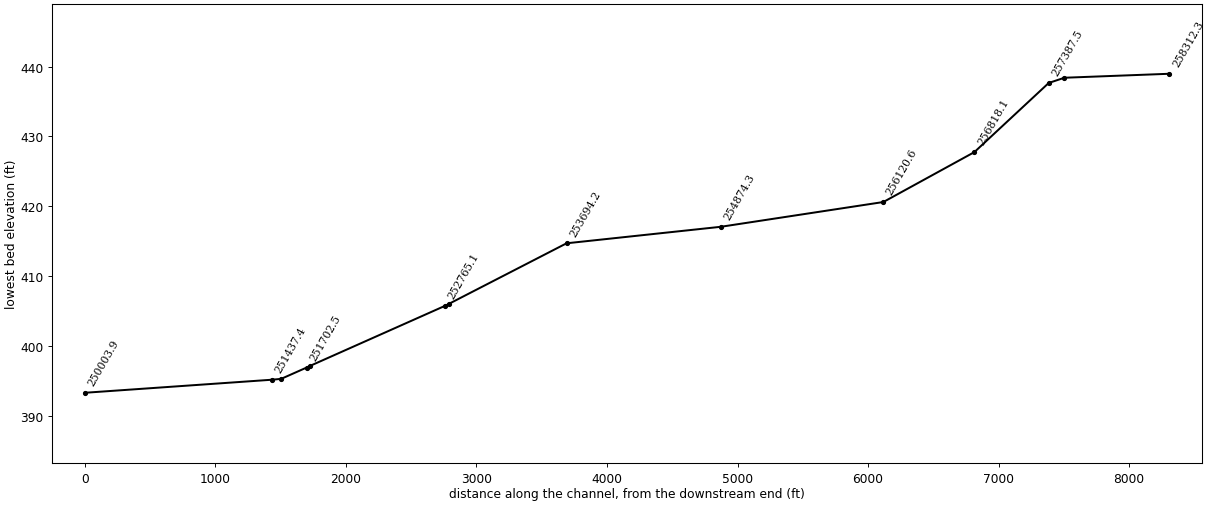
--- 020822_SANDY_CREEK.prj (project) ---

Proj Title=Sandy Creek
Current Plan=p01
Default Exp/Contr=.3,.1
English Units
Geom File=g01
Flow File=f01
Plan File=p01
Y Axis Title=Elevation
X Axis Title(PF)=Main Channel Distance
X Axis Title(XS)=Station
BEGIN DESCRIPTION:
SANDY CREEK
CodeH2 file for Sandy Creek
Generated by WISE at 3:29:07 PM on 8/5/2002 for HEC-RAS.
END DESCRIPTION:
DSS Export Rating Curves= 0
DSS Export Rating Curve Sorted= 0
DSS Export Volume Flow Curves= 0
DXF OffsetX= 0
DXF OffsetY= 0
DXF ScaleX= 1
DXF ScaleY= 10

--- 020822_SANDY_CREEK.p01 (plan) ---

Plan Title=100 Year Single
Version=Version 3.0.1  Mar 2001
Short Identifier=Plan01
Geom File=g01
Flow File=f01
Subcritical Flow
K Sum by GR= 0
Std Step Tol= 0.01
Critical Tol= 0.01
Num of Std Step Trials= 20
Max Error Tol= 0.3
Flow Tol Ratio= 0.001
Split Flow NTrial= 30
Split Flow Tol= 0.02
Split Flow Ratio= 0.02
Log Output Level= 0
Friction Slope Method= 1
Unsteady Friction Slope Method= 2
Parabolic Critical Depth
Global Vel Dist= 0 , 0 , 0
Global Log Level= 0
CheckData=True
Encroach Param=-1 ,10,10, 2
Encroach River=Sandy Creek
Encroach Reach=Reach - 1
Encroach Node=258312.3
       4      .7
Encroach Node=257507.5
       1    4981    5019
Encroach Node=257447.5
       1    4981    5019
Encroach Node=257387.5
       1 4983.84 5016.16
Encroach Node=256818.1
       1    4893    5150
Encroach Node=256120.6
       4      .7
Encroach Node=254874.3
       1    4872    5156
Encroach Node=253694.2
       1    4872    5158
Encroach Node=252790.1
       1    4866    5160
Encroach Node=252777.6
       1    4866    5160
Encroach Node=252765.1
       1    4866    5160
Encroach Node=251725.5
       1    4900    5084
Encroach Node=251714.0
       1    4900    5084
Encroach Node=251702.5
       1    4900    5084
Encroach Node=251507.4
       1  4988.5  5010.5
Encroach Node=251472.4
       1  4988.5  5010.5
Encroach Node=251437.4
       1  4988.5  5010.5
Encroach Node=250003.9
       1    4882    5070
Encroach Node=248540.7
       4      .7
Encroach Node=247526.9
       4      .7
Encroach Node=246849.6
       4      .7
Encroach Node=246666.6
       4      .7
Encroach Node=246654.1
       1    4915    5089
Encroach Node=246641.6
       1 4919.71 5083.57
Encroach Node=246219.1
       1    4973    5021
Encroach Node=246184.1
       1    4973    5021
Encroach Node=246149.1
       1    4973    5021
Encroach Node=245471.6
       4      .7
Encroach Node=244315.3
       4      .7
Encroach Node=243410.8
       4      .7
Encroach Node=242260.2
       4      .7
Encroach Node=241177.4
       4      .7
Encroach Node=240005.3
       4      .7
Encroach Node=238922.9
       1    4817    5066
Encroach Node=237920.2
       1    4955    5030
Encroach Node=236921.9
       1    4875 5009.62
Encroach Node=235800.1
       1    4965    5016
Encroach Node=234821.0
       1    4882    5014
Encroach Node=233680.5
       4      .7
Encroach Node=232509.1
       4      .7
Encroach Node=230915.4
       4      .7
Encroach Node=230082.8
       1    4701    5018
Encroach Node=229348.3
       4      .7
Encroach Node=228743.4
       4      .7
Encroach Node=227934.3
       4      .7
Encroach Node=227163.0
       1    4971    5017
Encroach Node=226524.0
       4      .7
Encroach Node=225750.8
       4      .7
Encroach Node=224048.8
       4      .7
Encroach Node=222623.3
       1    4959    5075
Encroach Node=222612.3
       1    4959    5075
Encroach Node=222601.3
       1    4959    5050
Encroach Node=222437.9
       1    4958    5047
Encroach Node=222415.4
       1    4958    5047
Encroach Node=222392.9
       1    4958    5047
Encroach Node=220389.5
       4      .7
Encroach Node=219861.0
       4      .7
Encroach Node=218838.3
       4      .7
Encroach Node=218126.8
       4      .7
Encroach Node=217118.4
       4      .7
Encroach Node=215999.1
       4      .7
Encroach Node=214993.1
       4      .7
Encroach Node=213632.9
       4      .7
Encroach Node=212790.2
       4      .7
Encroach Node=211837.7
       4      .7
Encroach Node=211110.1
       4      .7
Encroach Node=209933.2
       1    4860    5102
Encroach Node=209921.7
       1    4860    5102
Encroach Node=209910.2
       1    4860    5102
Encroach Node=209611.2
       1    4944    5050
Encroach Node=209591.2
       1    4944    5050
Encroach Node=209571.2
       1    4944    5050
Encroach Node=209187.1
       4      .7
Encroach Node=208250.9
       4      .7
Encroach Node=207137.4
       4      .7
Encroach Node=206120.7
       4      .7
Encroach Node=204749.1
       4      .7
Encroach Node=203659.7
       4      .7
Encroach Node=201812.7
       4      .7
Encroach Node=200840.5
       4      .7
Encroach Node=199410.4
       4      .7
Encroach Node=198205.6
       4      .7
Encroach Node=196989.6
       4      .7
Encroach Node=195482.2
       4      .7
Encroach Node=194343.2
       4      .7
Encroach Node=193122.3
       4      .7
Encroach Node=191989.3
       4      .7
Encroach Node=191118.6
       4      .7
Encroach Node=190146.8
       4      .7
Encroach Node=190127.8
       4      .7
Encroach Node=190108.8
       4      .7
Encroach Node=188820.7
       1    4850    5086
Encroach Node=188794.2
       1    4850    5086
Encroach Node=188767.7
       1    4850    5086
Encroach Node=188226.6
       4      .7
Encroach Node=187487.1
       1    4769  5027.7
Encroach Node=186654.9
       4      .7
Encroach Node=185053.0
       4      .7
Encroach Node=183077.9
       4      .7
Encroach Node=182105.7
       4      .7
Encroach Node=181262.2
       4      .7
Encroach Node=180345.9
       1    4747  5030.3
Encroach Node=179650.0
       1    4653    5031
Encroach Node=177837.4
       1    4782    5031
Encroach Node=177004.9
       4      .7
Encroach Node=175910.8
       4      .7
Encroach Node=174907.4
       1    4771    5137
Encroach Node=173732.7
       4      .7
Encroach Node=172003.0
       4      .7
Encroach Node=171157.2
       4      .7
Encroach Node=170001.6
       4      .7
Encroach Node=168785.0
       4      .7
Encroach Node=167719.4
       4      .7
Encroach Node=167310.5
       1    4932    5091
Encroach Node=167285.5
       1    4932    5091
Encroach Node=167260.5
       1    4932    5091
Encroach Node=166795.2
       4      .7
Encroach Node=165952.4
       4      .7
Encroach Node=165208.9
       4      .7
Encroach Node=164199.1
       4      .7
Encroach Node=163122.9
       4      .7
Encroach Node=162003.3
       4      .7
Encroach Node=161032.5
       4      .7
Encroach Node=160252.9
       4      .7
Encroach Node=159487.8
       4      .7
Encroach Node=157259.3
       4      .7
Encroach Node=155471.6
       4      .7
Encroach Node=154453.1
       4      .7
Encroach Node=153113.3
       4      .7
Encroach Node=152325.8
       4      .7
Encroach Node=151667.5
       4      .7
Encroach Node=150754.0
       4      .7
Encroach Node=150373.5
       1    4912    5065
Encroach Node=150353.0
       1    4912    5065
Encroach Node=150332.5
       1    4912    5065
Encroach Node=150189.6
       4      .7
Encroach Node=148659.5
       4      .7
Encroach Node=148054.9
       4      .7
Encroach Node=147368.9
       4      .7
Encroach Node=145364.2
       4      .7
Encroach Node=144898.0
       4      .7
Encroach Node=144279.4
       4      .7
Encroach Node=143629.4
       4      .7
Encroach Node=142969.9
       4      .7
Encroach Node=142373.5
       1    4556  5034.8
Encroach Node=141326.4
       4      .7
Encroach Node=140895.0
       4      .7
Encroach Node=140180.0
       4      .7
Encroach Node=139957.4
       1    4930    5098
Encroach Node=139932.4
       1    4930    5098
Encroach Node=139907.4
       1    4930    5098
Encroach Node=139004.0
       4      .7
Encroach Node=137554.6
       4      .7
Encroach Node=136142.2
       4      .7
Encroach Node=135224.6
       4      .7
Encroach Node=133969.3
       4      .7
Encroach Node=132157.1
       4      .7
Encroach Node=131088.2
       4      .7
Encroach Node=130194.1
       4      .7
Encroach Node=128598.7
       4      .7
Encroach Node=127207.0
       4      .7
Encroach Node=126145.9
       4      .7
Encroach Node=125274.8
       4      .7
Encroach Node=123834.6
       4      .7
Encroach Node=122788.6
       1    4908    5078
Encroach Node=122764.1
       1    4908    5078
Encroach Node=122739.6
       1    4908    5078
Encroach Node=122220.2
       4      .7
Encroach Node=121208.4
       4      .7
Encroach Node=119330.5
       4      .7
Encroach Node=117990.5
       4      .7
Encroach Node=117224.6
       4      .7
Encroach Node=116106.8
       4      .7
Encroach Node=115284.2
       4      .7
Encroach Node=113184.8
       4      .7
Encroach Node=110996.1
       4      .7
Encroach Node=109997.7
       4      .7
Encroach Node=108567.0
       4      .7
Encroach Node=107000.0
       4      .7
Encroach Node=105503.3
       4      .7
Encroach Node=105482.8
       4      .7
Encroach Node=105462.3
       4      .7
Encroach Node=104406.3
       4      .7
Encroach Node=103857.9
       4      .7
Encroach Node=101173.7
       4      .7
Encroach Node=100457.2
       4      .7
Encroach Node=100009.9
       4      .7
Encroach Node=99089.2
       4      .7
Encroach Node=98226.8
       4      .7
Encroach Node=96870.8
       4      .7
Encroach Node=95782.9
       4      .7
Encroach Node=94702.0
       1    4917    5082
Encroach Node=94675.5
       1    4917    5082
Encroach Node=94649.0
       1    4917    5082
Encroach Node=94101.3
       4      .7
Encroach Node=93200.8
       4      .7
Encroach Node=92014.7
       4      .7
Encroach Node=90518.1
       4      .7
Encroach Node=89793.4
       4      .7
Encroach Node=87069.3
       4      .7
Encroach Node=85954.6
       4      .7
Encroach Node=84147.9
       4      .7
Encroach Node=82098.9
       4      .7
Encroach Node=79973.7
       4      .7
Encroach Node=78990.2
       4      .7
Encroach Node=78202.2
       4      .7
Encroach Node=76991.0
       4      .7
Encroach Node=75838.2
       4      .7
Encroach Node=74842.8
       4      .7
Encroach Node=74354.6
       4      .7
Encroach Node=73188.7
       4      .7
Encroach Node=72177.6
       4      .7
Encroach Node=71260.4
       4      .7
Encroach Node=70029.5
       4      .7
Encroach Node=68169.6
       4      .7
Encroach Node=68144.6
       4      .7
Encroach Node=68119.6
       4      .7
Encroach Node=66561.5
       4      .7
Encroach Node=65643.5
       4      .7
Encroach Node=63900.8
       4      .7
Encroach Node=61942.5
       4      .7
Encroach Node=61000.0
       4      .7
Encroach Node=59247.7
       4      .7
Encroach Node=58303.4
       4      .7
Encroach Node=57404.8
       4      .7
Encroach Node=55463.7
       4      .7
Encroach Node=54341.9
       4      .7
Encroach Node=53000.0
       4      .7
Encroach Node=50653.5
       4      .7
Encroach Node=49518.2
       4      .7
Encroach Node=48612.4
       4      .7
Encroach Node=47829.0
       4      .7
Encroach Node=46829.6
       4      .7
Encroach Node=46000.0
       4      .7
Encroach Node=45070.3
       4      .7
Encroach Node=44006.9
       4      .7
Encroach Node=42405.7
       4      .7
Encroach Node=41860.0
       4      .7
Encroach Node=40546.9
       1    4917 5082.55
Encroach Node=40523.4
       1    4917 5082.55
Encroach Node=40499.9
       1    4917 5082.55
Encroach Node=39739.4
       4      .7
Encroach Node=38650.2
       4      .7
Encroach Node=37218.0
       4      .7
Encroach Node=35986.0
       4      .7
Encroach Node=34986.6
       4      .7
Encroach Node=33868.0
       4      .7
Encroach Node=32987.0
       4      .7
Encroach Node=31917.2
       4      .7
Encroach Node=31142.6
       4      .7
Encroach Node=29320.0
       4      .7
Encroach Node=27475.0
       4      .7
Encroach Node=26372.8
       4      .7
Encroach Node=25221.8
       4      .7
Encroach Node=23988.9
       4      .7
Encroach Node=22545.7
       4      .7
Encroach Node=21563.3
       4      .7
Encroach Node=21541.8
       4      .7
Encroach Node=21520.3
       4      .7
Encroach Node=20992.7
       4      .7
Encroach Node=20212.0
       4      .7
Encroach Node=18735.1
       4      .7
Encroach Node=15995.4
       4      .7
Encroach Node=14414.3
       4      .7
Encroach Node=12258.1
       4      .7
Encroach Node=11098.4
       4      .7
Encroach Node=10000.0
       4      .7
Encroach Node=8131.5
       4      .7
Encroach Node=6981.9
       4      .7
Encroach Node=5247.0
       4      .7
Encroach Node=3998.4
       4      .7
Encroach Node=2861.0
       4      .7
Encroach Node=2000.0
       4      .7
Encroach Node=368.4
       4      .7
Encroach Node=342.9
       4      .7
Encroach Node=317.4
       4      .7
Encroach Node=212.4
       4      .7
Computation Interval=1HOUR
Output Interval=1HOUR
Run HTab= 0
Run UNet= 0
Run PostProcess= 0
UNET Theta= 1
UNET ZTol= 0.02
UNET ZSATol= 0.1
UNET MxIter= 20
UNET MaxInSteps= 20
UNET DtIC= 0
UNET DtMin= 0
UNET MaxCRTS= 20
UNET WFStab= 2
UNET SFStab= 1
UNET WFX= 1
UNET SFX= 1
UNET Convert EG Bridges=-1
UNET Use Existing IB Tables=-1
Instantaneous Interval=1HOUR
Write IC File= 0
Write Velocity= 0
Write Detailed= 0

--- 020822_SANDY_CREEK.f01 (steady flow) ---

Flow Title= 100 Year Single
Version=Version 3.0.1  Mar 2001
Number of Profiles= 2
Profile Names=100-Year,AFW
River Rch & RM=Sandy Creek,Reach - 1       ,258312.3
     724     724
River Rch & RM=Sandy Creek,Reach - 1       ,256120.6
     942     942
River Rch & RM=Sandy Creek,Reach - 1       ,254874.3
    1910    1910
River Rch & RM=Sandy Creek,Reach - 1       ,248540.7
    2890    2890
River Rch & RM=Sandy Creek,Reach - 1       ,243410.8
    2990    2990
River Rch & RM=Sandy Creek,Reach - 1       ,234821
    3370    3370
River Rch & RM=Sandy Creek,Reach - 1       ,232509.1
    4260    4260
River Rch & RM=Sandy Creek,Reach - 1       ,224048.8
    4710    4710
River Rch & RM=Sandy Creek,Reach - 1       ,222392.9
    5370    5370
River Rch & RM=Sandy Creek,Reach - 1       ,211837.7
    6710    6710
River Rch & RM=Sandy Creek,Reach - 1       ,207137.4
    7130    7130
River Rch & RM=Sandy Creek,Reach - 1       ,200840.5
    7380    7380
River Rch & RM=Sandy Creek,Reach - 1       ,194343.2
    7630    7630
River Rch & RM=Sandy Creek,Reach - 1       ,183077.9
    8150    8150
River Rch & RM=Sandy Creek,Reach - 1       ,177837.4
    8440    8440
River Rch & RM=Sandy Creek,Reach - 1       ,167719.4
    8640    8640
River Rch & RM=Sandy Creek,Reach - 1       ,157259.3
    9680    9680
River Rch & RM=Sandy Creek,Reach - 1       ,155471.6
    9870    9870
River Rch & RM=Sandy Creek,Reach - 1       ,148659.5
    9980    9980
River Rch & RM=Sandy Creek,Reach - 1       ,139907.4
   10400   10400
River Rch & RM=Sandy Creek,Reach - 1       ,130194.1
   10500   10500
River Rch & RM=Sandy Creek,Reach - 1       ,119330.5
   10800   10800
River Rch & RM=Sandy Creek,Reach - 1       ,113184.8
   11000   11000
River Rch & RM=Sandy Creek,Reach - 1       ,105462.3
   11100   11100
River Rch & RM=Sandy Creek,Reach - 1       ,101173.7
   11300   11300
River Rch & RM=Sandy Creek,Reach - 1       ,92014.7
   11400   11400
River Rch & RM=Sandy Creek,Reach - 1       ,78990.2
   11500   11500
River Rch & RM=Sandy Creek,Reach - 1       ,68119.6
   11500   11500
River Rch & RM=Sandy Creek,Reach - 1       ,63900.8
   11700   11700
River Rch & RM=Sandy Creek,Reach - 1       ,40546.9
   11800   11800
River Rch & RM=Sandy Creek,Reach - 1       ,35986
   12100   12100
River Rch & RM=Sandy Creek,Reach - 1       ,27475
   12200   12200
River Rch & RM=Sandy Creek,Reach - 1       ,11098.4
   12300   12300
Boundary for River Rch & Prof#=Sandy Creek,Reach - 1       , 1
Up Type= 0
Dn Type= 3
Dn Slope=.0004
Boundary for River Rch & Prof#=Sandy Creek,Reach - 1       , 2
Up Type= 0
Dn Type= 1
Dn Known WS=155.95
DSS Import GetInterval= 0
DSS Import GetPeak= 0
DSS Import FillOption= 0

--- 020822_SANDY_CREEK.g01 (geometry) ---

Geom Title=Geom 01 by CodeH2 for Windows

River Reach=Sandy Creek,Reach - 1
Reach XY= 30
   .053715351132   .625776066469   .073649189435   .577233750814
   .137564361135   .529132103413   .184479353176   .511554569472
   .247385258309   .518724453532   .323705875629   .363933465690
   .355290118321   .321438481127   .394520714732   .307061792038
   .389229526512   .283211686699   .428371078234   .262786474142
   .423045771395   .251033485799   .445415745208   .246665952335
   .450348022376   .226004431564   .490779355959   .227530311463
   .517162155709   .195172269713   .552033345474   .213414941568
   .653786135162   .189379460737   .678180527046   .203051779003
   .715087484402   .135535446669   .745300677064   .120174361875
   .756590787148   .140202621470   .774861062155   .099023410571
   .790419012079   .112723472109   .823862894627   .071150180657
   .845802077094   .078889222123   .847612745873   .050000000000
   .895038886663   .068823879368   .908571577811   .096483710284
   .930188279784   .081346112950   .940683076704   .106387625518

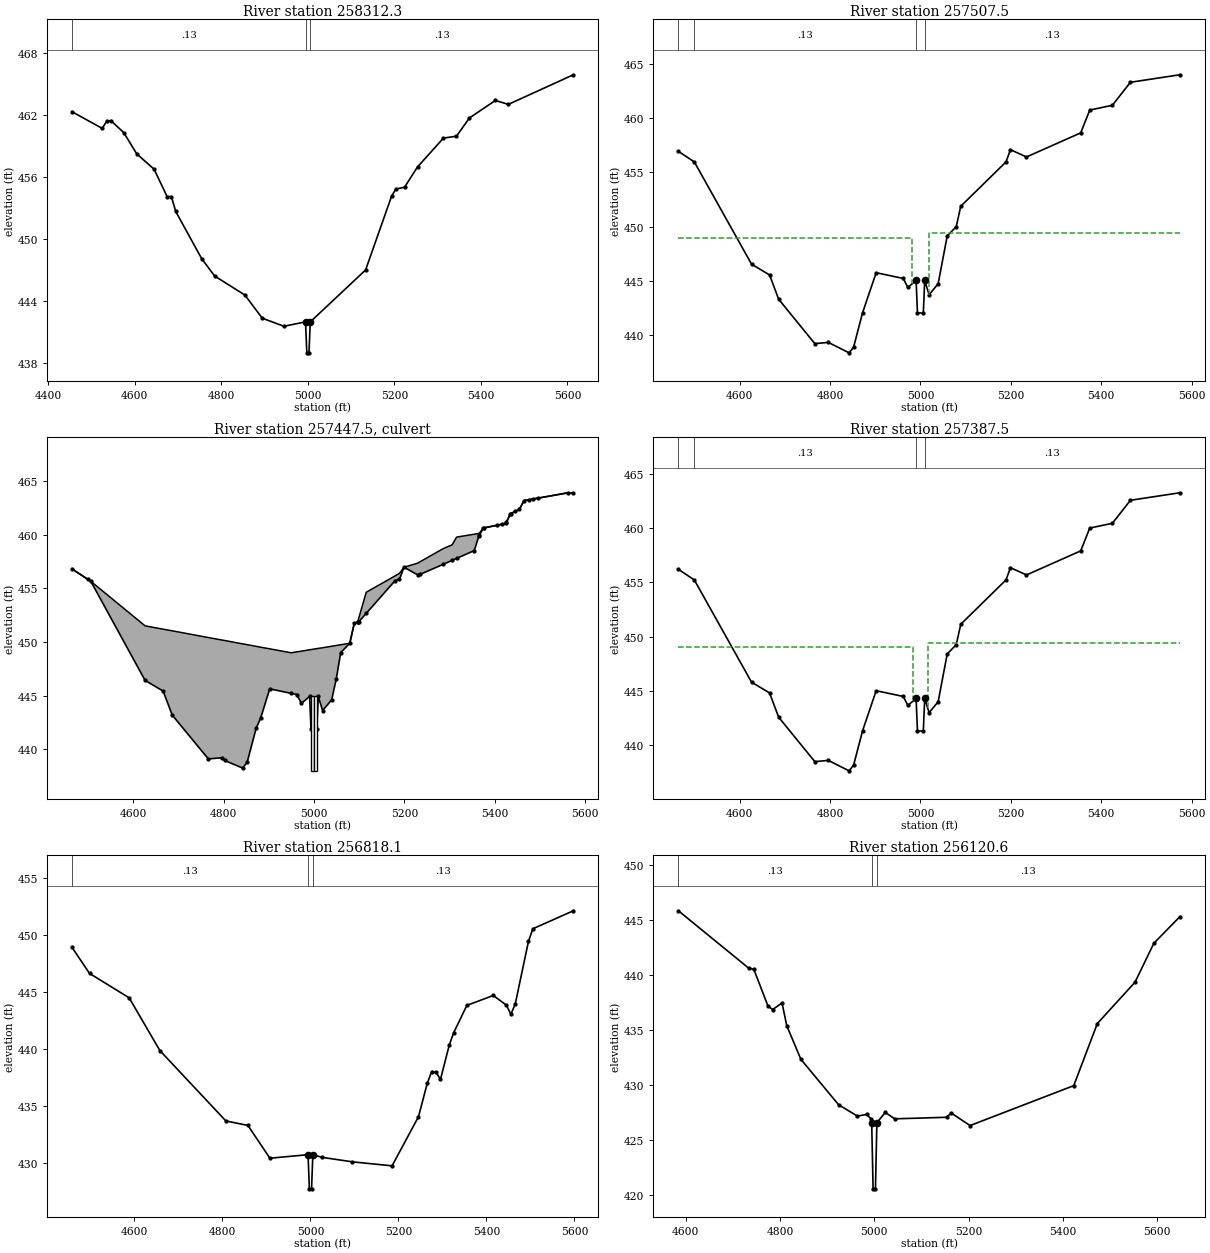
Type RM Length L Ch R = 1 ,258312.3,804.8,804.8,804.8
BEGIN DESCRIPTION:
Sandy Creek 258.0
END DESCRIPTION:
#Sta/Elev= 30
  4454.5  462.35  4524.5  460.73  4534.5   461.4  4544.5  461.49  4574.5  460.31
  4604.5  458.25  4644.5  456.77  4674.5  454.12  4684.5  454.11  4694.5  452.67
  4754.5  448.09  4784.5  446.41  4854.5  444.56  4894.5  442.32  4944.5  441.54
  4994.5  441.96  4997.5  438.96  5002.5  438.96  5005.5  441.96  5133.4     447
  5193.4  454.15  5203.4  454.85  5223.4  455.02  5253.4  456.99  5313.4  459.79
  5343.4  459.97  5373.4  461.74  5433.4  463.44  5463.4  463.06  5613.6  465.93
#Mann= 3 , 1 , 0
 4454.50    0.13       0  4994.5   0.042       0  5005.5    0.13       0
Bank Sta=4994.50,5005.50
Exp/Cntr=0.5,0.3

Type RM Length L Ch R = 1 ,257507.5,120,120,120
BEGIN DESCRIPTION:
Upstream Section of Bridge/Culvert/Weir
END DESCRIPTION:
#Sta/Elev= 30
  4464.6  456.95  4499.9  455.97  4626.4  446.56  4666.4  445.56  4686.4  443.33
  4766.4  439.24  4796.4  439.35  4842.2  438.39  4852.2  438.91  4872.2   442.1
  4902.2  445.77  4962.2  445.24  4972.2  444.41  4990.5  445.06  4993.5  442.06
  5006.5  442.06  5009.5  445.06  5019.3  443.75  5039.3  444.75  5059.3  449.15
  5079.3  450.01  5089.3  451.89  5189.3  455.97  5199.3   457.1  5234.7  456.43
  5354.7  458.65  5374.7  460.75  5424.7  461.19  5464.7  463.31  5573.9     464
#Mann= 4 , 1 , 0
 4464.60       1       0  4499.9    0.13       0  4990.5   0.042       0
  5009.5    0.13       0
#XS Ineff= 2 , 0
       0  4980.5     449  5019.5       0  449.41
Bank Sta=4990.50,5009.50
Exp/Cntr=0.5,0.3

Type RM Length L Ch R = 2 ,257447.5,,,
BEGIN DESCRIPTION:
US 1 Bypass-TOR
Structure ID: US 1 South
Approximate Survey Structure
END DESCRIPTION:
Bridge Culvert--1,0,-1,-1, 0
Deck Dist Width WeirC Skew NumUp NumDn MinLoCord MaxHiCord MaxSubmerge Is_Ogee
10,100,2.6,,58,58,,,0.95,0,1,1,,
  4464.6  4499.9  4506.4  4626.4  4666.4  4686.4  4766.4  4796.4  4802.2  4842.2
  4852.2  4872.2  4882.2  4902.2  4949.6  4962.2  4972.2  4990.5  4993.5  5006.5
  5009.5  5019.3  5039.3  5049.3  5059.3  5079.3  5089.3  5096.6  5097.6  5099.3
  5115.7  5179.3  5189.3  5199.3  5229.3  5234.7  5285.7  5305.7  5315.7  5354.7
  5364.7  5365.7  5374.7  5375.7  5405.7  5415.7  5424.7  5425.7  5434.7  5435.7
  5445.7  5454.7  5464.7  5475.7  5485.7  5495.7  5562.3  5573.9
  456.82  455.84  455.66  451.51   451.2  451.05  450.42  450.19  450.15  449.83
  449.76   449.6  449.52  449.37     449  449.09  449.15  449.28   449.3  449.39
  449.41  449.47  449.61  449.68  449.75  449.88  451.76  451.85     452  452.25
  454.64  456.16   456.4  456.97  457.35  457.48   458.7  459.06  459.78  460.05
  460.12  460.13  460.62  460.63  460.89  460.98  461.06  461.15  461.95  461.97
  462.18  462.37  463.18  463.26  463.34  463.41  463.91  463.87
  456.82  455.84  455.66  446.43  445.43   443.2  439.11  439.22  438.97  438.26
  438.78  441.97  442.92  445.64  445.22  445.11  444.28  444.93  441.93  441.93
  444.93  443.62  444.62  446.54  449.02  449.88  451.76  451.85  451.87  451.89
  452.67  455.71  455.84  456.97  456.27   456.3  457.24  457.61   457.8  458.52
  459.85  459.93  460.62  460.63  460.89  460.98  461.06  461.15  461.95  461.97
  462.18  462.37  463.18  463.26  463.34  463.41  463.91  463.87
  4464.6  4499.9  4506.4  4626.4  4666.4  4686.4  4766.4  4796.4  4802.2  4842.2
  4852.2  4872.2  4882.2  4902.2  4949.6  4962.2  4972.2  4990.5  4993.5  5006.5
  5009.5  5019.3  5039.3  5049.3  5059.3  5079.3  5089.3  5096.6  5097.6  5099.3
  5115.7  5179.3  5189.3  5199.3  5229.3  5234.7  5285.7  5305.7  5315.7  5354.7
  5364.7  5365.7  5374.7  5375.7  5405.7  5415.7  5424.7  5425.7  5434.7  5435.7
  5445.7  5454.7  5464.7  5475.7  5485.7  5495.7  5562.3  5573.9
  456.24  455.26  455.08  451.51   451.2  451.05  450.42  450.19  450.15  449.83
  449.76   449.6  449.52  449.37     449  449.09  449.15  449.28   449.3  449.39
  449.41  449.47  449.61  449.68  449.75  449.88  451.18  451.27     452  452.25
  454.64  456.16   456.4  456.64  457.35  457.48   458.7  459.06  459.78  460.05
  460.12  460.13  460.04  460.05  460.31   460.4  460.48  460.57  461.37  461.39
   461.6  461.79   462.6  462.68  462.76  462.83  463.33  463.29
  456.24  455.26  455.08  445.85  444.85  442.62  438.53  438.64  438.39  437.68
   438.2  441.39  442.34  445.06  444.64  444.53   443.7  444.35  441.35  441.35
  444.35  443.04  444.04  445.96  448.44   449.3  451.18  451.27  451.29  451.31
  452.09  455.13  455.26  456.39  455.69  455.72  456.66  457.03  457.22  457.94
  459.27  459.35  460.04  460.05  460.31   460.4  460.48  460.57  461.37  461.39
   461.6  461.79   462.6  462.68  462.76  462.83  463.33  463.29
BR Coef= 1 , 0 , 0 ,1.25, 0 ,,,0.8,-1,2,0,
Wspro=,,,, 1 ,,,, 0 ,,,, 0 ,,,,-1 ,-1 ,-1 , 0 , 0 , 0 , 0 , 0
Culvert=2,7.0,6.0,100.0,0.015,0.4,1.0,8,1,438.00,4996.50,437.50,4996.50,Culvert #1  ,0,10
Culvert=2,7.0,6.0,100.0,0.015,0.4,1.0,8,1,438.00,5003.50,437.50,5003.50,Culvert #2  ,0,10
BC Design=,, 0 ,, 0 ,,,,,,
BR U #Sta/Elev= 58
  4464.6  456.82  4499.9  455.84  4506.4  455.66  4626.4  446.43  4666.4  445.43
  4686.4   443.2  4766.4  439.11  4796.4  439.22  4802.2  438.97  4842.2  438.26
  4852.2  438.78  4872.2  441.97  4882.2  442.92  4902.2  445.64  4949.6  445.22
  4962.2  445.11  4972.2  444.28  4990.5  444.93  4993.5  441.93  5006.5  441.93
  5009.5  444.93  5019.3  443.62  5039.3  444.62  5049.3  446.54  5059.3  449.02
  5079.3  449.88  5089.3  451.76  5096.6  451.85  5097.6  451.87  5099.3  451.89
  5115.7  452.67  5179.3  455.71  5189.3  455.84  5199.3  456.97  5229.3  456.27
  5234.7   456.3  5285.7  457.24  5305.7  457.61  5315.7   457.8  5354.7  458.52
  5364.7  459.85  5365.7  459.93  5374.7  460.62  5375.7  460.63  5405.7  460.89
  5415.7  460.98  5424.7  461.06  5425.7  461.15  5434.7  461.95  5435.7  461.97
  5445.7  462.18  5454.7  462.37  5464.7  463.18  5475.7  463.26  5485.7  463.34
  5495.7  463.41  5562.3  463.91  5573.9  463.87
BR U #Mann= 4
 4464.60       1  4499.9    0.13  4990.5   0.015  5009.5    0.13
BR U Banks=4990.50,5009.50
BR D #Sta/Elev= 58
  4464.6  456.24  4499.9  455.26  4506.4  455.08  4626.4  445.85  4666.4  444.85
  4686.4  442.62  4766.4  438.53  4796.4  438.64  4802.2  438.39  4842.2  437.68
  4852.2   438.2  4872.2  441.39  4882.2  442.34  4902.2  445.06  4949.6  444.64
  4962.2  444.53  4972.2   443.7  4990.5  444.35  4993.5  441.35  5006.5  441.35
  5009.5  444.35  5019.3  443.04  5039.3  444.04  5049.3  445.96  5059.3  448.44
  5079.3   449.3  5089.3  451.18  5096.6  451.27  5097.6  451.29  5099.3  451.31
  5115.7  452.09  5179.3  455.13  5189.3  455.26  5199.3  456.39  5229.3  455.69
  5234.7  455.72  5285.7  456.66  5305.7  457.03  5315.7  457.22  5354.7  457.94
  5364.7  459.27  5365.7  459.35  5374.7  460.04  5375.7  460.05  5405.7  460.31
  5415.7   460.4  5424.7  460.48  5425.7  460.57  5434.7  461.37  5435.7  461.39
  5445.7   461.6  5454.7  461.79  5464.7   462.6  5475.7  462.68  5485.7  462.76
  5495.7  462.83  5562.3  463.33  5573.9  463.29
BR D #Mann= 4
 4464.60       1  4499.9    0.13  4990.5   0.015  5009.5    0.13
BR D Banks=4990.50,5009.50

Type RM Length L Ch R = 1 ,257387.5,569.4,569.4,569.4
BEGIN DESCRIPTION:
Downstream Section of Bridge/Culvert/Weir
END DESCRIPTION:
#Sta/Elev= 30
  4464.6   456.2  4499.9  455.22  4626.4  445.81  4666.4  444.81  4686.4  442.58
  4766.4  438.49  4796.4   438.6  4842.2  437.64  4852.2  438.16  4872.2  441.35
  4902.2  445.02  4962.2  444.49  4972.2  443.66  4990.5  444.31  4993.5  441.31
  5006.5  441.31  5009.5  444.31  5019.3     443  5039.3     444  5059.3   448.4
  5079.3  449.26  5089.3  451.14  5189.3  455.22  5199.3  456.35  5234.7  455.68
  5354.7   457.9  5374.7     460  5424.7  460.44  5464.7  462.56  5573.9  463.25
#Mann= 4 , 1 , 0
 4464.60       1       0  4499.9    0.13       0  4990.5   0.042       0
  5009.5    0.13       0
#XS Ineff= 2 , 0
       0 4983.83     449 5016.17       0  449.41
Bank Sta=4990.50,5009.50
Exp/Cntr=0.5,0.3

Type RM Length L Ch R = 1 ,256818.1,697.5,697.5,697.5
BEGIN DESCRIPTION:
Sandy Creek 257.0
END DESCRIPTION:
#Sta/Elev= 30
  4457.8  448.96  4497.8  446.66  4587.8  444.52  4657.8  439.88  4807.8   433.7
  4857.8  433.31  4907.8  430.43  4994.5  430.74  4997.5  427.74  5002.5  427.74
  5005.4  430.74  5005.5  430.74  5025.5  430.51  5095.5  430.11  5185.5  429.76
  5245.5  434.07  5265.5  437.01  5275.5  438.04  5285.5  437.98  5295.5  437.35
  5315.5  440.37  5325.5  441.45  5355.5  443.85  5415.5  444.72  5445.5  443.87
  5455.5  443.06  5465.5  443.98  5495.5  449.47  5505.5  450.58  5597.5  452.16
#Mann= 3 , 1 , 0
 4457.80    0.13       0  4994.5   0.042       0  5005.4    0.13       0
Bank Sta=4994.50,5005.40
Exp/Cntr=0.3,0.1

Type RM Length L Ch R = 1 ,256120.6,1246.3,1246.3,1246.3
BEGIN DESCRIPTION:
Sandy Creek 256.0
END DESCRIPTION:
#Sta/Elev= 26
  4584.2  445.81  4734.2  440.58  4744.2  440.51  4774.2  437.19  4784.2  436.85
  4804.2  437.45  4814.2  435.39  4844.2  432.34  4924.2  428.22  4964.2  427.19
  4984.2  427.34  4993.4  426.91  4994.5  426.59  4997.5  420.59  5002.5  420.59
  5005.5  426.59  5023.4  427.52  5043.4  426.94  5153.4  427.08  5163.4  427.46
  5203.4  426.33  5423.4  429.95  5473.4  435.58  5553.4  439.33  5593.4  442.86
  5648.5  445.27
#Mann= 3 , 1 , 0
 4584.20    0.13       0  4994.5   0.042       0  5005.5    0.13       0
Bank Sta=4994.50,5005.50
Exp/Cntr=0.3,0.1

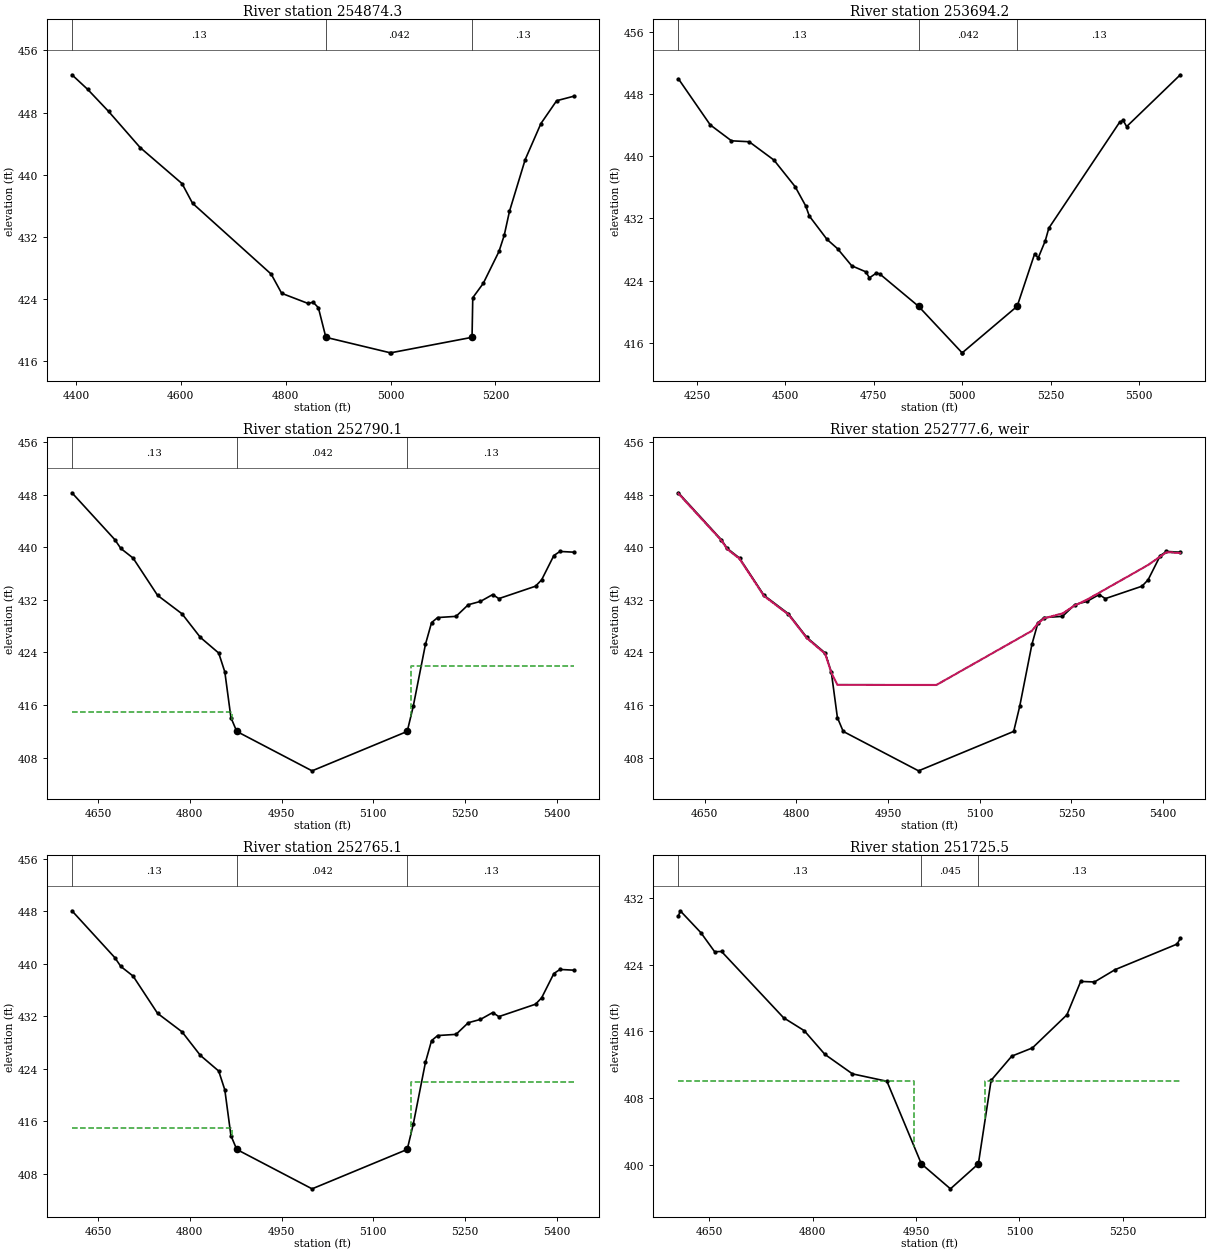
Type RM Length L Ch R = 1 ,254874.3,1180.1,1180.1,1180.1
BEGIN DESCRIPTION:
Sandy Creek 255.0
END DESCRIPTION:
#Sta/Elev= 24
  4392.4  452.86  4422.4  450.98  4462.4  448.13  4522.4  443.49  4602.4  438.84
  4622.4  436.31  4772.4  427.18  4792.4  424.71  4842.4  423.41  4852.4  423.56
  4862.4  422.86  4876.7  419.04  4999.9  417.04  5000.1  417.04  5155.5  419.04
  5156.9  424.14  5176.9  425.99  5206.9   430.1  5216.9  432.18  5226.9  435.27
  5256.9  441.94  5286.9  446.58  5316.9  449.52  5349.7   450.1
#Mann= 3 , 1 , 0
 4392.40    0.13       0  4876.7   0.042       0  5155.5    0.13       0
Bank Sta=4876.70,5155.50
Exp/Cntr=0.3,0.1

Type RM Length L Ch R = 1 ,253694.2,904.1,904.1,904.1
BEGIN DESCRIPTION:
Sandy Creek 254.0
END DESCRIPTION:
#Sta/Elev= 27
  4197.8     450  4287.8  444.06  4347.8  442.01  4397.8  441.89  4467.8  439.53
  4527.8   436.1  4557.8  433.61  4567.8  432.32  4617.8  429.31  4647.8   428.1
  4687.8   425.9  4727.8  425.12  4737.8  424.34  4757.8  424.98  4767.8  424.82
  4876.7  420.68  4999.9  414.68  5000.1  414.68  5155.5  420.68    5205  427.45
    5215  426.91    5235  429.12    5245  430.75    5445  444.39    5455  444.65
    5465  443.84  5616.8  450.52
#Mann= 3 , 1 , 0
 4197.80    0.13       0  4876.7   0.042       0  5155.5    0.13       0
Bank Sta=4876.70,5155.50
Exp/Cntr=0.5,0.3

Type RM Length L Ch R = 1 ,252790.1,25,25,25
BEGIN DESCRIPTION:
Upstream Section of Bridge/Culvert/Weir
END DESCRIPTION:
#Sta/Elev= 27
  4607.2   448.3  4677.2  441.18  4687.2  439.82  4707.2  438.36  4747.2  432.69
  4787.2  429.88  4817.2  426.29  4847.2  423.91  4857.2  421.04  4867.2  414.08
  4876.7  411.98  4999.9  405.98  5155.5  411.98  5165.3  415.78  5185.3  425.23
  5195.3  428.54  5205.3  429.31  5235.3  429.49  5255.3  431.26  5275.3  431.77
  5295.3  432.81  5305.3  432.19  5365.3  434.08  5375.3  435.05  5395.3  438.75
  5405.3  439.37    5428  439.26
#Mann= 3 , 1 , 0
 4607.20    0.13       0  4876.7   0.042       0  5155.5    0.13       0
#XS Ineff= 2 , 0
       0    4869     415    5161       0     422
Bank Sta=4876.70,5155.50
Exp/Cntr=0.5,0.3

Type RM Length L Ch R = 5 ,252777.6,,,
BEGIN DESCRIPTION:
Fox Reservoir Dam-TOR
Structure ID: Fox Reservoir - DAM
Approximate Survey Structure
END DESCRIPTION:
#Inline Weir SE= 21
  4607.2  448.18  4677.2  441.07  4687.2  439.71  4707.2  438.25  4747.2  432.58
  4787.2  429.77  4817.2  426.18  4847.2   423.8  4857.2  420.93  4867.2  419.07
  4999.9  419.05  5029.1  419.05  5185.3  427.29  5195.3  428.43  5205.3   429.2
  5235.3  429.93  5255.3  431.15  5275.3  432.03  5375.3  437.31  5405.3  439.25
    5428  439.14
IW Dist,WD,Coef,Skew,MaxSub,Min_El,Is_Ogee,SpillHt,DesHd
10.0,5.0,3.0,,0.95,, 0 ,,,2.0,2.0,

Type RM Length L Ch R = 1 ,252765.1,1039.6,1039.6,1039.6
BEGIN DESCRIPTION:
Downstream Section of Bridge/Culvert/Weir
END DESCRIPTION:
#Sta/Elev= 27
  4607.2  448.06  4677.2  440.94  4687.2  439.58  4707.2  438.12  4747.2  432.45
  4787.2  429.64  4817.2  426.05  4847.2  423.67  4857.2   420.8  4867.2  413.84
  4876.7  411.74  4999.9  405.74  5155.5  411.74  5165.3  415.54  5185.3  424.99
  5195.3   428.3  5205.3  429.07  5235.3  429.25  5255.3  431.02  5275.3  431.53
  5295.3  432.57  5305.3  431.95  5365.3  433.84  5375.3  434.81  5395.3  438.51
  5405.3  439.13    5428  439.02
#Mann= 3 , 1 , 0
 4607.20    0.13       0  4876.7   0.042       0  5155.5    0.13       0
#XS Ineff= 2 , 0
       0    4869     415    5161       0     422
Bank Sta=4876.70,5155.50
Exp/Cntr=0.5,0.3

Type RM Length L Ch R = 1 ,251725.5,23,23,23
BEGIN DESCRIPTION:
Upstream Section of Bridge/Culvert/Weir
END DESCRIPTION:
#Sta/Elev= 22
  4605.1  429.83  4607.7  430.49  4637.7  427.86  4657.7  425.57  4667.7   425.6
  4757.7  417.64  4787.7  416.09  4817.7  413.24  4857.7   410.9  4907.7  410.01
  4957.7  400.09  4999.9  397.09  5040.4  400.09  5058.9  410.12  5088.9  413.03
  5118.9  414.02  5168.9  417.99  5188.9     422  5208.9  421.94  5238.9  423.42
  5328.8  426.49  5333.5  427.18
#Mann= 3 , 1 , 0
 4605.10    0.13       0  4957.7   0.045       0  5040.4    0.13       0
#XS Ineff= 2 , 0
       0  4947.7     410  5050.4       0     410
Bank Sta=4957.70,5040.40
Exp/Cntr=0.5,0.3

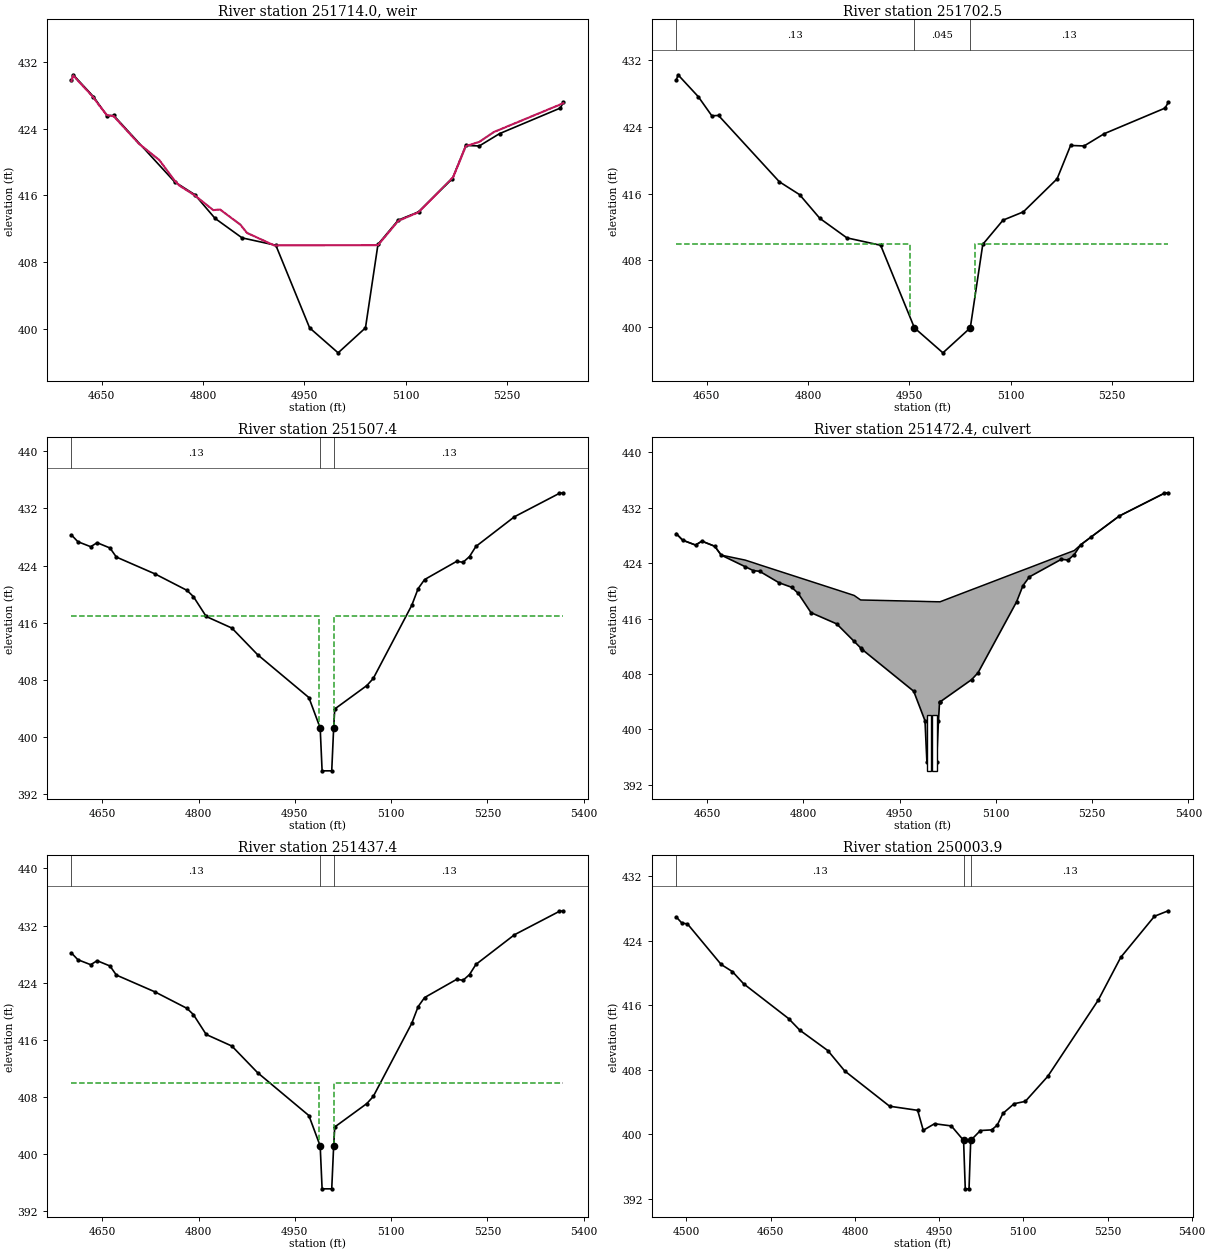
Type RM Length L Ch R = 5 ,251714.0,,,
BEGIN DESCRIPTION:
Dam_Vicksboro Rd_2
Structure ID: Dam_Vicksboro Rd
Approximate Survey Structure
END DESCRIPTION:
#Inline Weir SE= 24
  4605.1  429.73  4607.7   430.4  4637.7  427.77  4645.1  426.92  4657.7  425.64
  4667.7  425.51  4705.1   422.2  4735.1  420.25  4757.7  417.79  4765.1  417.17
  4787.7     416  4815.1  414.23  4825.1  414.31  4855.1  412.49  4865.1  411.49
  4905.1     410  5058.9  410.03  5088.9  412.94  5118.9  413.98  5170.4  418.21
  5188.9  421.91  5208.9  422.43  5230.4  423.61  5333.5  427.08
IW Dist,WD,Coef,Skew,MaxSub,Min_El,Is_Ogee,SpillHt,DesHd
10.0,3.0,3.0,,0.95,, 0 ,,,2.0,2.0,

Type RM Length L Ch R = 1 ,251702.5,195.1,195.1,195.1
BEGIN DESCRIPTION:
Downstream Section of Bridge/Culvert/Weir
END DESCRIPTION:
#Sta/Elev= 22
  4605.1  429.62  4607.7  430.28  4637.7  427.65  4657.7  425.36  4667.7  425.39
  4757.7  417.43  4787.7  415.88  4817.7  413.03  4857.7  410.69  4907.7   409.8
  4957.7  399.88  4999.9  396.88  5040.4  399.88  5058.9  409.91  5088.9  412.82
  5118.9  413.81  5168.9  417.78  5188.9  421.79  5208.9  421.73  5238.9  423.21
  5328.8  426.28  5333.5  426.97
#Mann= 3 , 1 , 0
 4605.10    0.13       0  4957.7   0.045       0  5040.4    0.13       0
#XS Ineff= 2 , 0
       0 4951.03     410 5047.07       0     410
Bank Sta=4957.70,5040.40
Exp/Cntr=0.5,0.3

Type RM Length L Ch R = 1 ,251507.4,70,70,70
BEGIN DESCRIPTION:
Upstream Section of Bridge/Culvert/Weir
END DESCRIPTION:
#Sta/Elev= 30
  4601.9  428.28  4611.9  427.34  4631.9  426.64  4641.9   427.2  4661.9  426.46
  4671.9  425.19  4731.9  422.84  4781.9  420.53  4791.9  419.66  4811.9  416.87
  4851.9  415.25  4891.9  411.53  4971.9  405.52  4989.5  401.26  4992.5  395.26
  5007.5  395.26  5010.5  401.26  5012.2  403.92  5062.2   407.2  5072.2  408.19
  5132.2  418.43  5142.2  420.78  5152.2  422.04  5202.2  424.59  5212.2  424.46
  5222.2  425.26  5232.2  426.68  5292.2  430.83  5362.2  434.11  5368.6  434.19
#Mann= 3 , 1 , 0
 4601.90    0.13       0  4989.5   0.045       0  5010.5    0.13       0
#XS Ineff= 2 , 0
       0  4987.7     417  5010.5       0     417
Bank Sta=4989.50,5010.50
Exp/Cntr=0.5,0.3

Type RM Length L Ch R = 2 ,251472.4,,,
BEGIN DESCRIPTION:
Vicksboro Rd-1-TOR
Structure ID: Vicksboro Rd-Culvert
Approximate Survey Structure
END DESCRIPTION:
Bridge Culvert--1,0,-1,-1, 0
Deck Dist Width WeirC Skew NumUp NumDn MinLoCord MaxHiCord MaxSubmerge Is_Ogee
10,50,3,,37,37,,,0.95,0,1,1,,
  4601.9  4611.9  4631.9  4641.9  4661.9  4671.9  4709.1  4721.9  4731.9  4761.9
  4781.9  4791.9  4811.9  4851.9  4879.1  4889.1  4891.9  4971.9  4989.5  4992.5
  5007.5  5010.5  5012.2  5012.9  5062.2  5072.2  5132.2  5142.2  5152.2  5202.2
  5212.2  5222.2  5232.2  5248.9  5292.2  5362.2  5368.6
  428.26  427.32  426.62  427.18  426.44  425.17  424.45  424.07  423.76  422.86
  422.26  421.96  421.36  420.16  419.34  418.69  418.68  418.51  418.47  418.46
  418.43  418.43  418.42  418.42  420.17  420.52  422.65     423  423.35  425.13
  425.48  425.83  426.66  427.82  430.81  434.09  434.17
  428.26  427.32  426.62  427.18  426.44  425.17   423.5  422.93  422.82  421.18
  420.51  419.64  416.85  415.23   412.7  411.77  411.51   405.5  401.24  395.24
  395.24  401.24   403.9  403.95  407.18  408.17  418.41  420.76  422.02  424.57
  424.44  425.24  426.66  427.82  430.81  434.09  434.17
  4601.9  4611.9  4631.9  4641.9  4661.9  4671.9  4709.1  4721.9  4731.9  4761.9
  4781.9  4791.9  4811.9  4851.9  4879.1  4889.1  4891.9  4971.9  4989.5  4992.5
  5007.5  5010.5  5012.2  5012.9  5062.2  5072.2  5132.2  5142.2  5152.2  5202.2
  5212.2  5222.2  5232.2  5248.9  5292.2  5362.2  5368.6
  428.22  427.28  426.58  427.14   426.4  425.13  424.45  424.07  423.76  422.86
  422.26  421.96  421.36  420.16  419.34  418.69  418.68  418.51  418.47  418.46
  418.43  418.43  418.42  418.42  420.17  420.52  422.65     423  423.35  425.13
  425.48  425.83  426.63  427.79  430.77  434.05  434.13
  428.18  427.24  426.54   427.1  426.36  425.09  423.42  422.85  422.74   421.1
  420.43  419.56  416.77  415.15  412.62  411.69  411.43  405.42  401.16  395.16
  395.16  401.16  403.82  403.87   407.1  408.09  418.33  420.68  421.94  424.49
  424.36  425.16  426.58  427.74  430.73  434.01  434.09
BR Coef= 1 , 0 , 0 ,1.25, 0 ,,,0.8,-1,2,0,
Wspro=,,,, 1 ,,,, 0 ,,,, 0 ,,,,-1 ,-1 ,-1 , 0 , 0 , 0 , 0 , 0
Culvert=2,8.0,7.0,50.0,0.015,0.4,1.0,8,1,394.00,4996.04,393.75,4996.04,Culvert #1  ,0,10
Culvert=2,8.0,7.0,50.0,0.015,0.4,1.0,8,1,394.00,5004.04,393.75,5004.04,Culvert #2  ,0,10
BC Design=,, 0 ,, 0 ,,,,,,
BR U #Sta/Elev= 37
  4601.9  428.26  4611.9  427.32  4631.9  426.62  4641.9  427.18  4661.9  426.44
  4671.9  425.17  4709.1   423.5  4721.9  422.93  4731.9  422.82  4761.9  421.18
  4781.9  420.51  4791.9  419.64  4811.9  416.85  4851.9  415.23  4879.1   412.7
  4889.1  411.77  4891.9  411.51  4971.9   405.5  4989.5  401.24  4992.5  395.24
  5007.5  395.24  5010.5  401.24  5012.2   403.9  5012.9  403.95  5062.2  407.18
  5072.2  408.17  5132.2  418.41  5142.2  420.76  5152.2  422.02  5202.2  424.57
  5212.2  424.44  5222.2  425.24  5232.2  426.66  5248.9  427.82  5292.2  430.81
  5362.2  434.09  5368.6  434.17
BR U #Mann= 3
 4601.90    0.13  4989.5   0.045  5010.5    0.13
BR U Banks=4989.50,5010.50
BR D #Sta/Elev= 37
  4601.9  428.18  4611.9  427.24  4631.9  426.54  4641.9   427.1  4661.9  426.36
  4671.9  425.09  4709.1  423.42  4721.9  422.85  4731.9  422.74  4761.9   421.1
  4781.9  420.43  4791.9  419.56  4811.9  416.77  4851.9  415.15  4879.1  412.62
  4889.1  411.69  4891.9  411.43  4971.9  405.42  4989.5  401.16  4992.5  395.16
  5007.5  395.16  5010.5  401.16  5012.2  403.82  5012.9  403.87  5062.2   407.1
  5072.2  408.09  5132.2  418.33  5142.2  420.68  5152.2  421.94  5202.2  424.49
  5212.2  424.36  5222.2  425.16  5232.2  426.58  5248.9  427.74  5292.2  430.73
  5362.2  434.01  5368.6  434.09
BR D #Mann= 3
 4601.90    0.13  4989.5   0.045  5010.5    0.13
BR D Banks=4989.50,5010.50

Type RM Length L Ch R = 1 ,251437.4,1433.5,1433.5,1433.5
BEGIN DESCRIPTION:
Downstream Section of Bridge/Culvert/Weir
END DESCRIPTION:
#Sta/Elev= 30
  4601.9  428.16  4611.9  427.22  4631.9  426.52  4641.9  427.08  4661.9  426.34
  4671.9  425.07  4731.9  422.72  4781.9  420.41  4791.9  419.54  4811.9  416.75
  4851.9  415.13  4891.9  411.41  4971.9   405.4  4989.5  401.14  4992.5  395.14
  5007.5  395.14  5010.5  401.14  5012.2   403.8  5062.2  407.08  5072.2  408.07
  5132.2  418.31  5142.2  420.66  5152.2  421.92  5202.2  424.47  5212.2  424.34
  5222.2  425.14  5232.2  426.56  5292.2  430.71  5362.2  433.99  5368.6  434.07
#Mann= 3 , 1 , 0
 4601.90    0.13       0  4989.5   0.045       0  5010.5    0.13       0
#XS Ineff= 2 , 0
       0  4987.7     410  5010.5       0     410
Bank Sta=4989.50,5010.50
Exp/Cntr=0.5,0.3

Type RM Length L Ch R = 1 ,250003.9,1463.2,1463.2,1463.2
BEGIN DESCRIPTION:
Sandy Creek 250.0
END DESCRIPTION:
#Sta/Elev= 30
  4481.8  426.93  4491.8  426.18  4501.8  426.07  4561.8  421.05  4581.8  420.17
  4601.8  418.66  4681.8  414.36  4701.8  412.92  4751.8  410.39  4781.8  407.87
  4861.8   403.5  4911.8  402.99  4921.8  400.52  4941.8  401.33  4971.8  401.06
  4993.6  399.27  4996.6  393.27  5003.3  393.27  5006.3  399.27  5023.6  400.49
  5043.6  400.57  5053.6  401.16  5063.6   402.6  5083.6  403.81  5103.6   404.1
  5143.6   407.2  5233.6  416.65  5273.6  421.94  5333.6  427.02  5358.2   427.7
#Mann= 3 , 1 , 0
 4481.80    0.13       0  4993.6   0.042       0  5006.3    0.13       0
Bank Sta=4993.60,5006.30
Exp/Cntr=0.3,0.1