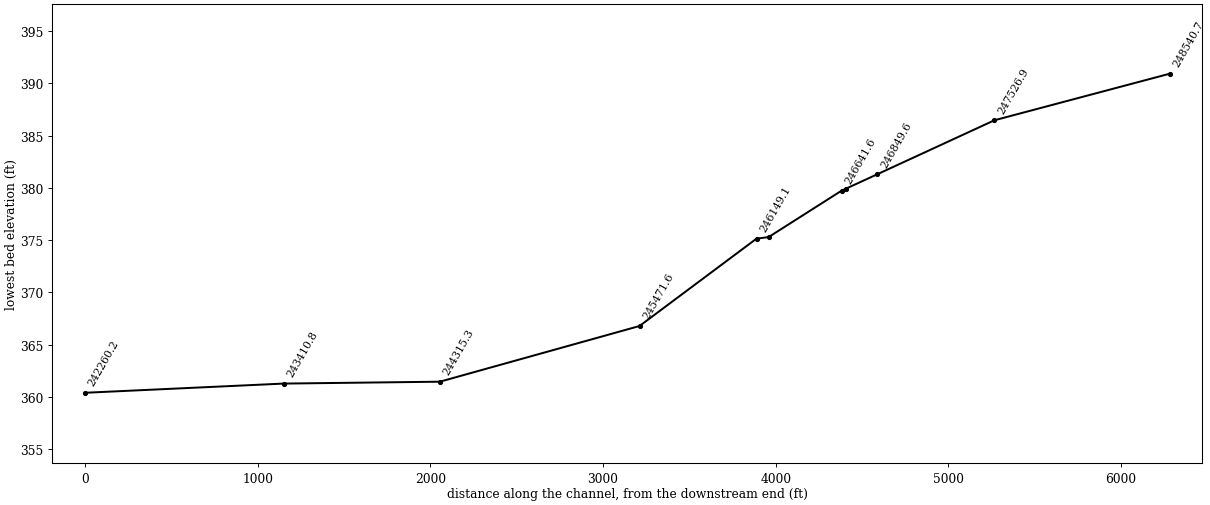
HEC-RAS study 020822_SANDY_CREEK.prj: Sandy Creek

--- 020822_SANDY_CREEK.g01 (geometry) --- (continued)

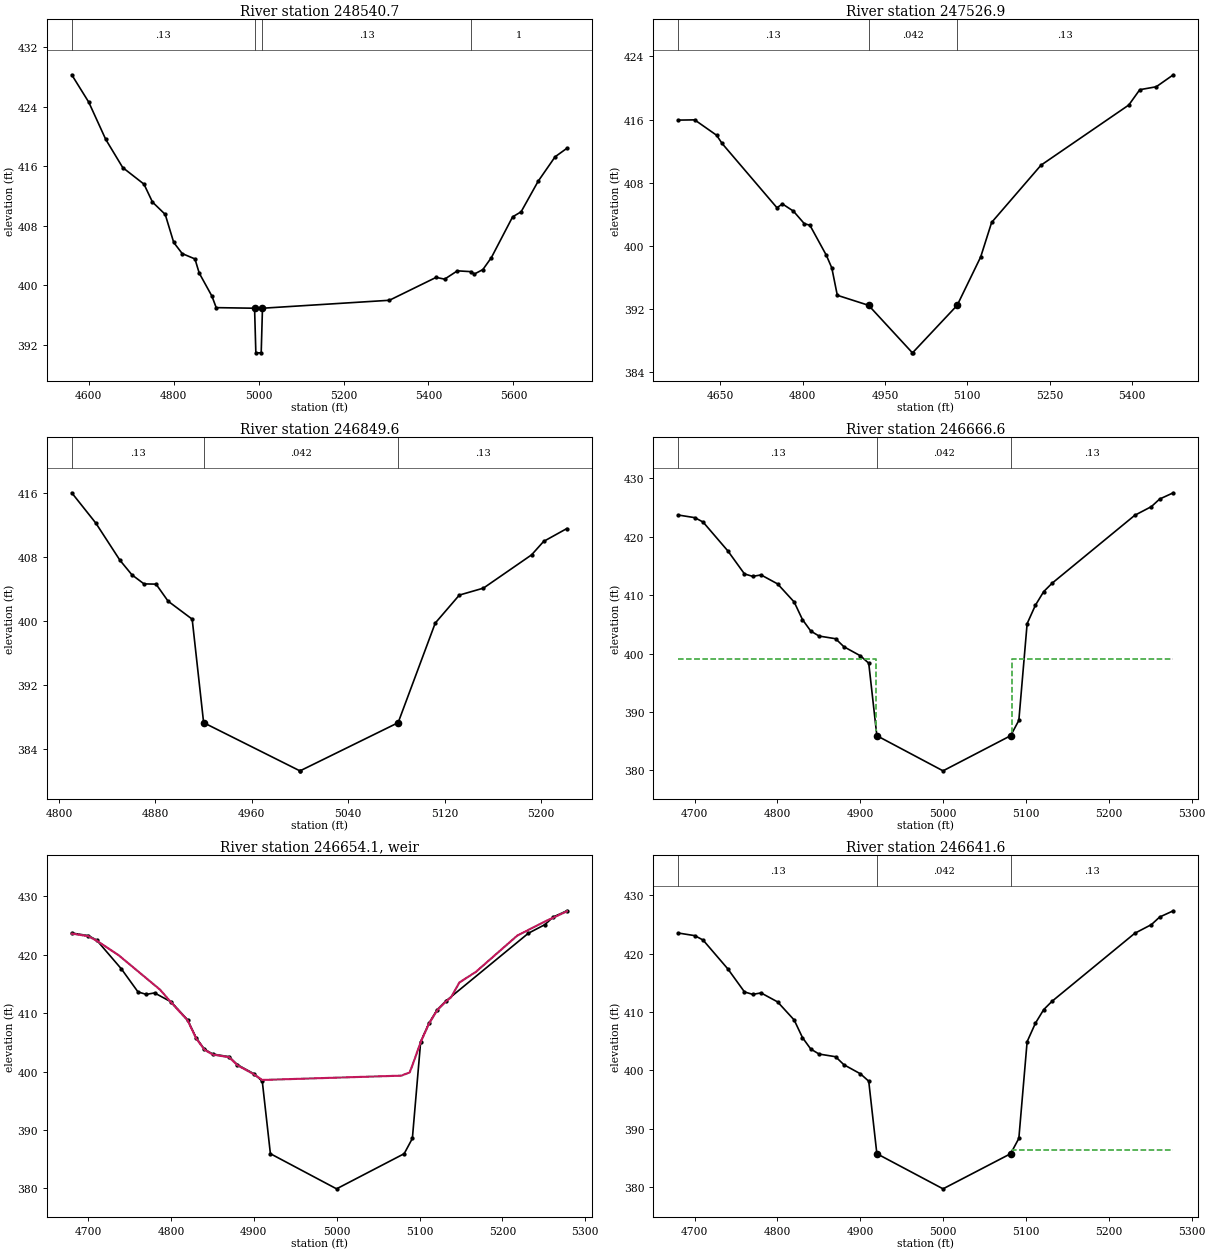
Type RM Length L Ch R = 1 ,248540.7,1013.8,1013.8,1013.8
BEGIN DESCRIPTION:
Sandy Creek 249.0
END DESCRIPTION:
#Sta/Elev= 30
  4560.4  428.31  4600.4  424.63  4640.4  419.62  4680.4  415.83  4730.4   413.6
  4750.4  411.19  4780.4  409.53  4800.4  405.76  4820.4  404.26  4850.4  403.54
  4860.4  401.64  4890.4  398.53  4900.4  396.99  4990.7  396.91  4993.7  390.91
  5006.3  390.91  5009.3  396.91    5308  397.98    5418  401.06    5438  400.82
    5468  401.94  5499.9  401.83    5508  401.51    5528  402.11    5548  403.72
    5598   409.2    5618  409.88    5658  413.98    5698  417.28  5725.7  418.42
#Mann= 4 , 1 , 0
 4560.40    0.13       0  4990.7   0.042       0  5009.3    0.13       0
  5499.9       1       0
Bank Sta=4990.70,5009.30
Exp/Cntr=0.3,0.1

Type RM Length L Ch R = 1 ,247526.9,677.3,677.3,677.3
BEGIN DESCRIPTION:
Sandy Creek 248.0
END DESCRIPTION:
#Sta/Elev= 23
    4573  415.94    4603  415.97    4643  414.02    4653  412.98    4753  404.84
    4763  405.32    4783  404.41    4803  402.81    4813  402.63    4843  398.82
    4853  397.21    4863  393.75    4920  392.48  4999.9  386.46  5000.1  386.46
  5081.5  392.48  5124.3   398.6  5144.3  402.98  5234.3  410.23  5394.3  417.85
  5414.3  419.79  5444.3  420.16  5475.5  421.68
#Mann= 3 , 1 , 0
 4573.00    0.13       0    4920   0.042       0  5081.5    0.13       0
Bank Sta=4920.00,5081.50
Exp/Cntr=0.3,0.1

Type RM Length L Ch R = 1 ,246849.6,183,183,183
BEGIN DESCRIPTION:
Sandy Creek 247.0
END DESCRIPTION:
#Sta/Elev= 18
  4810.5  416.06  4830.5  412.27  4850.5  407.63  4860.5   405.8  4870.5  404.67
  4880.5  404.64  4890.5  402.51  4910.5  400.26    4920  387.32  4999.9   381.3
  5000.1   381.3  5081.5  387.32  5112.3  399.77  5132.3  403.27  5152.3  404.14
  5192.3   408.3  5202.3  409.98  5221.6  411.59
#Mann= 3 , 1 , 0
 4810.50    0.13       0    4920   0.042       0  5081.5    0.13       0
Bank Sta=4920.00,5081.50
Exp/Cntr=0.5,0.3

Type RM Length L Ch R = 1 ,246666.6,25,25,25
BEGIN DESCRIPTION:
Upstream Section of Bridge/Culvert/Weir
END DESCRIPTION:
#Sta/Elev= 28
  4680.2  423.73  4700.2  423.28  4710.2  422.53  4740.2  417.57  4760.2  413.64
  4770.2  413.22  4780.2  413.47  4800.2  411.93  4820.2  408.83  4830.2  405.82
  4840.2  403.86  4850.2     403  4870.2  402.54  4880.2  401.17  4900.2  399.61
  4910.2  398.35    4920  385.93  4999.9  379.91  5081.5  385.93  5091.4  388.55
  5101.4  405.12  5111.4  408.28  5121.4  410.61  5131.4  412.03  5231.4  423.69
  5251.4  425.17  5261.4  426.47  5277.9  427.54
#Mann= 3 , 1 , 0
 4680.20    0.13       0    4920   0.042       0  5081.5    0.13       0
#XS Ineff= 2 , 0
       0 4919.41     399    5083       0     399
Bank Sta=4920.00,5081.50
Exp/Cntr=0.5,0.3

Type RM Length L Ch R = 5 ,246654.1,,,
BEGIN DESCRIPTION:
Roland Pond Dam-TOR
Structure ID: Roland Pond_DAM
Approximate Survey Structure
END DESCRIPTION:
#Inline Weir SE= 27
  4680.2  423.63  4700.2  423.18  4710.2  422.43  4736.8  419.93  4786.8  414.03
  4800.2  411.84  4820.2  408.74  4830.2  405.73  4840.2  403.77  4850.2  402.91
  4870.2  402.45  4880.2  401.08  4900.2  399.52  4910.2  398.56  5078.1   399.3
  5088.1  399.85  5091.4  401.05  5101.4  405.03  5111.4  408.19  5121.4  410.52
  5131.4  411.94  5138.1  412.72  5148.1  415.25  5168.1  417.08  5218.1   423.3
  5252.6  425.78  5277.9  427.44
IW Dist,WD,Coef,Skew,MaxSub,Min_El,Is_Ogee,SpillHt,DesHd
10.0,5.0,3.0,,0.95,, 0 ,,,2.0,2.0,

Type RM Length L Ch R = 1 ,246641.6,422.5,422.5,422.5
BEGIN DESCRIPTION:
Downstream Section of Bridge/Culvert/Weir
END DESCRIPTION:
#Sta/Elev= 28
  4680.2  423.54  4700.2  423.09  4710.2  422.34  4740.2  417.38  4760.2  413.45
  4770.2  413.03  4780.2  413.28  4800.2  411.74  4820.2  408.64  4830.2  405.63
  4840.2  403.67  4850.2  402.81  4870.2  402.35  4880.2  400.98  4900.2  399.42
  4910.2  398.16    4920  385.74  4999.9  379.72  5081.5  385.74  5091.4  388.36
  5101.4  404.93  5111.4  408.09  5121.4  410.42  5131.4  411.84  5231.4   423.5
  5251.4  424.98  5261.4  426.28  5277.9  427.35
#Mann= 3 , 1 , 0
 4680.20    0.13       0    4920   0.042       0  5081.5    0.13       0
#XS Ineff= 2 , 0
       0 4919.41   386.3    5083       0   386.3
Bank Sta=4920.00,5081.50
Exp/Cntr=0.5,0.3

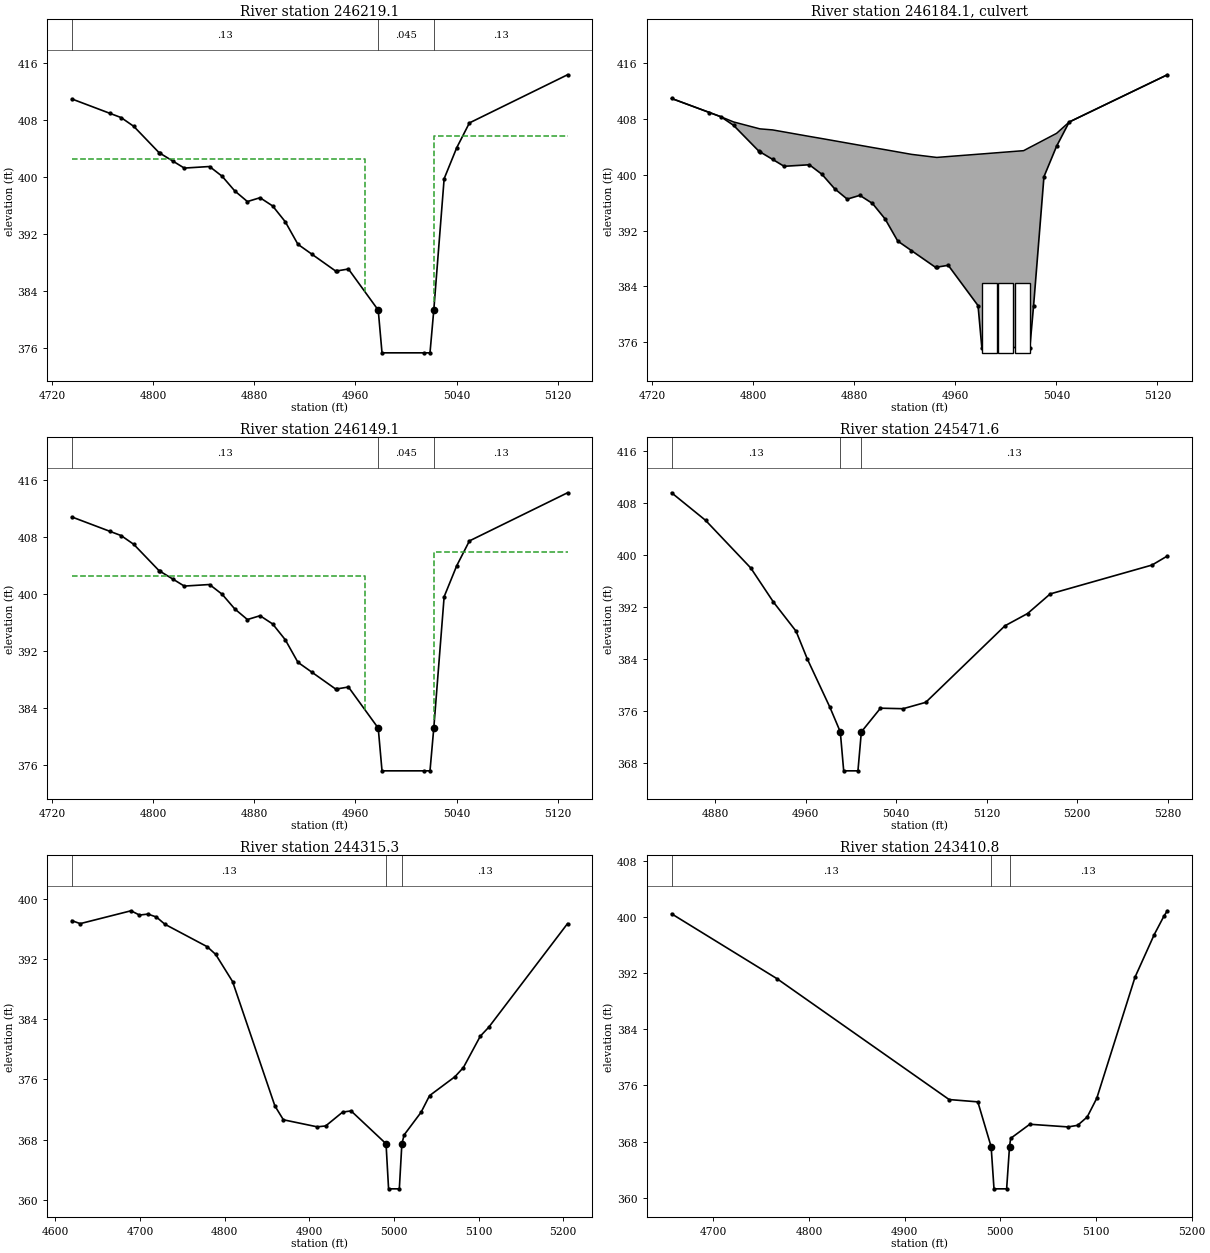
Type RM Length L Ch R = 1 ,246219.1,70,70,70
BEGIN DESCRIPTION:
Upstream Section of Bridge/Culvert/Weir
END DESCRIPTION:
#Sta/Elev= 29
  4735.3  410.93  4765.3  408.92  4774.4  408.31  4784.4  407.08  4804.4  403.39
  4805.3  403.29  4815.3  402.21  4824.4  401.22  4844.4  401.44  4854.4  400.07
  4864.4  398.01  4874.4  396.52  4884.4  397.06  4894.4   395.9  4904.4  393.68
  4914.4  390.52  4925.3  389.15  4944.4  386.75  4945.3  386.78  4954.4  387.05
    4978  381.28    4981  375.28  5014.1  375.28    5019  375.28    5022  381.28
  5030.2  399.73  5040.2  404.09  5050.2  407.56  5127.9  414.32
#Mann= 3 , 1 , 0
 4735.30    0.13       0    4978   0.045       0    5022    0.13       0
#XS Ineff= 2 , 0
       0 4967.42  402.51  5022.5       0  405.79
Bank Sta=4978.00,5022.00
Exp/Cntr=0.5,0.3

Type RM Length L Ch R = 2 ,246184.1,,,
BEGIN DESCRIPTION:
Rockmill Rd-TOR
Structure ID: Rockmill Rd-
Approximate Survey Structure
END DESCRIPTION:
Bridge Culvert--1,0,-1,-1, 0
Deck Dist Width WeirC Skew NumUp NumDn MinLoCord MaxHiCord MaxSubmerge Is_Ogee
10,50,3,,29,29,,,0.95,0,1,1,,
  4735.3  4765.3  4774.4  4784.4  4804.4  4805.3  4815.3  4824.4  4844.4  4854.4
  4864.4  4874.4  4884.4  4894.4  4904.4  4914.4  4925.3  4944.4  4945.3  4954.4
    4978    4981  5014.1    5019    5022  5030.2  5040.2  5050.2  5127.9
  410.91   408.9  408.29  407.55   406.6  406.56  406.41  406.12  405.48  405.17
  404.85  404.53  404.21  403.89  403.58  403.26  402.91  402.49  402.47   402.6
  402.93  402.97  403.44  403.91  404.19  404.97  405.92  407.54   414.3
  410.91   408.9  408.29  407.06  403.37  403.27  402.19   401.2  401.42  400.05
  397.99   396.5  397.04  395.88  393.66   390.5  389.13  386.73  386.76  387.03
  381.26  375.26  375.26  375.26  381.26  399.71  404.07  407.54   414.3
  4735.3  4765.3  4774.4  4784.4  4804.4  4805.3  4815.3  4824.4  4844.4  4854.4
  4864.4  4874.4  4884.4  4894.4  4904.4  4914.4  4925.3  4944.4  4945.3  4954.4
    4978    4981  5014.1    5019    5022  5030.2  5040.2  5050.2  5127.9
  410.85  408.85  408.24  407.55   406.6  406.56  406.41  406.12  405.48  405.17
  404.85  404.53  404.21  403.89  403.58  403.26  402.91  402.49  402.47   402.6
  402.93  402.97  403.44  403.91  404.19  404.97  405.92  407.49  414.24
   410.8  408.79  408.18  406.95  403.26  403.16  402.08  401.09  401.31  399.94
  397.88  396.39  396.93  395.77  393.55  390.39  389.02  386.62  386.65  386.92
  381.15  375.15  375.15  375.15  381.15   399.6  403.96  407.43  414.19
BR Coef= 1 , 0 , 0 ,1.25, 0 ,,,0.8,-1,2,0,
Wspro=,,,, 1 ,,,, 0 ,,,, 0 ,,,,-1 ,-1 ,-1 , 0 , 0 , 0 , 0 , 0
Culvert=2,10.0,12.0,50.0,0.015,0.4,1.0,8,1,374.50,4987.03,374.25,4987.03,Culvert #1  ,0,10
Culvert=2,10.0,12.0,50.0,0.015,0.4,1.0,8,1,374.50,5000.03,374.25,5000.03,Culvert #2  ,0,10
Culvert=2,10.0,12.0,50.0,0.015,0.4,1.0,8,1,374.50,5013.03,374.25,5013.03,Culvert #3  ,0,10
BC Design=,, 0 ,, 0 ,,,,,,
BR U #Sta/Elev= 29
  4735.3  410.91  4765.3   408.9  4774.4  408.29  4784.4  407.06  4804.4  403.37
  4805.3  403.27  4815.3  402.19  4824.4   401.2  4844.4  401.42  4854.4  400.05
  4864.4  397.99  4874.4   396.5  4884.4  397.04  4894.4  395.88  4904.4  393.66
  4914.4   390.5  4925.3  389.13  4944.4  386.73  4945.3  386.76  4954.4  387.03
    4978  381.26    4981  375.26  5014.1  375.26    5019  375.26    5022  381.26
  5030.2  399.71  5040.2  404.07  5050.2  407.54  5127.9   414.3
BR U #Mann= 3
 4735.30    0.13    4978   0.045    5022    0.13
BR U Banks=4978.00,5022.00
BR D #Sta/Elev= 29
  4735.3   410.8  4765.3  408.79  4774.4  408.18  4784.4  406.95  4804.4  403.26
  4805.3  403.16  4815.3  402.08  4824.4  401.09  4844.4  401.31  4854.4  399.94
  4864.4  397.88  4874.4  396.39  4884.4  396.93  4894.4  395.77  4904.4  393.55
  4914.4  390.39  4925.3  389.02  4944.4  386.62  4945.3  386.65  4954.4  386.92
    4978  381.15    4981  375.15  5014.1  375.15    5019  375.15    5022  381.15
  5030.2   399.6  5040.2  403.96  5050.2  407.43  5127.9  414.19
BR D #Mann= 3
 4735.30    0.13    4978   0.045    5022    0.13
BR D Banks=4978.00,5022.00

Type RM Length L Ch R = 1 ,246149.1,677.5,677.5,677.5
BEGIN DESCRIPTION:
Downstream Section of Bridge/Culvert/Weir
END DESCRIPTION:
#Sta/Elev= 29
  4735.3  410.78  4765.3  408.77  4774.4  408.16  4784.4  406.93  4804.4  403.24
  4805.3  403.14  4815.3  402.06  4824.4  401.07  4844.4  401.29  4854.4  399.92
  4864.4  397.86  4874.4  396.37  4884.4  396.91  4894.4  395.75  4904.4  393.53
  4914.4  390.37  4925.3     389  4944.4   386.6  4945.3  386.63  4954.4   386.9
    4978  381.13    4981  375.13  5014.1  375.13    5019  375.13    5022  381.13
  5030.2  399.58  5040.2  403.94  5050.2  407.41  5127.9  414.17
#Mann= 3 , 1 , 0
 4735.30    0.13       0    4978   0.045       0    5022    0.13       0
#XS Ineff= 2 , 0
       0 4967.42  402.51  5022.5       0  405.79
Bank Sta=4978.00,5022.00
Exp/Cntr=0.5,0.3

Type RM Length L Ch R = 1 ,245471.6,1156.3,1156.3,1156.3
BEGIN DESCRIPTION:
Sandy Creek 245.0
END DESCRIPTION:
#Sta/Elev= 19
  4841.6   409.6  4871.6  405.36  4911.6  398.01  4931.6  392.77  4951.6  388.28
  4961.6  383.98  4981.6  376.53  4990.7  372.77  4993.7  366.77  5006.3  366.77
  5009.3  372.77  5026.2  376.42  5046.2  376.34  5066.2  377.32  5136.2  389.11
  5156.2     391  5176.2  394.02  5266.2  398.47  5279.7  399.86
#Mann= 3 , 1 , 0
 4841.60    0.13       0  4990.7   0.042       0  5009.3    0.13       0
Bank Sta=4990.70,5009.30
Exp/Cntr=0.3,0.1

Type RM Length L Ch R = 1 ,244315.3,904.5,904.5,904.5
BEGIN DESCRIPTION:
Sandy Creek 244.0
END DESCRIPTION:
#Sta/Elev= 28
  4619.3  397.13  4629.3  396.73  4689.3  398.44  4699.3  397.87  4709.3     398
  4719.3  397.61  4729.3  396.65  4779.3  393.66  4789.3  392.64  4809.3  389.02
  4859.3  372.47  4869.3  370.63  4909.3  369.69  4919.3  369.81  4939.3  371.65
  4949.3  371.81  4990.6  367.44  4993.6  361.44  5006.3  361.44  5009.3  367.44
    5012  368.62    5032  371.63    5042  373.84    5072  376.36    5082  377.58
    5102  381.76    5112  382.95    5205  396.73
#Mann= 3 , 1 , 0
 4619.30    0.13       0  4990.6   0.042       0  5009.3    0.13       0
Bank Sta=4990.60,5009.30
Exp/Cntr=0.3,0.1

Type RM Length L Ch R = 1 ,243410.8,1150.6,1150.6,1150.6
BEGIN DESCRIPTION:
Sandy Creek 243.0
END DESCRIPTION:
#Sta/Elev= 18
  4656.5  400.44  4766.5  391.21  4946.5  373.98  4976.5  373.65  4990.4  367.26
  4993.4  361.26  5006.6  361.26  5009.6  367.26  5010.8  368.45  5030.8  370.46
  5070.8  370.08  5080.8  370.31  5090.8   371.5  5100.8  374.17  5140.8  391.43
  5160.8  397.47  5170.8  400.07  5174.5  400.87
#Mann= 3 , 1 , 0
 4656.50    0.13       0  4990.4   0.042       0  5009.6    0.13       0
Bank Sta=4990.40,5009.60
Exp/Cntr=0.3,0.1

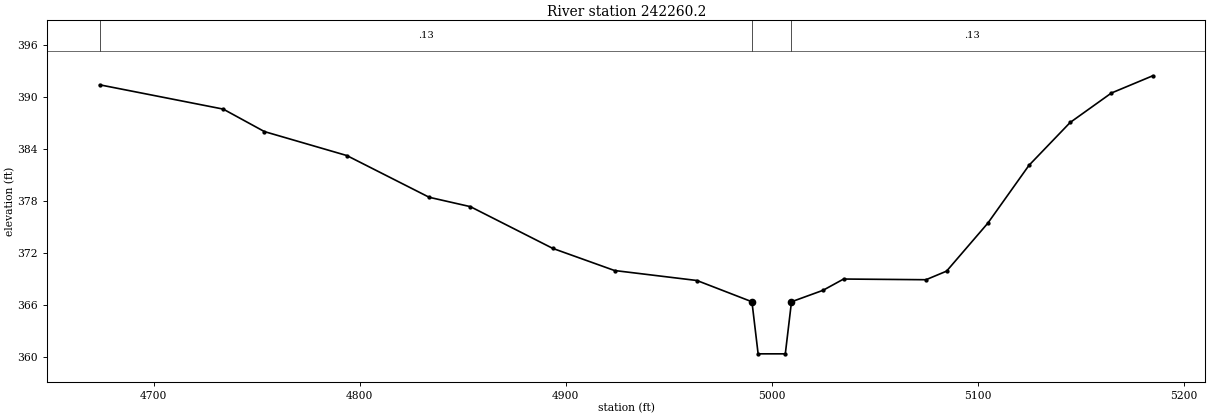
Type RM Length L Ch R = 1 ,242260.2,1082.8,1082.8,1082.8
BEGIN DESCRIPTION:
Sandy Creek 242.0
END DESCRIPTION:
#Sta/Elev= 22
  4673.7  391.38  4733.7  388.58  4753.7  385.99  4793.7  383.23  4833.7  378.42
  4853.7  377.34  4893.7  372.53  4923.7  369.98  4963.7  368.83  4990.4  366.38
  4993.4  360.38  5006.6  360.38  5009.6  366.38  5024.9   367.7  5034.9     369
  5074.9  368.92  5084.9  369.91  5104.9  375.43  5124.9   382.1  5144.9  387.04
  5164.9  390.43    5185  392.42
#Mann= 3 , 1 , 0
 4673.70    0.13       0  4990.4   0.042       0  5009.6    0.13       0
Bank Sta=4990.40,5009.60
Exp/Cntr=0.3,0.1