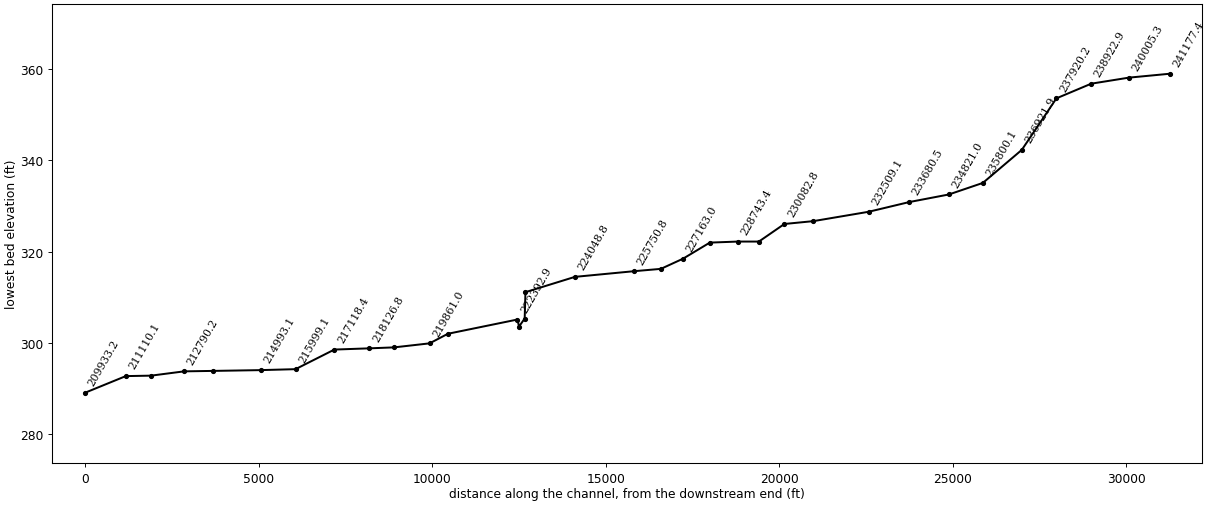
HEC-RAS study 020822_SANDY_CREEK.prj: Sandy Creek

--- 020822_SANDY_CREEK.g01 (geometry) --- (continued)

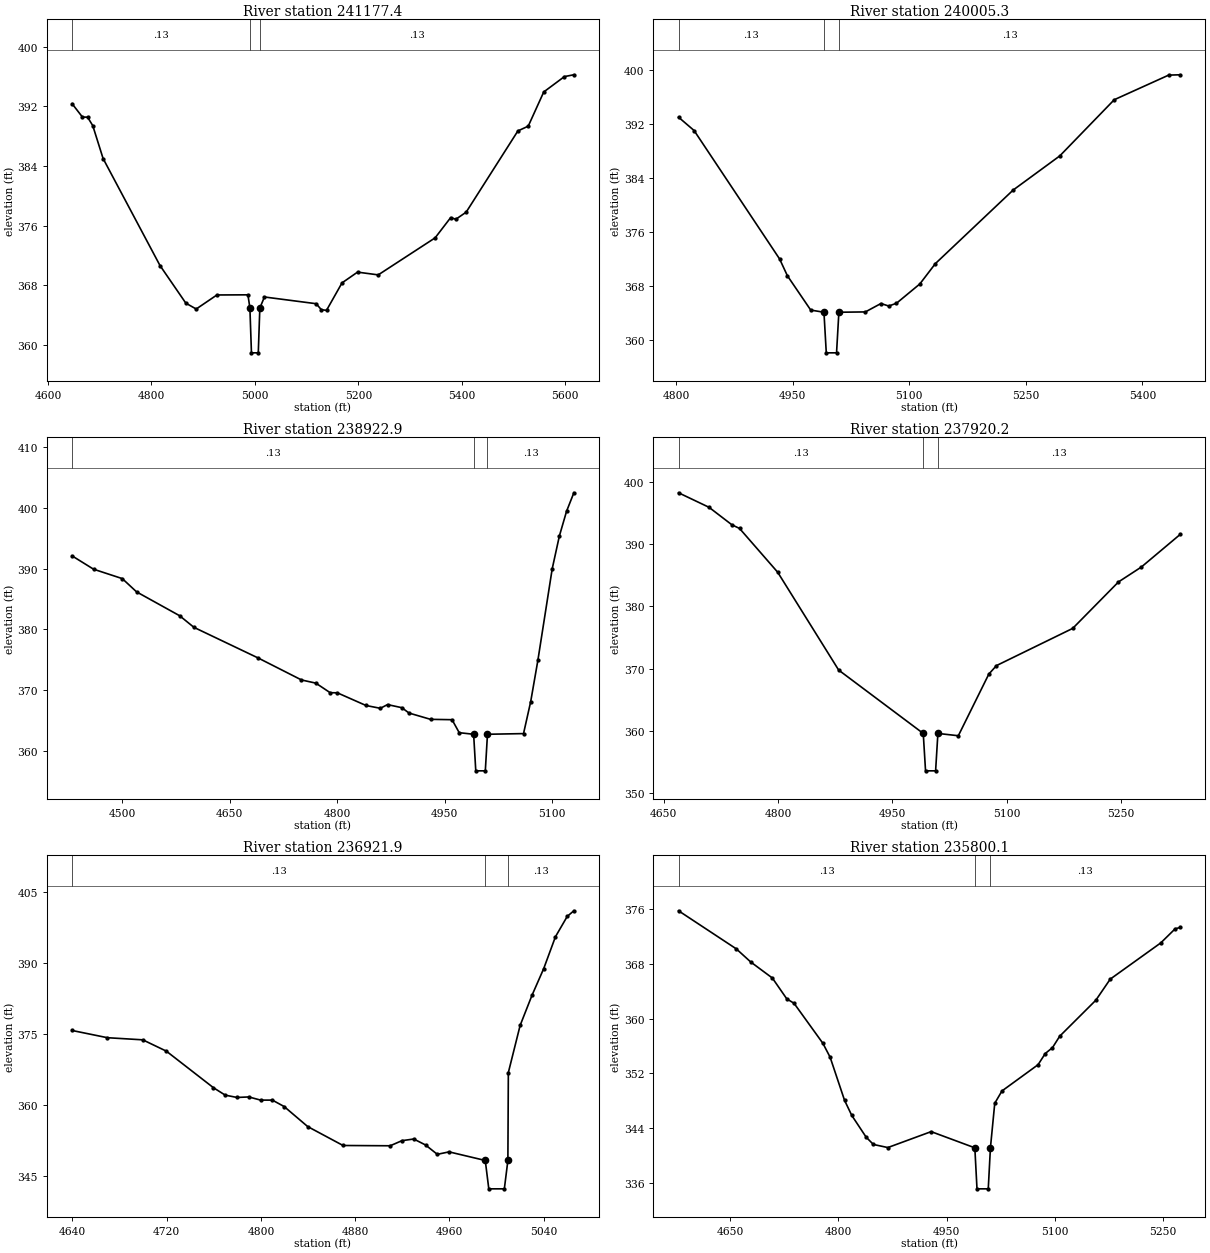
Type RM Length L Ch R = 1 ,241177.4,1172.1,1172.1,1172.1
BEGIN DESCRIPTION:
Sandy Creek 241.0
END DESCRIPTION:
#Sta/Elev= 30
  4646.6  392.35  4666.6  390.56  4676.6  390.54  4686.6  389.41  4706.6     385
  4816.6  370.67  4866.6  365.63  4886.6  364.85  4926.6  366.73  4986.6  366.75
  4990.4  364.98  4993.4  358.98  5006.6  358.98  5009.6  364.98  5018.5  366.46
  5118.5  365.56  5128.5  364.76  5138.5  364.67  5168.5  368.35  5198.5  369.79
  5238.5  369.42  5348.5  374.38  5378.5  377.09  5388.5  376.87  5408.5  377.82
  5508.5   388.7  5528.5  389.34  5558.5  393.92  5598.5  395.98  5616.7  396.22
#Mann= 3 , 1 , 0
 4646.60    0.13       0  4990.4   0.042       0  5009.6    0.13       0
Bank Sta=4990.40,5009.60
Exp/Cntr=0.3,0.1

Type RM Length L Ch R = 1 ,240005.3,1082.4,1082.4,1082.4
BEGIN DESCRIPTION:
Sandy Creek 240.0
END DESCRIPTION:
#Sta/Elev= 20
  4803.4  392.96  4823.4  390.99  4933.4     372  4943.4  369.52  4973.4  364.45
  4990.4  364.13  4993.4  358.13  5006.6  358.13  5009.6  364.13  5043.7  364.18
  5063.7  365.42  5073.7  365.05  5083.7  365.46  5113.7  368.31  5133.7  371.32
  5233.7  382.19  5293.7  387.24  5363.7  395.54  5433.7  399.18  5448.7  399.23
#Mann= 3 , 1 , 0
 4803.40    0.13       0  4990.4   0.042       0  5009.6    0.13       0
Bank Sta=4990.40,5009.60
Exp/Cntr=0.3,0.1

Type RM Length L Ch R = 1 ,238922.9,1002.7,1002.7,1002.7
BEGIN DESCRIPTION:
Sandy Creek 239.0
END DESCRIPTION:
#Sta/Elev= 30
  4430.3  392.08  4460.3  389.89  4500.3  388.35  4520.3  386.17  4580.3  382.26
  4600.3  380.35  4690.3   375.3  4750.3  371.72  4770.3   371.2  4790.3  369.63
  4800.3  369.61  4840.3  367.53  4860.3  367.07  4870.3  367.68  4890.3  367.17
  4900.3  366.29  4930.3  365.26  4960.3   365.2  4970.3  363.07  4990.4  362.81
  4993.4  356.81  5006.7  356.81  5009.7  362.81    5060  362.92    5070  368.17
    5080  374.93    5100  389.96    5110  395.34    5120  399.39  5130.2  402.43
#Mann= 3 , 1 , 0
 4430.30    0.13       0  4990.4   0.042       0  5009.7    0.13       0
Bank Sta=4990.40,5009.70
Exp/Cntr=0.3,0.1

Type RM Length L Ch R = 1 ,237920.2,998.3,998.3,998.3
BEGIN DESCRIPTION:
Sandy Creek 237.5
END DESCRIPTION:
#Sta/Elev= 17
  4669.5   398.2  4709.5  395.87  4739.5  393.06  4749.5  392.48  4799.5  385.46
  4879.5  369.76  4990.4   359.6  4993.4   353.6  5006.6   353.6  5009.6   359.6
  5036.4  359.23  5076.4  369.12  5086.4  370.48  5186.4  376.45  5246.4   383.9
  5276.4  386.29  5327.5  391.54
#Mann= 3 , 1 , 0
 4669.50    0.13       0  4990.4   0.042       0  5009.6    0.13       0
Bank Sta=4990.40,5009.60
Exp/Cntr=0.3,0.1

Type RM Length L Ch R = 1 ,236921.9,1121.8,1121.8,1121.8
BEGIN DESCRIPTION:
Sandy Creek 237.0
END DESCRIPTION:
#Sta/Elev= 30
  4639.7  375.81  4669.7  374.28  4699.7  373.83  4719.7  371.44  4759.7   363.7
  4769.7  362.13  4779.7  361.64  4789.7  361.75  4799.7  361.08  4809.7  361.08
  4819.7  359.72  4839.7  355.48  4869.7  351.48  4909.7  351.42  4919.7   352.5
  4929.7  352.85  4939.7  351.59  4949.7  349.61  4959.7  350.13  4990.4  348.31
  4993.4  342.31  5006.6  342.31  5009.6  348.31    5010  366.91    5020  376.88
    5030  383.21    5040  388.89    5050  395.65    5060  399.95  5065.6  401.13
#Mann= 3 , 1 , 0
 4639.70    0.13       0  4990.4   0.042       0  5009.6    0.13       0
Bank Sta=4990.40,5009.60
Exp/Cntr=0.3,0.1

Type RM Length L Ch R = 1 ,235800.1,979.1,979.1,979.1
BEGIN DESCRIPTION:
Sandy Creek 236.0
END DESCRIPTION:
#Sta/Elev= 29
  4578.7  375.76  4658.7  370.19  4678.7  368.27  4708.7  365.92  4728.7  362.87
  4738.7  362.23  4778.7  356.37  4788.7  354.34  4808.7  348.03  4818.7  345.82
  4838.7  342.63  4848.7  341.57  4868.7  341.12  4928.7  343.45  4989.2  341.08
  4992.2  335.08  5007.8  335.08  5010.8  341.08  5016.8   347.6  5026.8   349.4
  5076.8  353.24  5086.8  354.88  5096.8  355.74  5106.8  357.41  5156.8  362.67
  5176.8  365.76  5246.8  371.06  5266.8  373.13  5273.9  373.32
#Mann= 3 , 1 , 0
 4578.70    0.13       0  4989.2   0.042       0  5010.8    0.13       0
Bank Sta=4989.20,5010.80
Exp/Cntr=0.3,0.1

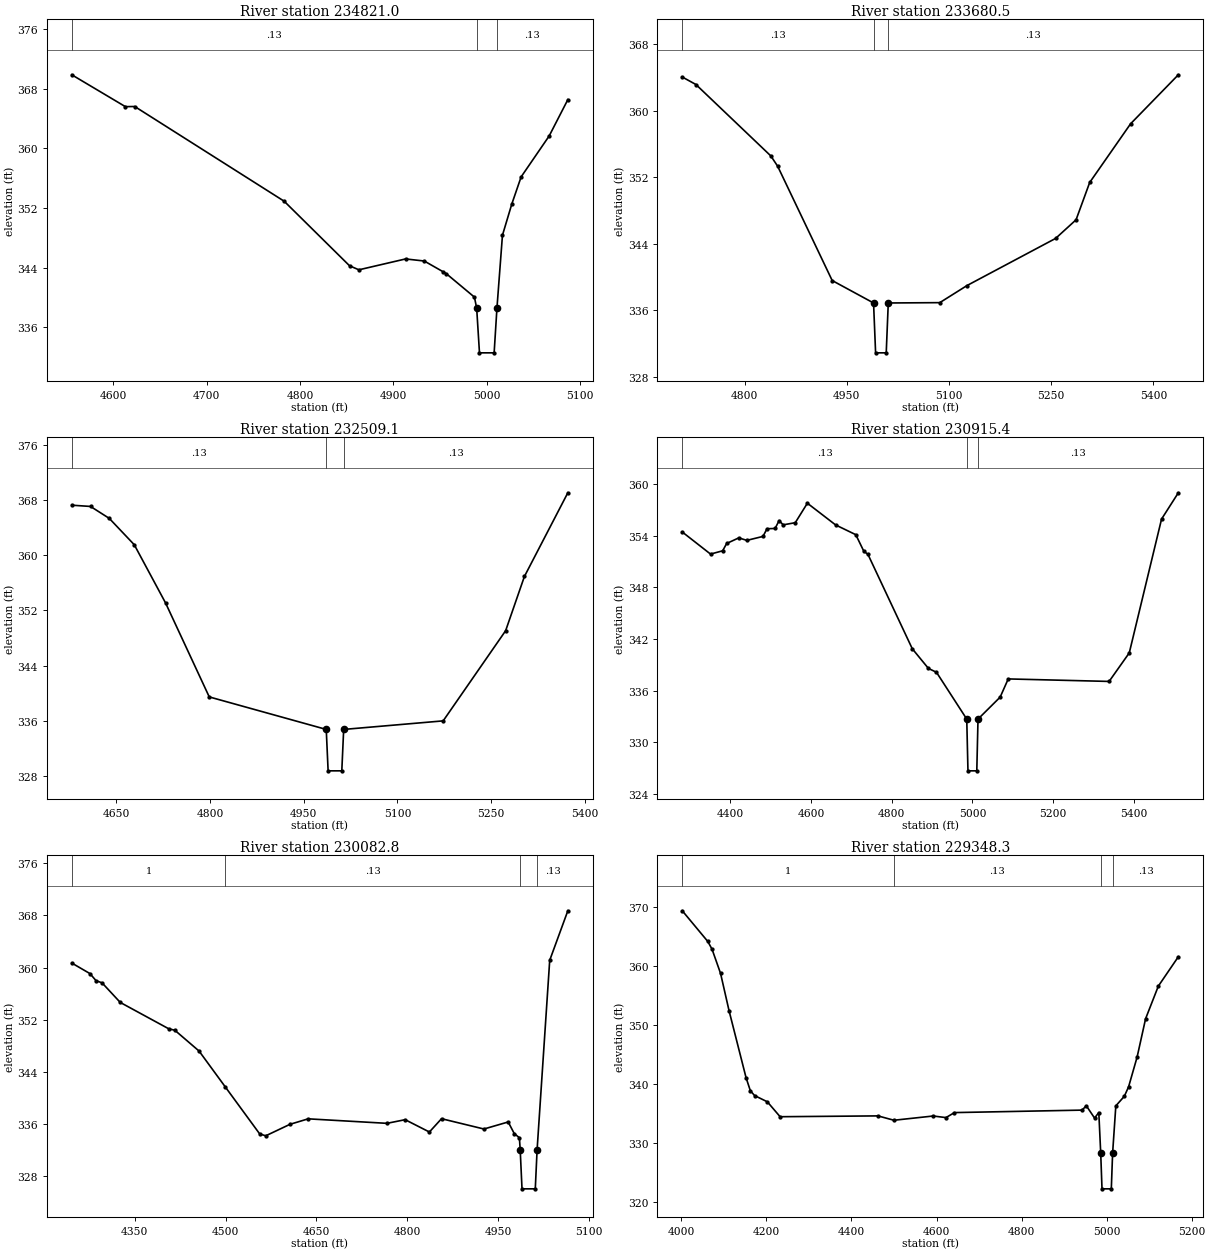
Type RM Length L Ch R = 1 ,234821.0,1140.5,1140.5,1140.5
BEGIN DESCRIPTION:
Sandy Creek 235.0
END DESCRIPTION:
#Sta/Elev= 20
  4555.7  369.89  4613.1  365.61  4623.1  365.63  4783.1  352.91  4853.1  344.24
  4863.1   343.7  4913.1  345.16  4933.1  344.88  4953.1  343.45  4956.8  343.17
  4986.8  340.03  4989.2  338.55  4992.2  332.55  5007.9  332.55  5010.9  338.55
  5016.8  348.34  5026.8  352.53  5036.8  356.18  5066.8  361.67  5086.8  366.55
#Mann= 3 , 1 , 0
 4555.70    0.13       0  4989.2   0.042       0  5010.9    0.13       0
Bank Sta=4989.20,5010.90
Exp/Cntr=0.3,0.1

Type RM Length L Ch R = 1 ,233680.5,1171.4,1171.4,1171.4
BEGIN DESCRIPTION:
Sandy Creek 234.0
END DESCRIPTION:
#Sta/Elev= 16
  4708.5  364.08  4728.5  363.18  4838.5  354.58  4848.5  353.34  4928.5  339.59
  4989.2  336.89  4992.2  330.89  5007.8  330.89  5010.8  336.89  5086.4  336.93
  5126.4  338.99  5256.4  344.66  5286.4   346.9  5306.4  351.39  5366.4  358.45
  5436.5  364.35
#Mann= 3 , 1 , 0
 4708.50    0.13       0  4989.2   0.042       0  5010.8    0.13       0
Bank Sta=4989.20,5010.80
Exp/Cntr=0.3,0.1

Type RM Length L Ch R = 1 ,232509.1,1593.7,1593.7,1593.7
BEGIN DESCRIPTION:
Sandy Creek 233.0
END DESCRIPTION:
#Sta/Elev= 14
  4578.9  367.25  4608.9  367.07  4638.9  365.34  4678.9  361.52  4728.9   353.1
  4798.9  339.47  4986.1  334.76  4989.1  328.76    5011  328.76    5014  334.76
  5173.2     336  5273.2  349.07  5303.2  356.92  5372.7  369.05
#Mann= 3 , 1 , 0
 4578.90    0.13       0  4986.1   0.042       0    5014    0.13       0
Bank Sta=4986.10,5014.00
Exp/Cntr=0.3,0.1

Type RM Length L Ch R = 1 ,230915.4,832.6,832.6,832.6
BEGIN DESCRIPTION:
Sandy Creek 232.0
END DESCRIPTION:
#Sta/Elev= 30
    4281  354.41    4351  351.85    4381  352.23    4391  353.08    4421  353.73
    4441  353.44    4481   353.9    4491  354.79    4511  354.82    4521  355.74
    4531  355.24    4561  355.49    4591  357.75    4661  355.23    4711   354.1
    4731  352.17    4741  351.83    4851  340.87    4891  338.59    4911  338.14
    4986  332.71    4989  326.71  5010.9  326.71  5013.9  332.71  5068.8  335.26
  5088.8  337.37  5338.8  337.08  5388.8  340.39  5468.8  355.91  5510.4  358.96
#Mann= 3 , 1 , 0
 4281.00    0.13       0    4986   0.042       0  5013.9    0.13       0
Bank Sta=4986.00,5013.90
Exp/Cntr=0.3,0.1

Type RM Length L Ch R = 1 ,230082.8,734.5,734.5,734.5
BEGIN DESCRIPTION:
Sandy Creek 231.0
END DESCRIPTION:
#Sta/Elev= 27
  4246.3   360.7  4276.3  359.08  4286.3     358  4296.3  357.66  4326.3  354.66
  4406.3  350.62  4416.3   350.4  4456.3  347.21  4499.9  341.67  4556.3  334.51
  4566.3  334.22  4606.3  335.98  4636.3  336.82  4766.3  336.13  4796.3  336.69
  4836.3   334.8  4856.3  336.84  4926.3  335.26  4966.3  336.34  4976.3  334.56
  4984.8  333.92  4986.1  332.09  4989.1  326.09    5011  326.09    5014  332.09
  5034.8  361.12  5064.7  368.71
#Mann= 4 , 1 , 0
 4246.30       1       0  4499.9    0.13       0  4986.1   0.042       0
    5014    0.13       0
Bank Sta=4986.10,5014.00
Exp/Cntr=0.3,0.1

Type RM Length L Ch R = 1 ,229348.3,604.9,604.9,604.9
BEGIN DESCRIPTION:
Sandy Creek 230.0
END DESCRIPTION:
#Sta/Elev= 30
  4002.2  369.43  4062.2  364.22  4072.2   362.9  4092.2   358.8  4112.2  352.46
  4152.2  341.09  4162.2   338.9  4172.2  338.07  4202.2  337.01  4232.2  334.48
  4462.2  334.62  4499.9  333.88  4592.2   334.6  4622.2  334.33  4642.2  335.18
  4942.2   335.6  4952.2  336.34  4971.6  334.25  4981.6  335.19  4986.1  328.24
  4989.1  322.24    5011  322.24    5014  328.24  5021.6  336.32  5041.6  337.95
  5051.6  339.55  5071.6  344.59  5091.6  351.11  5121.6  356.65  5168.6  361.63
#Mann= 4 , 1 , 0
 4002.20       1       0  4499.9    0.13       0  4986.1   0.042       0
    5014    0.13       0
Bank Sta=4986.10,5014.00
Exp/Cntr=0.3,0.1

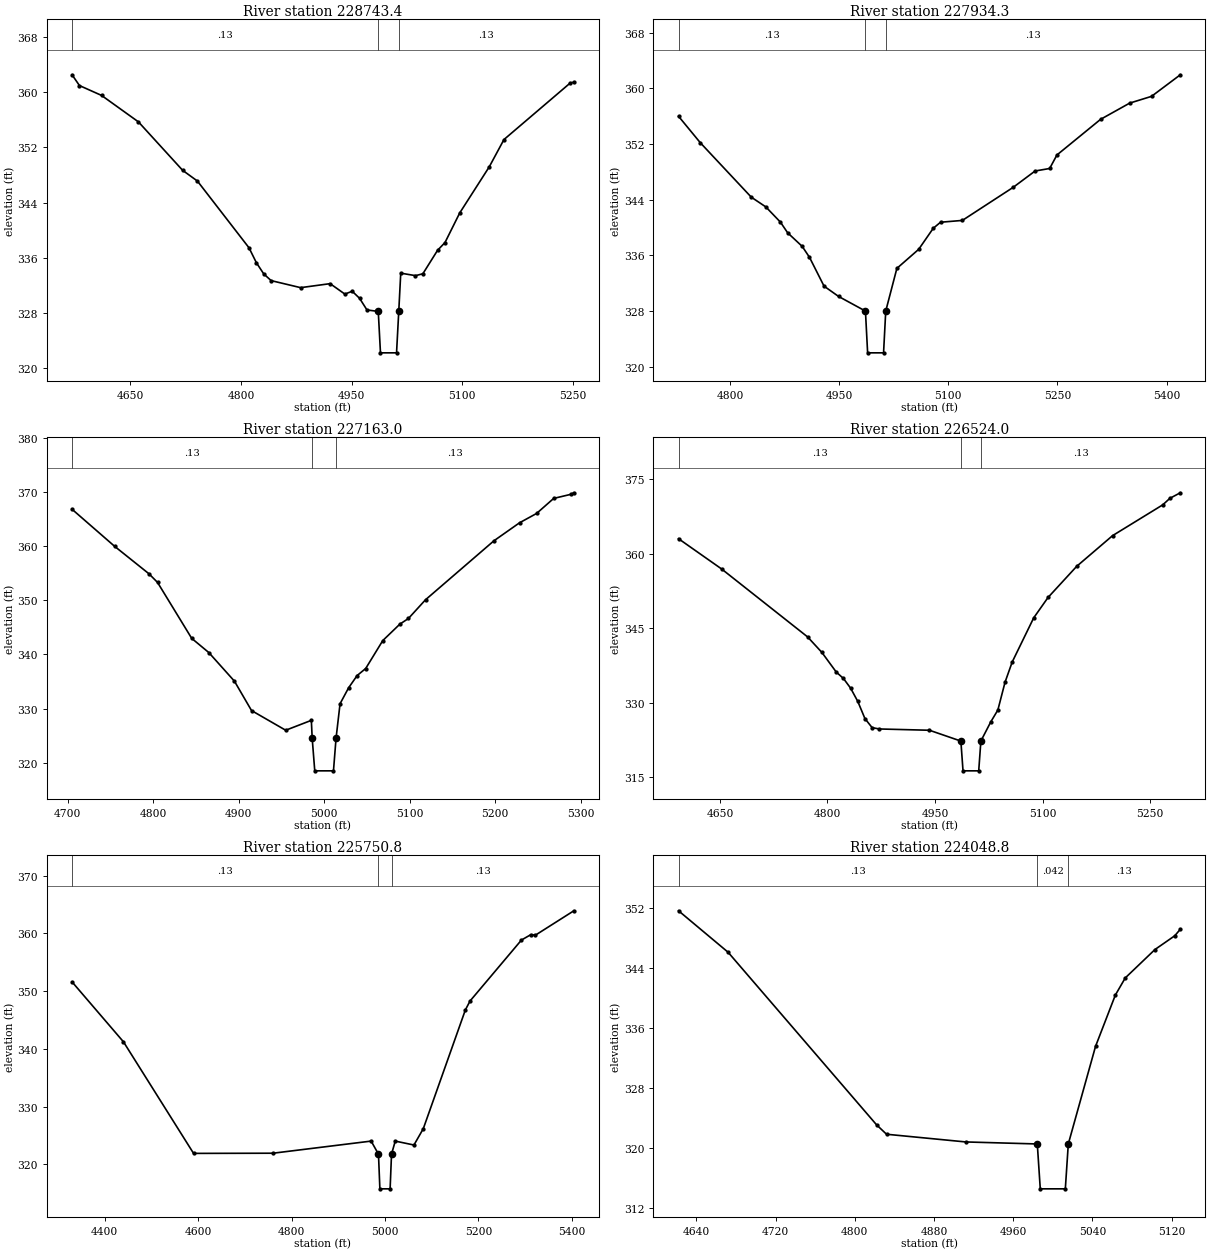
Type RM Length L Ch R = 1 ,228743.4,809.1,809.1,809.1
BEGIN DESCRIPTION:
Sandy Creek 229.0
END DESCRIPTION:
#Sta/Elev= 30
  4570.8  362.51  4580.8  360.95  4610.8  359.52  4660.8  355.69  4720.8  348.67
  4740.8  347.12  4810.8  337.45  4820.8  335.29  4830.8  333.67  4840.8   332.7
  4880.8  331.68  4920.8  332.26  4940.8  330.75  4950.8  331.16  4960.8  330.13
  4970.8  328.45  4986.1  328.24  4989.1  322.24  5010.9  322.24  5013.9  328.24
  5016.6  333.78  5036.6  333.42  5046.6  333.69  5066.6   337.1  5076.6  338.21
  5096.6   342.5  5136.6  349.17  5156.6  353.13  5246.6  361.33  5251.4  361.43
#Mann= 3 , 1 , 0
 4570.80    0.13       0  4986.1   0.042       0  5013.9    0.13       0
Bank Sta=4986.10,5013.90
Exp/Cntr=0.3,0.1

Type RM Length L Ch R = 1 ,227934.3,771.3,771.3,771.3
BEGIN DESCRIPTION:
Sandy Creek 228.0
END DESCRIPTION:
#Sta/Elev= 27
  4729.2  355.99  4759.2  352.18  4829.2  344.37  4849.2  342.97  4869.2  340.79
  4879.2  339.25  4899.2   337.3  4909.2  335.73  4929.2  331.59  4949.2  330.11
  4986.1  328.01  4989.1  322.01    5011  322.01    5014  328.01  5029.3  334.14
  5059.3  336.88  5079.3   339.9  5089.3  340.77  5119.3  341.03  5189.3  345.79
  5219.3  348.13  5239.3  348.49  5249.3  350.43  5309.3  355.55  5349.3  357.88
  5379.3  358.85  5418.9  361.95
#Mann= 3 , 1 , 0
 4729.20    0.13       0  4986.1   0.042       0    5014    0.13       0
Bank Sta=4986.10,5014.00
Exp/Cntr=0.3,0.1

Type RM Length L Ch R = 1 ,227163.0,639,639,639
BEGIN DESCRIPTION:
Sandy Creek 227.0
END DESCRIPTION:
#Sta/Elev= 28
    4705  366.82    4755  359.95    4795   354.9    4805  353.31    4845  342.97
    4865  340.35    4895  335.06    4915  329.63    4955  325.99    4985  327.82
    4986  324.49    4989  318.49  5010.9  318.49  5013.9  324.49  5018.6  330.89
  5028.6  333.83  5038.6   336.1  5048.6   337.4  5068.6  342.56  5088.6   345.6
  5098.6  346.64  5118.6   350.1  5198.6  360.99  5228.6  364.32  5248.6  366.05
  5268.6  368.83  5288.6  369.58  5292.2  369.87
#Mann= 3 , 1 , 0
 4705.00    0.13       0    4986   0.042       0  5013.9    0.13       0
Bank Sta=4986.00,5013.90
Exp/Cntr=0.3,0.1

Type RM Length L Ch R = 1 ,226524.0,773.2,773.2,773.2
BEGIN DESCRIPTION:
Sandy Creek 226.0
END DESCRIPTION:
#Sta/Elev= 27
  4592.3  363.05  4652.3  356.96  4772.3  343.26  4792.3  340.12  4812.3  336.17
  4822.3  334.88  4832.3  332.93  4842.3  330.26  4852.3  326.79  4862.3  324.97
  4872.3   324.7  4942.3  324.44  4986.1  322.26  4989.1  316.26    5011  316.26
    5014  322.26  5027.7   326.1  5037.7  328.52  5047.7  334.12  5057.7   338.2
  5087.7   347.1  5107.7  351.21  5147.7  357.49  5197.7  363.67  5267.7  369.88
  5277.7   371.2  5292.2  372.31
#Mann= 3 , 1 , 0
 4592.30    0.13       0  4986.1   0.042       0    5014    0.13       0
Bank Sta=4986.10,5014.00
Exp/Cntr=0.3,0.1

Type RM Length L Ch R = 1 ,225750.8,1702,1702,1702
BEGIN DESCRIPTION:
Sandy Creek 225.0
END DESCRIPTION:
#Sta/Elev= 18
  4330.4  351.59  4440.4  341.21  4590.4  321.89  4760.4  321.92  4970.4  324.02
  4986.1  321.75  4989.1  315.75    5011  315.75    5014  321.75    5022  324.02
    5062  323.34    5082  326.17    5172  346.73    5182  348.28    5292  358.84
    5312  359.77    5322  359.69  5404.2  363.91
#Mann= 3 , 1 , 0
 4330.40    0.13       0  4986.1   0.042       0    5014    0.13       0
Bank Sta=4986.10,5014.00
Exp/Cntr=0.3,0.1

Type RM Length L Ch R = 1 ,224048.8,1425.5,1425.5,1425.5
BEGIN DESCRIPTION:
Sandy Creek 224.0
END DESCRIPTION:
#Sta/Elev= 15
  4622.1  351.69  4672.1  346.15  4822.1  323.06  4832.1  321.81  4912.1  320.78
  4984.3  320.51  4987.3  314.51  5012.6  314.51  5015.6  320.51  5043.1  333.56
  5063.1  340.42  5073.1  342.71  5103.1  346.51  5123.1  348.35  5128.7  349.22
#Mann= 3 , 1 , 0
 4622.10    0.13       0  4984.3   0.042       0  5015.6    0.13       0
Bank Sta=4984.30,5015.60
Exp/Cntr=0.3,0.1

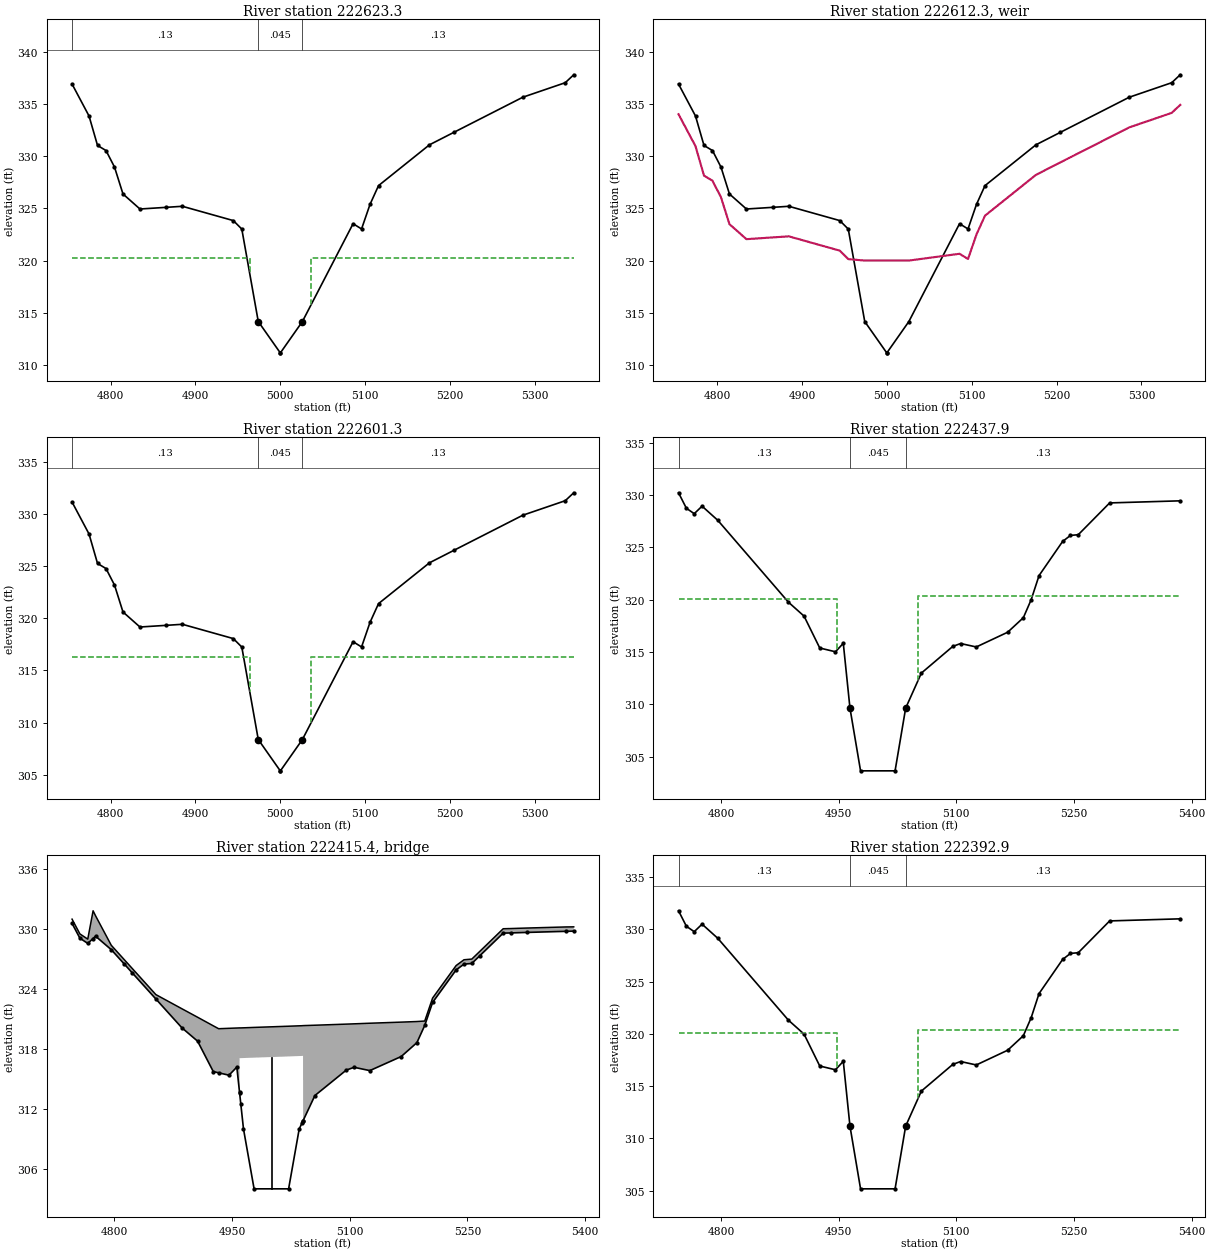
Type RM Length L Ch R = 1 ,222623.3,22,22,22
BEGIN DESCRIPTION:
Upstream Section of Bridge/Culvert/Weir
END DESCRIPTION:
#Sta/Elev= 24
  4754.6  336.91  4774.6  333.85  4784.6  331.03  4794.6  330.54  4804.6  328.96
  4814.6  326.38  4834.6  324.94  4865.6   325.1  4884.6   325.2  4944.6  323.83
  4954.6  323.02    4974  314.16  4999.9  311.16  5000.1  311.16    5026  314.16
  5085.7  323.53  5095.7  323.03  5105.7  325.39  5115.7  327.18  5175.7  331.09
  5204.6  332.29  5285.7  335.65  5335.7  337.04  5345.7   337.8
#Mann= 3 , 1 , 0
 4754.60    0.13       0    4974   0.045       0    5026    0.13       0
#XS Ineff= 2 , 0
       0    4964  320.24    5036       0  320.24
Bank Sta=4974.00,5026.00
Exp/Cntr=0.5,0.3

Type RM Length L Ch R = 5 ,222612.3,,,
BEGIN DESCRIPTION:
Dam_Weldon Mill Rd_2
Structure ID: Dam_weldon Mill Rd
Approximate Survey Structure
END DESCRIPTION:
#Inline Weir SE= 24
  4754.6  334.02  4774.6  330.96  4784.6  328.14  4794.6  327.65  4804.6  326.07
  4814.6  323.49  4834.6  322.05  4865.6  322.22  4884.6  322.32  4944.6  320.95
  4954.6  320.14    4974     320  4999.9     320  5000.1     320    5026     320
  5085.7  320.65  5095.7  320.15  5105.7  322.51  5115.7   324.3  5175.7  328.21
  5204.6  329.41  5285.7  332.76  5335.7  334.15  5345.7  334.91
IW Dist,WD,Coef,Skew,MaxSub,Min_El,Is_Ogee,SpillHt,DesHd
10.0,2.0,3.0,,0.95,, 0 ,,,2.0,2.0,

Type RM Length L Ch R = 1 ,222601.3,163.4,163.4,163.4
BEGIN DESCRIPTION:
Downstream Section of Bridge/Culvert/Weir
END DESCRIPTION:
#Sta/Elev= 24
  4754.6  331.13  4774.6  328.07  4784.6  325.25  4794.6  324.76  4804.6  323.18
  4814.6   320.6  4834.6  319.16  4865.6  319.32  4884.6  319.42  4944.6  318.05
  4954.6  317.24    4974  308.38  4999.9  305.38  5000.1  305.38    5026  308.38
  5085.7  317.75  5095.7  317.25  5105.7  319.61  5115.7   321.4  5175.7  325.31
  5204.6  326.51  5285.7  329.87  5335.7  331.26  5345.7  332.02
#Mann= 3 , 1 , 0
 4754.60    0.13       0    4974   0.045       0    5026    0.13       0
#XS Ineff= 2 , 0
       0    4964  316.24    5036       0  316.24
Bank Sta=4974.00,5026.00
Exp/Cntr=0.5,0.3

Type RM Length L Ch R = 1 ,222437.9,45,45,45
BEGIN DESCRIPTION:
Upstream Section of Bridge/Culvert/Weir
END DESCRIPTION:
#Sta/Elev= 27
    4746  330.23    4756  328.75    4766  328.23    4776  328.95    4796   327.6
    4886  319.77    4906  318.43    4926  315.38    4946  315.02    4956  315.83
  4964.5  309.63    4978  303.63    5022  303.63  5035.5  309.63  5055.5  312.98
  5095.5  315.53  5105.5  315.81  5125.5  315.48  5165.5  316.89  5185.5  318.28
  5195.5  320.01  5205.5  322.31  5235.5  325.57  5245.5  326.15  5255.5  326.22
  5295.5  329.26  5385.4  329.46
#Mann= 3 , 1 , 0
 4746.00    0.13       0  4964.5   0.045       0  5035.5    0.13       0
#XS Ineff= 2 , 0
       0    4948  320.04    5051       0  320.39
Bank Sta=4964.50,5035.50
Exp/Cntr=0.5,0.3

Type RM Length L Ch R = 3 ,222415.4,,,
BEGIN DESCRIPTION:
Weldon Mill Rd-1-TOR
Structure ID: Weldon Mill Rd-Bridge
Approximate Survey Structure
END DESCRIPTION:
Bridge Culvert--1,0,-1,-1, 0
Deck Dist Width WeirC Skew NumUp NumDn MinLoCord MaxHiCord MaxSubmerge Is_Ogee
10,25,2.6,,42,42,,,0.95,0,1,1,,
    4746    4756    4766  4772.8    4776    4796  4812.8  4822.8  4852.8    4886
    4906    4926  4932.8    4946    4956 4959.41  4959.5    4961  4964.5    4978
    5022  5035.5    5039 5040.39  5040.5  5055.5  5095.5  5105.5  5125.5  5165.5
  5185.5  5195.5  5205.5  5235.5  5245.5  5255.5  5265.4  5295.5  5305.4  5325.4
  5375.4  5385.4
     331  329.52     329  331.84  331.33  328.38  326.92  326.05  323.44  322.02
  321.17  320.31  320.02  320.06  320.09   320.1   320.1   320.1  320.11  320.15
  320.27  320.31  320.32  320.33  320.33  320.37  320.48  320.51  320.57  320.68
  320.74  320.79  323.09  326.35  326.93     327  327.75  330.04  330.06  330.11
  330.22  330.23
  330.57  329.09  328.57  329.06  329.29  327.94  326.48  325.61     323  320.11
  318.77  315.72   315.6  315.36  316.17  313.68  317.07  317.07  317.08  317.12
  317.24  317.28  317.29   317.3  310.81  313.32  315.87  316.15  315.82  317.23
  318.62  320.35  322.65  325.91  326.49  326.56  327.31   329.6  329.62  329.67
  329.78   329.8
    4746    4756    4766  4772.8    4776    4796  4812.8  4822.8  4852.8    4886
    4906    4926  4932.8    4946    4956 4959.41  4959.5    4961  4964.5    4978
    5022  5035.5    5039 5040.39  5040.5  5055.5  5095.5  5105.5  5125.5  5165.5
  5185.5  5195.5  5205.5  5235.5  5245.5  5255.5  5265.4  5295.5  5305.4  5325.4
  5375.4  5385.4
  331.43  329.95  329.43  331.84  331.33   328.8  327.34  326.47  323.86  322.02
  321.17  320.31  320.02  320.06  320.09   320.1   320.1   320.1  320.11  320.15
  320.27  320.31  320.32  320.33  320.33  320.37  320.48  320.51  320.57  320.68
  320.74  321.21  323.51  326.77  327.35  327.42  328.17  330.46  330.48  330.53
  330.64  330.66
  331.43  329.95  329.43  329.92  330.15   328.8  327.34  326.47  323.86  320.97
  319.63  316.58  316.46  316.22  317.03  314.54  317.93  317.93  317.94  317.98
   318.1  318.14  318.15  318.16  311.67  314.18  316.73  317.01  316.68  318.09
  319.48  321.21  323.51  326.77  327.35  327.42  328.17  330.46  330.48  330.53
  330.64  330.66
Pier Skew, UpSta & Num, DnSta & Num=,5000.0, 2 ,5000.0, 2 , 0 , 0 , 0 ,,
       1       1
  302.97  318.18
       1       1
  303.83  319.04
Abutment Skew #Up #Dn=, 2 , 2
 4959.30 4961.00
  317.07  312.52
 4959.30 4961.00
  317.93  313.38
Abutment Skew #Up #Dn=, 2 , 2
 5039.00 5040.59
  310.56  317.30
 5039.00 5040.59
  311.42  318.16
BR Coef= 1 , 1 , 0 ,1.25, 0 ,,,0.8,0,2,0,
Wspro=,,,, 1 ,,,, 0 ,,,, 0 ,,,,-1 ,-1 ,-1 , 0 , 0 , 0 , 0 , 0
BC Design=,, 0 ,, 0 ,,,,,,
BR U #Sta/Elev= 42
    4746  330.57    4756  329.09    4766  328.57  4772.8  329.06    4776  329.29
    4796  327.94  4812.8  326.48  4822.8  325.61  4852.8     323    4886  320.11
    4906  318.77    4926  315.72  4932.8   315.6    4946  315.36    4956  316.17
 4959.41  313.68  4959.5  313.62    4961  312.52  4964.5  309.97    4978  303.97
    5022  303.97  5035.5  309.97    5039  310.56 5040.39  310.79  5040.5  310.81
  5055.5  313.32  5095.5  315.87  5105.5  316.15  5125.5  315.82  5165.5  317.23
  5185.5  318.62  5195.5  320.35  5205.5  322.65  5235.5  325.91  5245.5  326.49
  5255.5  326.56  5265.4  327.31  5295.5   329.6  5305.4  329.62  5325.4  329.67
  5375.4  329.78  5385.4   329.8
BR U #Mann= 3
 4746.00    0.13  4964.5   0.045  5035.5    0.13
BR U Banks=4964.50,5035.50
BR D #Sta/Elev= 42
    4746  331.43    4756  329.95    4766  329.43  4772.8  329.92    4776  330.15
    4796   328.8  4812.8  327.34  4822.8  326.47  4852.8  323.86    4886  320.97
    4906  319.63    4926  316.58  4932.8  316.46    4946  316.22    4956  317.03
 4959.41  314.54  4959.5  314.48    4961  313.38  4964.5  310.83    4978  304.83
    5022  304.83  5035.5  310.83    5039  311.42 5040.39  311.65  5040.5  311.67
  5055.5  314.18  5095.5  316.73  5105.5  317.01  5125.5  316.68  5165.5  318.09
  5185.5  319.48  5195.5  321.21  5205.5  323.51  5235.5  326.77  5245.5  327.35
  5255.5  327.42  5265.4  328.17  5295.5  330.46  5305.4  330.48  5325.4  330.53
  5375.4  330.64  5385.4  330.66
BR D #Mann= 3
 4746.00    0.13  4964.5   0.045  5035.5    0.13
BR D Banks=4964.50,5035.50

Type RM Length L Ch R = 1 ,222392.9,2003.4,2003.4,2003.4
BEGIN DESCRIPTION:
Downstream Section of Bridge/Culvert/Weir
END DESCRIPTION:
#Sta/Elev= 27
    4746  331.77    4756  330.29    4766  329.77    4776  330.49    4796  329.14
    4886  321.31    4906  319.97    4926  316.92    4946  316.56    4956  317.37
  4964.5  311.17    4978  305.17    5022  305.17  5035.5  311.17  5055.5  314.52
  5095.5  317.07  5105.5  317.35  5125.5  317.02  5165.5  318.43  5185.5  319.82
  5195.5  321.55  5205.5  323.85  5235.5  327.11  5245.5  327.69  5255.5  327.76
  5295.5   330.8  5385.4     331
#Mann= 3 , 1 , 0
 4746.00    0.13       0  4964.5   0.045       0  5035.5    0.13       0
#XS Ineff= 2 , 0
       0    4948  320.04    5051       0  320.39
Bank Sta=4964.50,5035.50
Exp/Cntr=0.5,0.3

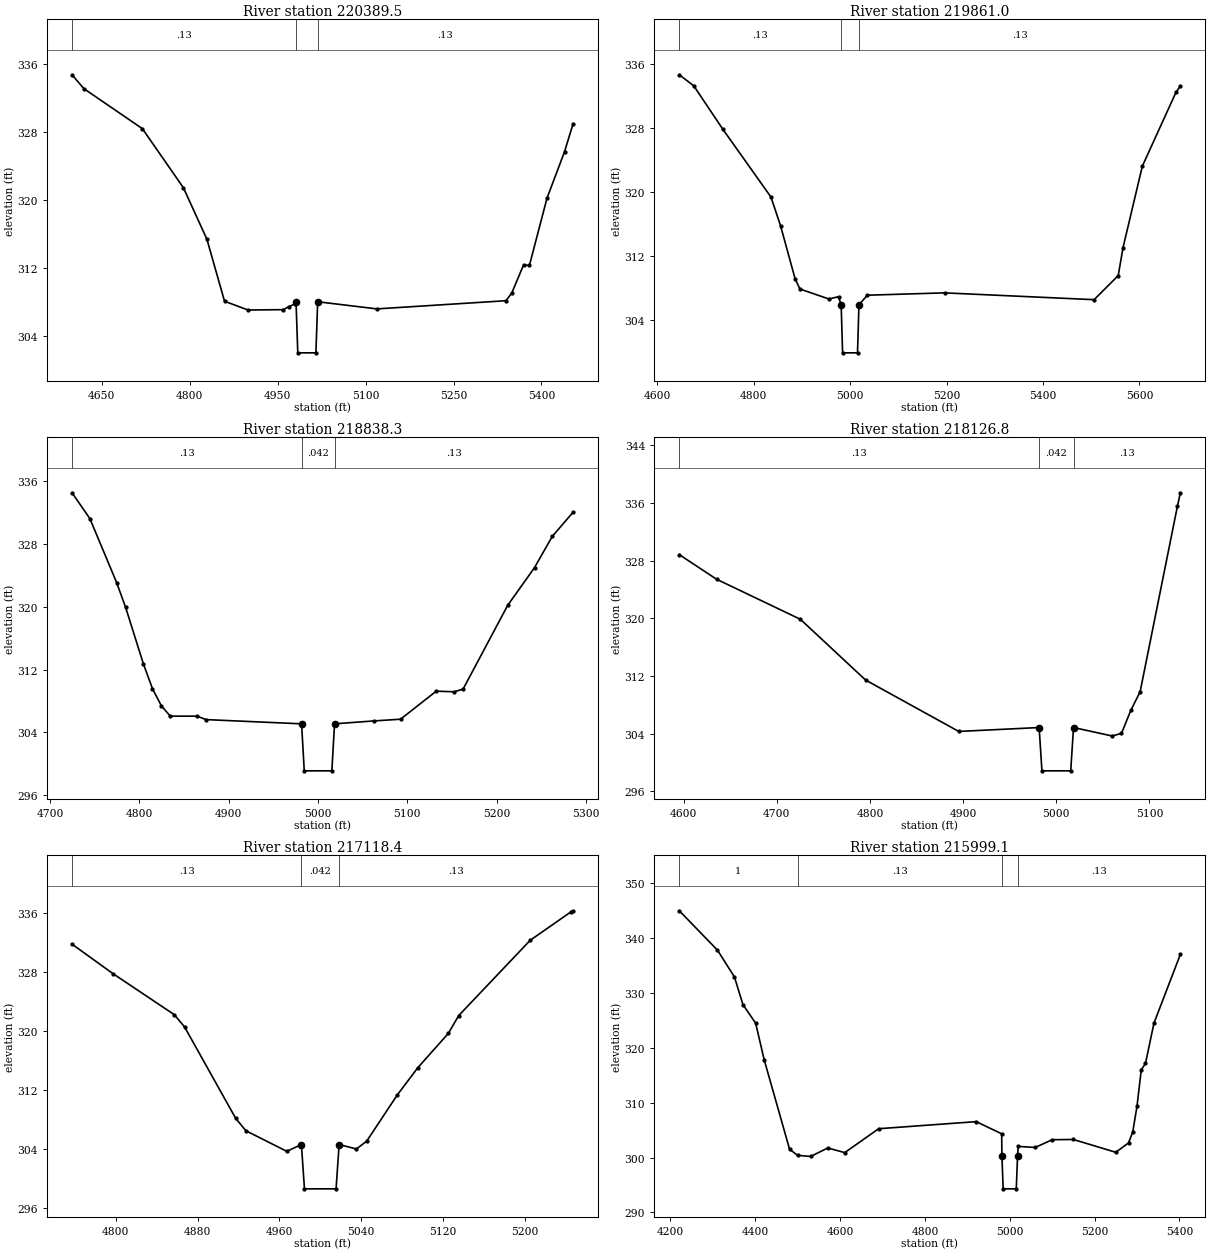
Type RM Length L Ch R = 1 ,220389.5,528.5,528.5,528.5
BEGIN DESCRIPTION:
Sandy Creek 221.0
END DESCRIPTION:
#Sta/Elev= 22
  4599.6   334.7  4619.6  333.08  4719.6  328.37  4789.6  321.42  4829.6  315.38
  4859.6  308.11  4899.6  307.08  4959.6  307.12  4969.4  307.48  4979.4  307.78
  4981.5  308.05  4984.5  302.05  5015.4  302.05  5018.4  308.05  5119.4  307.21
  5339.4  308.17  5349.4  309.08  5369.4  312.37  5379.4  312.31  5409.4  320.21
  5439.4  325.69  5453.9  328.96
#Mann= 3 , 1 , 0
 4599.60    0.13       0  4981.5   0.042       0  5018.4    0.13       0
Bank Sta=4981.50,5018.40
Exp/Cntr=0.3,0.1

Type RM Length L Ch R = 1 ,219861.0,1022.7,1022.7,1022.7
BEGIN DESCRIPTION:
Sandy Creek 220.0
END DESCRIPTION:
#Sta/Elev= 21
  4646.1  334.68  4676.1   333.3  4736.1   327.9  4836.1  319.41  4856.1   315.8
  4886.1  309.21  4896.1  307.92  4956.1  306.68  4976.1  306.96  4981.6  305.95
  4984.6  299.95  5015.5  299.95  5018.5  305.95  5035.9  307.15  5195.9  307.44
  5505.9  306.59  5555.9   309.6  5565.9   313.1  5605.9  323.27  5675.9  332.53
  5684.7  333.26
#Mann= 3 , 1 , 0
 4646.10    0.13       0  4981.6   0.042       0  5018.5    0.13       0
Bank Sta=4981.60,5018.50
Exp/Cntr=0.3,0.1

Type RM Length L Ch R = 1 ,218838.3,711.5,711.5,711.5
BEGIN DESCRIPTION:
Sandy Creek 219.0
END DESCRIPTION:
#Sta/Elev= 23
  4724.6  334.56  4744.6  331.26  4774.6  323.08  4784.6  319.93  4804.6  312.69
  4814.6  309.57  4824.6  307.37  4834.6  306.05  4864.6  306.05  4874.6  305.61
  4981.6  305.07  4984.6  299.07  5015.5  299.07  5018.5  305.07  5062.4  305.44
  5092.4  305.66  5132.4  309.24  5152.4  309.16  5162.4   309.5  5212.4   320.2
  5242.4  325.01  5262.4  329.01  5285.6  332.08
#Mann= 3 , 1 , 0
 4724.60    0.13       0  4981.6   0.042       0  5018.5    0.13       0
Bank Sta=4981.60,5018.50
Exp/Cntr=0.3,0.1

Type RM Length L Ch R = 1 ,218126.8,1008.4,1008.4,1008.4
BEGIN DESCRIPTION:
Sandy Creek 218.0
END DESCRIPTION:
#Sta/Elev= 15
  4595.3  328.82  4635.3  325.41  4725.3  319.86  4795.3  311.44  4895.3  304.32
  4981.6  304.86  4984.6  298.86  5015.5  298.86  5018.5  304.86    5060  303.69
    5070  304.05    5080  307.23    5090  309.82    5130   335.5  5133.2  337.39
#Mann= 3 , 1 , 0
 4595.30    0.13       0  4981.6   0.042       0  5018.5    0.13       0
Bank Sta=4981.60,5018.50
Exp/Cntr=0.3,0.1

Type RM Length L Ch R = 1 ,217118.4,1119.3,1119.3,1119.3
BEGIN DESCRIPTION:
Sandy Creek 217.0
END DESCRIPTION:
#Sta/Elev= 20
  4757.2  331.73  4797.2  327.74  4857.2  322.18  4867.2  320.53  4917.2  308.15
  4927.2  306.46  4967.2  303.67  4981.5  304.59  4984.5  298.59  5015.4  298.59
  5018.4  304.59  5035.3  303.99  5045.3  305.04  5075.3  311.31  5095.3  314.99
  5125.3  319.66  5135.3  322.05  5205.3  332.26  5245.3  336.12  5247.2  336.25
#Mann= 3 , 1 , 0
 4757.20    0.13       0  4981.5   0.042       0  5018.4    0.13       0
Bank Sta=4981.50,5018.40
Exp/Cntr=0.3,0.1

Type RM Length L Ch R = 1 ,215999.1,1006,1006,1006
BEGIN DESCRIPTION:
Sandy Creek 216.0
END DESCRIPTION:
#Sta/Elev= 30
    4221   344.9    4311  337.74    4351  332.86    4371  327.83    4401  324.45
    4421  317.82    4481   301.5  4499.9  300.39    4531   300.2    4571  301.74
    4611  300.89    4691  305.24    4921  306.53    4981  304.31  4981.5   300.3
  4984.5   294.3  5015.4   294.3  5018.4   300.3    5020  302.02    5060  301.83
    5100  303.24    5150  303.28    5250  300.95    5280  302.66    5290  304.67
    5300  309.34    5310  315.94    5320  317.14    5340  324.46  5402.2  336.96
#Mann= 4 , 1 , 0
 4221.00       1       0  4499.9    0.13       0  4981.5   0.042       0
  5018.4    0.13       0
Bank Sta=4981.50,5018.40
Exp/Cntr=0.3,0.1

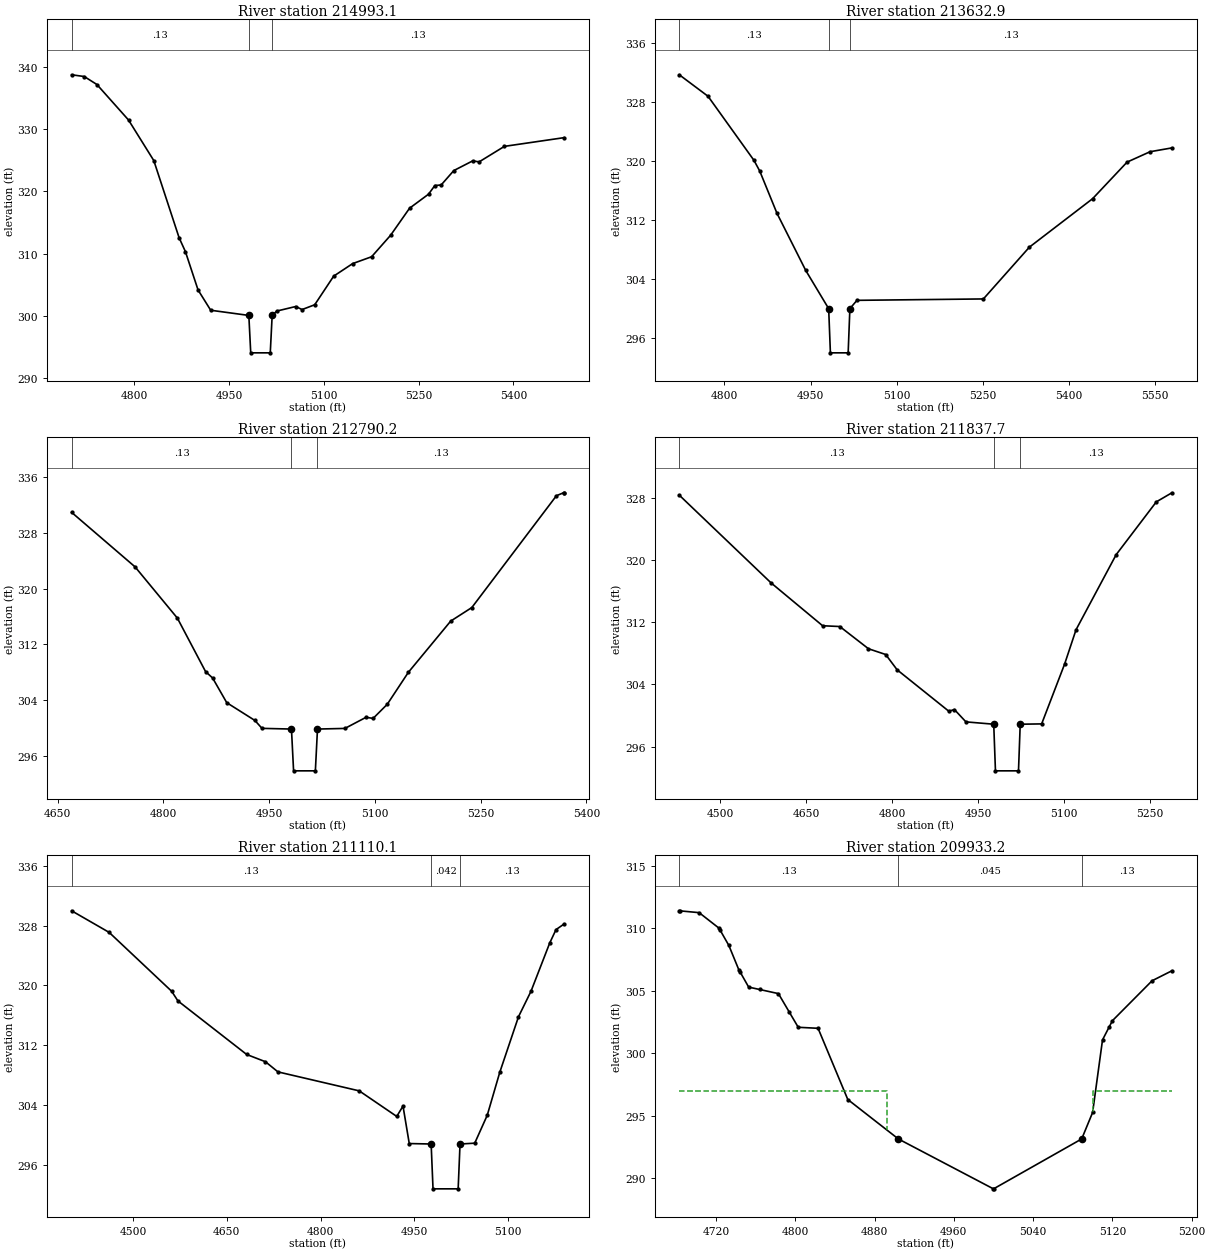
Type RM Length L Ch R = 1 ,214993.1,1360.2,1360.2,1360.2
BEGIN DESCRIPTION:
Sandy Creek 215.0
END DESCRIPTION:
#Sta/Elev= 30
  4701.2  338.68  4721.2   338.4  4741.2  337.12  4791.2  331.43  4831.2  324.92
  4871.2  312.55  4881.2  310.32  4901.2  304.17  4921.2  300.92  4981.5  300.09
  4984.5  294.09  5015.4  294.09  5018.4  300.09  5025.7  300.79  5055.7  301.52
  5065.7  301.03  5085.7   301.8  5115.7  306.39  5145.7   308.4  5175.7   309.5
  5205.7  312.94  5235.7  317.28  5265.7  319.53  5275.7  320.92  5285.7  321.01
  5305.7  323.32  5335.7  324.88  5345.7  324.71  5385.7   327.2  5480.3   328.6
#Mann= 3 , 1 , 0
 4701.20    0.13       0  4981.5   0.042       0  5018.4    0.13       0
Bank Sta=4981.50,5018.40
Exp/Cntr=0.3,0.1

Type RM Length L Ch R = 1 ,213632.9,842.7,842.7,842.7
BEGIN DESCRIPTION:
Sandy Creek 214.0
END DESCRIPTION:
#Sta/Elev= 17
  4721.7  331.68  4771.7  328.76  4851.7  320.05  4861.7   318.6  4891.7  312.86
  4941.7  305.11  4981.6  299.92  4984.6  293.92  5015.5  293.92  5018.5  299.92
  5030.8  301.05  5250.8  301.24  5330.8  308.27  5440.8  314.85  5500.8  319.82
  5540.8  321.23  5578.8  321.75
#Mann= 3 , 1 , 0
 4721.70    0.13       0  4981.6   0.042       0  5018.5    0.13       0
Bank Sta=4981.60,5018.50
Exp/Cntr=0.3,0.1

Type RM Length L Ch R = 1 ,212790.2,952.5,952.5,952.5
BEGIN DESCRIPTION:
Sandy Creek 213.0
END DESCRIPTION:
#Sta/Elev= 22
  4669.8  330.94  4759.8  323.11  4819.8  315.75  4859.8  308.07  4869.8  307.15
  4889.8  303.61  4929.8  301.05  4939.8  299.92  4981.6  299.82  4984.6  293.82
  5015.5  293.82  5018.5  299.82  5057.4  299.91  5087.4  301.51  5097.4  301.35
  5117.4  303.37  5147.4  307.97  5207.4  315.32  5237.4  317.27  5357.4  333.33
  5367.4  333.75  5368.4  333.71
#Mann= 3 , 1 , 0
 4669.80    0.13       0  4981.6   0.042       0  5018.5    0.13       0
Bank Sta=4981.60,5018.50
Exp/Cntr=0.3,0.1

Type RM Length L Ch R = 1 ,211837.7,727.6,727.6,727.6
BEGIN DESCRIPTION:
Sandy Creek 212.0
END DESCRIPTION:
#Sta/Elev= 20
  4428.4  328.35  4588.4  317.07  4678.4  311.55  4708.4  311.45  4758.4  308.59
  4788.4  307.85  4808.4  305.88  4898.4  300.56  4908.4  300.76  4928.4  299.18
  4976.9  298.88  4979.9  292.88  5020.1  292.88  5023.1  298.88  5060.5  298.92
  5100.5  306.61  5120.5  311.04  5190.5   320.7  5260.5  327.49  5287.7  328.66
#Mann= 3 , 1 , 0
 4428.40    0.13       0  4976.9   0.042       0  5023.1    0.13       0
Bank Sta=4976.90,5023.10
Exp/Cntr=0.3,0.1

Type RM Length L Ch R = 1 ,211110.1,1176.9,1176.9,1176.9
BEGIN DESCRIPTION:
Sandy Creek 211.0
END DESCRIPTION:
#Sta/Elev= 23
  4401.9  329.99  4461.9   327.1  4561.9  319.22  4571.9  317.93  4681.9  310.76
  4711.9  309.79  4731.9  308.43  4861.9  305.89  4921.9  302.47  4931.9  303.86
  4941.9  298.84  4976.9  298.78  4979.9  292.78  5020.1  292.78  5023.1  298.78
  5046.6  298.89  5066.6  302.62  5086.6  308.36  5116.6  315.81  5136.6  319.22
  5166.6  325.69  5176.6  327.47  5189.7  328.23
#Mann= 3 , 1 , 0
 4401.90    0.13       0  4976.9   0.042       0  5023.1    0.13       0
Bank Sta=4976.90,5023.10
Exp/Cntr=0.3,0.1

Type RM Length L Ch R = 1 ,209933.2,23,23,23
BEGIN DESCRIPTION:
Upstream Section of Bridge/Culvert/Weir
END DESCRIPTION:
#Sta/Elev= 25
    4683  311.42  4684.1  311.41    4703  311.27    4723  310.03  4724.1  309.88
    4733  308.64    4743   306.7  4744.1  306.55    4753   305.3  4764.1  305.11
    4783  304.78  4794.1  303.28    4803  302.08    4823     302    4853  296.29
    4904  293.13  4999.9  289.13  5000.1  289.13    5089  293.13    5100  295.25
    5110  301.07  5116.8  302.12    5120  302.61    5160  305.81    5180  306.61
#Mann= 3 , 1 , 0
 4683.00    0.13       0    4904   0.045       0    5089    0.13       0
#XS Ineff= 2 , 0
       0    4893     297    5100       0     297
Bank Sta=4904.00,5089.00
Exp/Cntr=0.5,0.3