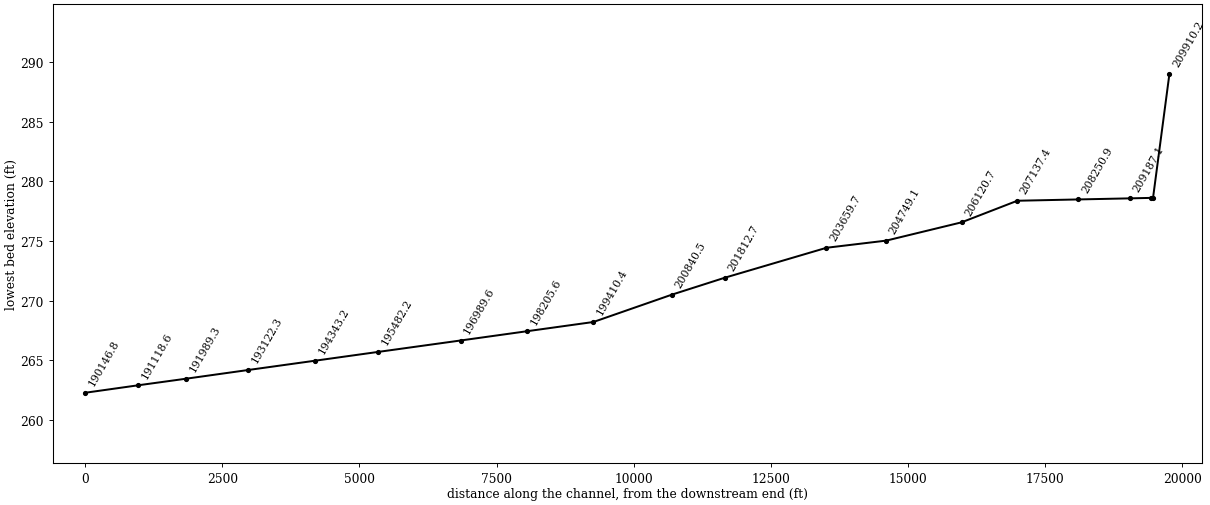
HEC-RAS study 020822_SANDY_CREEK.prj: Sandy Creek

--- 020822_SANDY_CREEK.g01 (geometry) --- (continued)

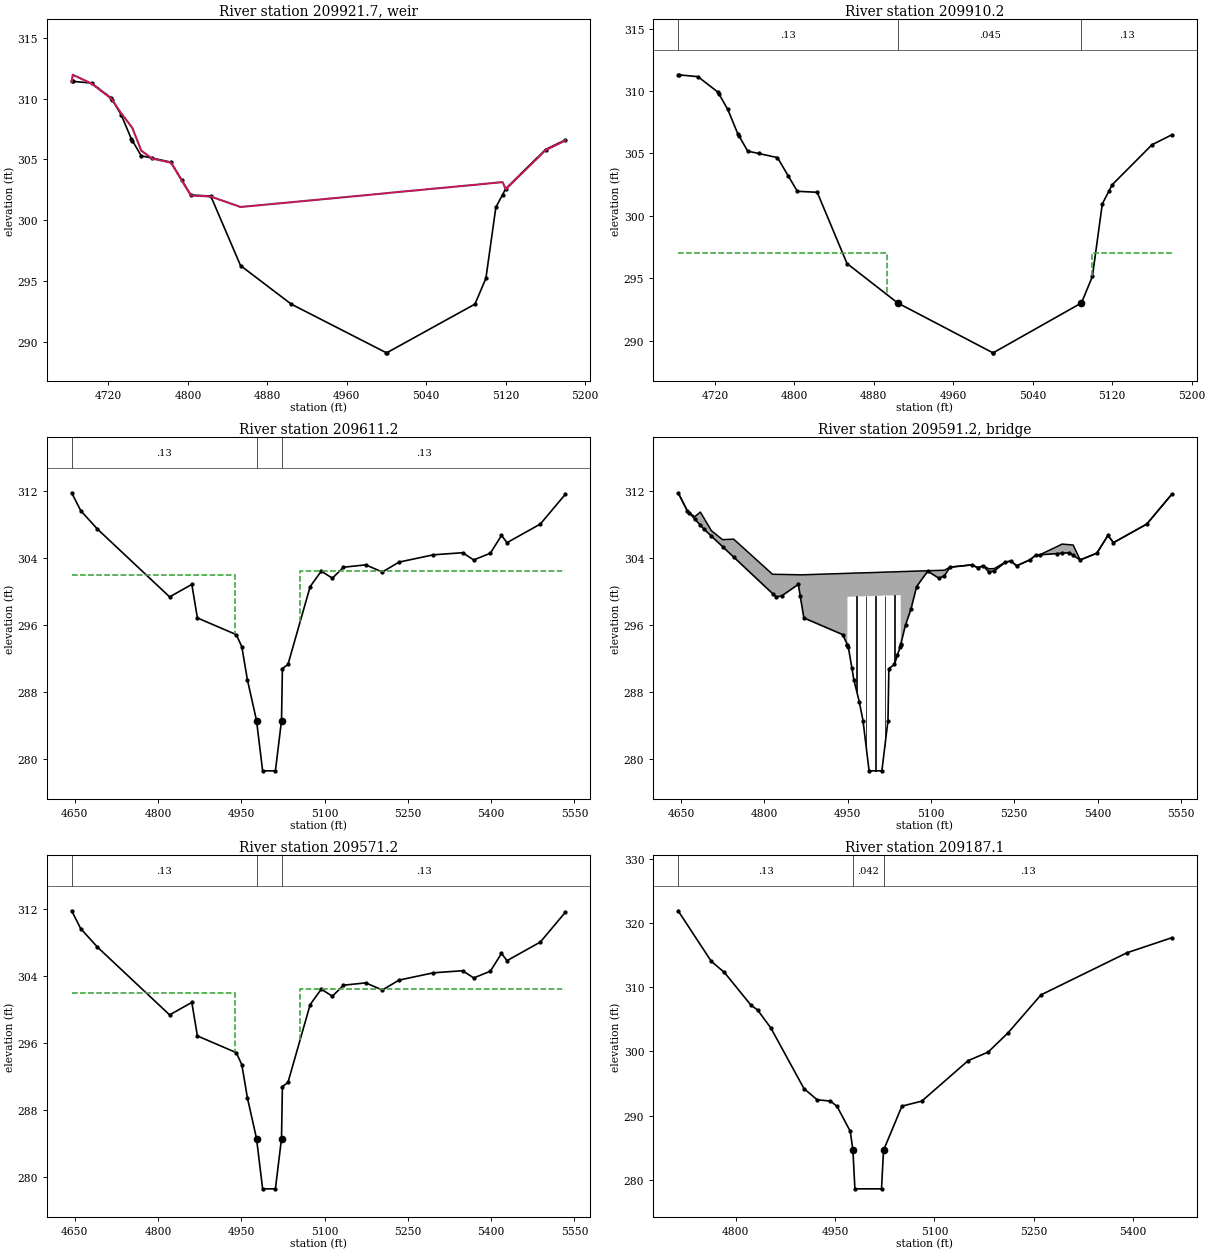
Type RM Length L Ch R = 5 ,209921.7,,,
BEGIN DESCRIPTION:
Dam_Southerland Mill Rd_2
Structure ID: Dam_Southerland Mill Rd
Approximate Survey Structure
END DESCRIPTION:
#Inline Weir SE= 25
    4683  311.37  4684.1  311.95    4703  311.23    4723  309.99  4724.1  309.84
    4733  308.77    4743  307.71  4744.1  307.59    4753  305.73  4764.1  305.07
    4783  304.74  4794.1  303.24    4803  302.04    4823  301.96    4853   301.1
    4904  301.49  4999.9  302.23  5000.1  302.24    5089  302.92    5100  303.01
    5110  303.09  5116.8  303.14    5120  302.56    5160  305.76    5180  306.56
IW Dist,WD,Coef,Skew,MaxSub,Min_El,Is_Ogee,SpillHt,DesHd
10.0,3.0,3.0,,0.95,, 0 ,,,2.0,2.0,

Type RM Length L Ch R = 1 ,209910.2,299,299,299
BEGIN DESCRIPTION:
Downstream Section of Bridge/Culvert/Weir
END DESCRIPTION:
#Sta/Elev= 25
    4683  311.31  4684.1   311.3    4703  311.16    4723  309.92  4724.1  309.77
    4733  308.53    4743  306.59  4744.1  306.44    4753  305.19  4764.1     305
    4783  304.67  4794.1  303.17    4803  301.97    4823  301.89    4853  296.18
    4904  293.02  4999.9  289.02  5000.1  289.02    5089  293.02    5100  295.14
    5110  300.96  5116.8  302.01    5120   302.5    5160   305.7    5180   306.5
#Mann= 3 , 1 , 0
 4683.00    0.13       0    4904   0.045       0    5089    0.13       0
#XS Ineff= 2 , 0
       0    4893     297    5100       0     297
Bank Sta=4904.00,5089.00
Exp/Cntr=0.5,0.3

Type RM Length L Ch R = 1 ,209611.2,40,40,40
BEGIN DESCRIPTION:
Upstream Section of Bridge/Culvert/Weir
END DESCRIPTION:
#Sta/Elev= 30
  4644.6  311.79    4661  309.65    4691  307.46    4821  299.37    4861  300.86
    4871  296.86    4941  294.87    4951  293.43    4961   289.5  4977.5  284.62
  4988.5  278.62  5011.5  278.62  5022.5  284.62  5024.1  290.82  5034.1  291.31
  5074.1   300.6  5094.1  302.44  5114.1   301.6  5134.1  302.91  5174.1  303.19
  5204.1  302.34  5234.1  303.52    5296  304.39  5348.6  304.64  5368.6  303.78
  5398.6  304.58  5418.6   306.7  5428.6  305.84  5488.6  308.06  5533.7  311.62
#Mann= 3 , 1 , 0
 4644.60    0.13       0  4977.5   0.045       0  5022.5    0.13       0
#XS Ineff= 2 , 0
       0    4938  301.99    5056       0   302.4
Bank Sta=4977.50,5022.50
Exp/Cntr=0.5,0.3

Type RM Length L Ch R = 3 ,209591.2,,,
BEGIN DESCRIPTION:
Southerland Mill Rd-TOR
Structure ID: Southerland Mill Rd
Approximate Survey Structure
END DESCRIPTION:
Bridge Culvert--1,0,-1,-1, 0
Deck Dist Width WeirC Skew NumUp NumDn MinLoCord MaxHiCord MaxSubmerge Is_Ogee
10,20,2.6,,60,60,,,0.95,0,1,1,,
  4644.6    4661  4664.6  4674.6  4684.6    4691  4704.6  4724.6  4744.6  4814.6
    4821    4831    4861  4864.6    4871    4941 4949.41  4949.5    4951  4957.5
    4961    4971  4977.5  4988.5  5011.5  5022.5  5024.1  5034.1  5039.5  5044.1
 5045.39  5045.5  5054.1  5064.1  5074.1  5094.1  5114.1  5124.1  5134.1  5174.1
  5184.1  5194.1  5204.1  5214.1  5234.1  5244.1  5254.1  5278.6  5288.6    5296
    5326    5336  5348.6    5356  5368.6  5398.6  5418.6  5428.6  5488.6  5533.7
  311.79  309.66   309.4  308.94  309.49  308.78  307.26   306.2  306.26  302.07
  302.06  302.05  302.01     302  302.01  302.16  302.18  302.18  302.18   302.2
  302.21  302.23  302.24  302.26  302.31  302.34  302.34  302.36  302.37  302.38
  302.39  302.39   302.4  302.43  302.45  302.49  302.53  302.55  302.92   303.2
  302.85  303.08  302.72  302.75  303.53  303.65  303.08  303.81  304.36   304.4
  305.34  305.67   305.6  305.56  303.78  304.58   306.7  305.84  308.06  311.62
  311.79  309.65  309.39  308.66  307.93  307.46  306.61  305.37  304.12  299.77
  299.37  299.48  300.86  299.42  296.86  294.87  293.66  299.38  299.38   299.4
  299.41  299.43  299.44  299.46  299.51  299.54  299.54  299.56  299.57  299.58
  299.59  293.72  296.02  297.95   300.6  302.44   301.6  301.88  302.91  303.19
  302.84  303.07  302.34  302.47  303.52  303.64  303.07   303.8  304.35  304.39
  304.53  304.58  304.64  304.32  303.78  304.58   306.7  305.84  308.06  311.62
  4644.6    4661  4664.6  4674.6  4684.6    4691  4704.6  4724.6  4744.6  4814.6
    4821    4831    4861  4864.6    4871    4941 4949.41  4949.5    4951  4957.5
    4961    4971  4977.5  4988.5  5011.5  5022.5  5024.1  5034.1  5039.5  5044.1
 5045.39  5045.5  5054.1  5064.1  5074.1  5094.1  5114.1  5124.1  5134.1  5174.1
  5184.1  5194.1  5204.1  5214.1  5234.1  5244.1  5254.1  5278.6  5288.6    5296
    5326    5336  5348.6    5356  5368.6  5398.6  5418.6  5428.6  5488.6  5533.7
  311.79  309.66   309.4  308.94  309.49  308.78  307.26   306.2  306.26  302.07
  302.06  302.05  302.01     302  302.01  302.16  302.18  302.18  302.18   302.2
  302.21  302.23  302.24  302.26  302.31  302.34  302.34  302.36  302.37  302.38
  302.39  302.39   302.4  302.43  302.45  302.49  302.53  302.55  302.92   303.2
  302.85  303.08  302.72  302.75  303.53  303.65  303.08  303.81  304.36   304.4
  305.34  305.67   305.6  305.56  303.78  304.58   306.7  305.84  308.06  311.62
  311.79  309.65  309.39  308.66  307.93  307.46  306.61  305.37  304.12  299.77
  299.37  299.48  300.86  299.42  296.86  294.87  293.66  299.38  299.38   299.4
  299.41  299.43  299.44  299.46  299.51  299.54  299.54  299.56  299.57  299.58
  299.59  293.72  296.02  297.95   300.6  302.44   301.6  301.88  302.91  303.19
  302.84  303.07  302.34  302.47  303.52  303.64  303.07   303.8  304.35  304.39
  304.53  304.58  304.64  304.32  303.78  304.58   306.7  305.84  308.06  311.62
Pier Skew, UpSta & Num, DnSta & Num=,4966.0, 2 ,4966.0, 2 , 0 , 0 , 0 ,,
     1.5     1.5
  286.95  300.42
     1.5     1.5
  286.95  300.42
Pier Skew, UpSta & Num, DnSta & Num=,4983.0, 2 ,4983.0, 2 , 0 , 0 , 0 ,,
     1.5     1.5
  280.21  300.45
     1.5     1.5
  280.21  300.45
Pier Skew, UpSta & Num, DnSta & Num=,5000.0, 2 ,5000.0, 2 , 0 , 0 , 0 ,,
     1.5     1.5
  277.62  300.49
     1.5     1.5
  277.62  300.49
Pier Skew, UpSta & Num, DnSta & Num=,5017.0, 2 ,5017.0, 2 , 0 , 0 , 0 ,,
     1.5     1.5
  280.21  300.53
     1.5     1.5
  280.21  300.53
Pier Skew, UpSta & Num, DnSta & Num=,5034.0, 2 ,5034.0, 2 , 0 , 0 , 0 ,,
     1.5     1.5
  290.27  300.56
     1.5     1.5
  290.27  300.56
Abutment Skew #Up #Dn=, 2 , 2
 4949.30 4957.50
  299.38  290.88
 4949.30 4957.50
  299.38  290.88
Abutment Skew #Up #Dn=, 2 , 2
 5039.50 5045.59
  292.41  299.59
 5039.50 5045.59
  292.41  299.59
BR Coef= 1 , 1 , 0 ,1.25, 0 ,,,0.8,0,2,0,
Wspro=,,,, 1 ,,,, 0 ,,,, 0 ,,,,-1 ,-1 ,-1 , 0 , 0 , 0 , 0 , 0
BC Design=,, 0 ,, 0 ,,,,,,
BR U #Sta/Elev= 60
  4644.6  311.79    4661  309.65  4664.6  309.39  4674.6  308.66  4684.6  307.93
    4691  307.46  4704.6  306.61  4724.6  305.37  4744.6  304.12  4814.6  299.77
    4821  299.37    4831  299.48    4861  300.86  4864.6  299.42    4871  296.86
    4941  294.87 4949.41  293.66  4949.5  293.65    4951  293.43  4957.5  290.88
    4961   289.5    4971   286.8  4977.5  284.62  4988.5  278.62  5011.5  278.62
  5022.5  284.62  5024.1  290.82  5034.1  291.31  5039.5  292.41  5044.1  293.35
 5045.39  293.69  5045.5  293.72  5054.1  296.02  5064.1  297.95  5074.1   300.6
  5094.1  302.44  5114.1   301.6  5124.1  301.88  5134.1  302.91  5174.1  303.19
  5184.1  302.84  5194.1  303.07  5204.1  302.34  5214.1  302.47  5234.1  303.52
  5244.1  303.64  5254.1  303.07  5278.6   303.8  5288.6  304.35    5296  304.39
    5326  304.53    5336  304.58  5348.6  304.64    5356  304.32  5368.6  303.78
  5398.6  304.58  5418.6   306.7  5428.6  305.84  5488.6  308.06  5533.7  311.62
BR U #Mann= 3
 4644.60    0.13  4977.5   0.045  5022.5    0.13
BR U Banks=4977.50,5022.50
BR D #Sta/Elev= 60
  4644.6  311.79    4661  309.65  4664.6  309.39  4674.6  308.66  4684.6  307.93
    4691  307.46  4704.6  306.61  4724.6  305.37  4744.6  304.12  4814.6  299.77
    4821  299.37    4831  299.48    4861  300.86  4864.6  299.42    4871  296.86
    4941  294.87 4949.41  293.66  4949.5  293.65    4951  293.43  4957.5  290.88
    4961   289.5    4971   286.8  4977.5  284.62  4988.5  278.62  5011.5  278.62
  5022.5  284.62  5024.1  290.82  5034.1  291.31  5039.5  292.41  5044.1  293.35
 5045.39  293.69  5045.5  293.72  5054.1  296.02  5064.1  297.95  5074.1   300.6
  5094.1  302.44  5114.1   301.6  5124.1  301.88  5134.1  302.91  5174.1  303.19
  5184.1  302.84  5194.1  303.07  5204.1  302.34  5214.1  302.47  5234.1  303.52
  5244.1  303.64  5254.1  303.07  5278.6   303.8  5288.6  304.35    5296  304.39
    5326  304.53    5336  304.58  5348.6  304.64    5356  304.32  5368.6  303.78
  5398.6  304.58  5418.6   306.7  5428.6  305.84  5488.6  308.06  5533.7  311.62
BR D #Mann= 3
 4644.60    0.13  4977.5   0.045  5022.5    0.13
BR D Banks=4977.50,5022.50

Type RM Length L Ch R = 1 ,209571.2,384.1,384.1,384.1
BEGIN DESCRIPTION:
Downstream Section of Bridge/Culvert/Weir
END DESCRIPTION:
#Sta/Elev= 30
  4644.6  311.79    4661  309.65    4691  307.46    4821  299.37    4861  300.86
    4871  296.86    4941  294.87    4951  293.43    4961   289.5  4977.5  284.62
  4988.5  278.62  5011.5  278.62  5022.5  284.62  5024.1  290.82  5034.1  291.31
  5074.1   300.6  5094.1  302.44  5114.1   301.6  5134.1  302.91  5174.1  303.19
  5204.1  302.34  5234.1  303.52    5296  304.39  5348.6  304.64  5368.6  303.78
  5398.6  304.58  5418.6   306.7  5428.6  305.84  5488.6  308.06  5533.7  311.62
#Mann= 3 , 1 , 0
 4644.60    0.13       0  4977.5   0.045       0  5022.5    0.13       0
#XS Ineff= 2 , 0
       0    4938  301.99    5056       0   302.4
Bank Sta=4977.50,5022.50
Exp/Cntr=0.5,0.3

Type RM Length L Ch R = 1 ,209187.1,936.2,936.2,936.2
BEGIN DESCRIPTION:
Sandy Creek 209.0
END DESCRIPTION:
#Sta/Elev= 23
  4712.9  321.92  4762.9  314.05  4782.9   312.3  4822.9  307.21  4832.9  306.46
  4852.9  303.66  4902.9  294.21  4922.9  292.46  4942.9  292.26  4952.9  291.44
  4972.9  287.54  4976.9  284.58  4979.9  278.58  5020.1  278.58  5023.1  284.58
  5050.9  291.47  5080.9  292.25  5150.9  298.56  5180.9  299.88  5210.9  302.86
  5260.9  308.81  5390.9  315.38  5458.6  317.72
#Mann= 3 , 1 , 0
 4712.90    0.13       0  4976.9   0.042       0  5023.1    0.13       0
Bank Sta=4976.90,5023.10
Exp/Cntr=0.3,0.1

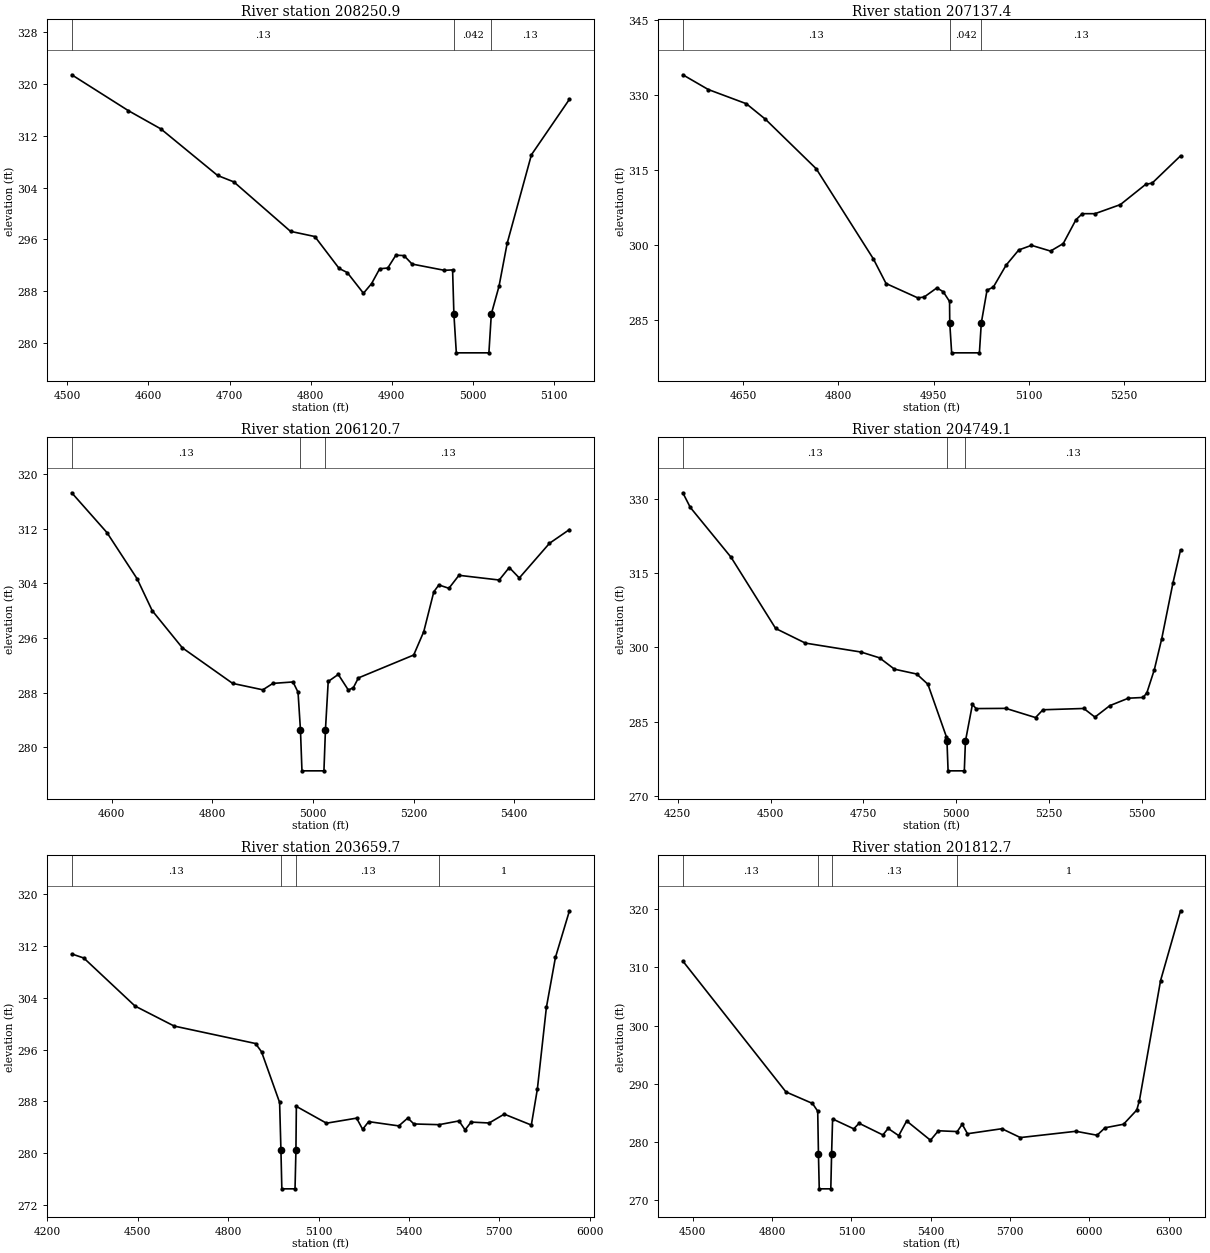
Type RM Length L Ch R = 1 ,208250.9,1113.5,1113.5,1113.5
BEGIN DESCRIPTION:
Sandy Creek 208.0
END DESCRIPTION:
#Sta/Elev= 26
  4505.3  321.43  4575.3  315.88  4615.3  313.07  4685.3  305.88  4705.3  304.89
  4775.3  297.25  4805.3  296.45  4835.3  291.52  4845.3  290.89  4865.3  287.69
  4875.3  289.18  4885.3  291.47  4895.3  291.59  4905.3  293.57  4915.3  293.51
  4925.3   292.2  4965.3  291.23  4975.3   291.3  4976.9  284.49  4979.9  278.49
  5020.1  278.49  5023.1  284.49  5032.6  288.78  5042.6  295.38  5072.6  309.08
  5119.5  317.65
#Mann= 3 , 1 , 0
 4505.30    0.13       0  4976.9   0.042       0  5023.1    0.13       0
Bank Sta=4976.90,5023.10
Exp/Cntr=0.3,0.1

Type RM Length L Ch R = 1 ,207137.4,1016.7,1016.7,1016.7
BEGIN DESCRIPTION:
Sandy Creek 207.0
END DESCRIPTION:
#Sta/Elev= 30
  4554.9  334.09  4594.9  331.14  4654.9  328.29  4684.9  325.19  4764.9  315.27
  4854.9  297.21  4874.9  292.27  4924.9  289.39  4934.9  289.56  4954.9  291.39
  4964.9  290.63  4974.9  288.67  4975.2  284.38  4978.2  278.38  5021.9  278.38
  5024.9  284.38  5033.9  290.93  5043.9  291.56  5063.9  295.94  5083.9  298.99
  5103.9  299.92  5133.9  298.77  5153.9  300.27  5173.9  305.04  5183.9  306.26
  5203.9  306.26  5243.9  308.08  5283.9  312.15  5293.9  312.38  5338.6  317.85
#Mann= 3 , 1 , 0
 4554.90    0.13       0  4975.2   0.042       0  5024.9    0.13       0
Bank Sta=4975.20,5024.90
Exp/Cntr=0.3,0.1

Type RM Length L Ch R = 1 ,206120.7,1371.6,1371.6,1371.6
BEGIN DESCRIPTION:
Sandy Creek 206.0
END DESCRIPTION:
#Sta/Elev= 30
  4520.3  317.24  4590.3  311.42  4650.3  304.66  4680.3     300  4740.3  294.56
  4840.3  289.36  4900.3  288.42  4920.3  289.36  4960.3  289.57  4970.3  288.07
  4975.1  282.57  4978.1  276.57  5021.8  276.57  5024.8  282.57  5030.3  289.64
  5050.3  290.67  5070.3  288.39  5080.3  288.73  5090.3  290.16  5200.3  293.51
  5220.3  296.93  5240.3  302.76  5250.3  303.76  5270.3  303.27  5290.3  305.17
  5370.3  304.48  5390.3  306.31  5410.3  304.78  5470.3  309.85    5510  311.86
#Mann= 3 , 1 , 0
 4520.30    0.13       0  4975.1   0.042       0  5024.8    0.13       0
Bank Sta=4975.10,5024.80
Exp/Cntr=0.3,0.1

Type RM Length L Ch R = 1 ,204749.1,1089.4,1089.4,1089.4
BEGIN DESCRIPTION:
Sandy Creek 205.0
END DESCRIPTION:
#Sta/Elev= 30
  4263.8  331.31  4283.8  328.36  4393.8  318.25  4513.8  303.85  4593.8  300.89
  4743.8  299.08  4793.8   297.9  4833.8  295.61  4893.8  294.63  4923.8  292.56
  4973.8  281.89  4975.2  281.04  4978.2  275.04  5021.9  275.04  5024.9  281.04
  5043.7  288.47  5053.7  287.64  5133.7  287.68  5213.7  285.82  5233.7   287.4
  5343.7  287.66  5373.7  285.91  5413.7  288.23  5463.7  289.74  5503.7  289.89
  5513.7  290.87  5533.7  295.53  5553.7  301.82  5583.7  313.03  5604.2  319.74
#Mann= 3 , 1 , 0
 4263.80    0.13       0  4975.2   0.042       0  5024.9    0.13       0
Bank Sta=4975.20,5024.90
Exp/Cntr=0.3,0.1

Type RM Length L Ch R = 1 ,203659.7,1847,1847,1847
BEGIN DESCRIPTION:
Sandy Creek 203.0
END DESCRIPTION:
#Sta/Elev= 30
  4280.7  310.79  4320.7  310.16  4490.7  302.73  4620.7  299.63  4890.7  296.93
  4910.7  295.65  4970.7  287.81  4975.1  280.44  4978.1  274.44  5021.9  274.44
  5024.9  280.44  5026.3   287.2  5126.3   284.6  5226.3  285.38  5246.3  283.65
  5266.3  284.84  5366.3  284.18  5396.3   285.4  5416.3  284.48  5499.9  284.37
  5566.3  284.95  5586.3  283.56  5606.3  284.77  5666.3  284.63  5716.3     286
  5806.3  284.31  5826.3  289.87  5856.3  302.52  5886.3  310.25  5932.8  317.47
#Mann= 4 , 1 , 0
 4280.70    0.13       0  4975.1   0.042       0  5024.9    0.13       0
  5499.9       1       0
Bank Sta=4975.10,5024.90
Exp/Cntr=0.3,0.1

Type RM Length L Ch R = 1 ,201812.7,972.2,972.2,972.2
BEGIN DESCRIPTION:
Sandy Creek 202.0
END DESCRIPTION:
#Sta/Elev= 30
  4462.4  311.08  4852.4  288.59  4952.4  286.62  4972.4  285.29  4975.2  277.94
  4978.2  271.94  5021.9  271.94  5024.9  277.94  5028.7  283.95  5108.7  282.25
  5128.7  283.21  5218.7   281.2  5238.7  282.32  5278.7  281.08  5308.7   283.6
  5398.7  280.29  5428.7  281.92  5499.9  281.78  5518.7  283.03  5538.7  281.41
  5668.7  282.27  5738.7  280.75  5948.7  281.83  6028.7  281.15  6058.7  282.43
  6128.7  283.04  6178.7  285.48  6188.7   287.1  6268.7  307.72  6344.2  319.72
#Mann= 4 , 1 , 0
 4462.40    0.13       0  4975.2   0.042       0  5024.9    0.13       0
  5499.9       1       0
Bank Sta=4975.20,5024.90
Exp/Cntr=0.3,0.1

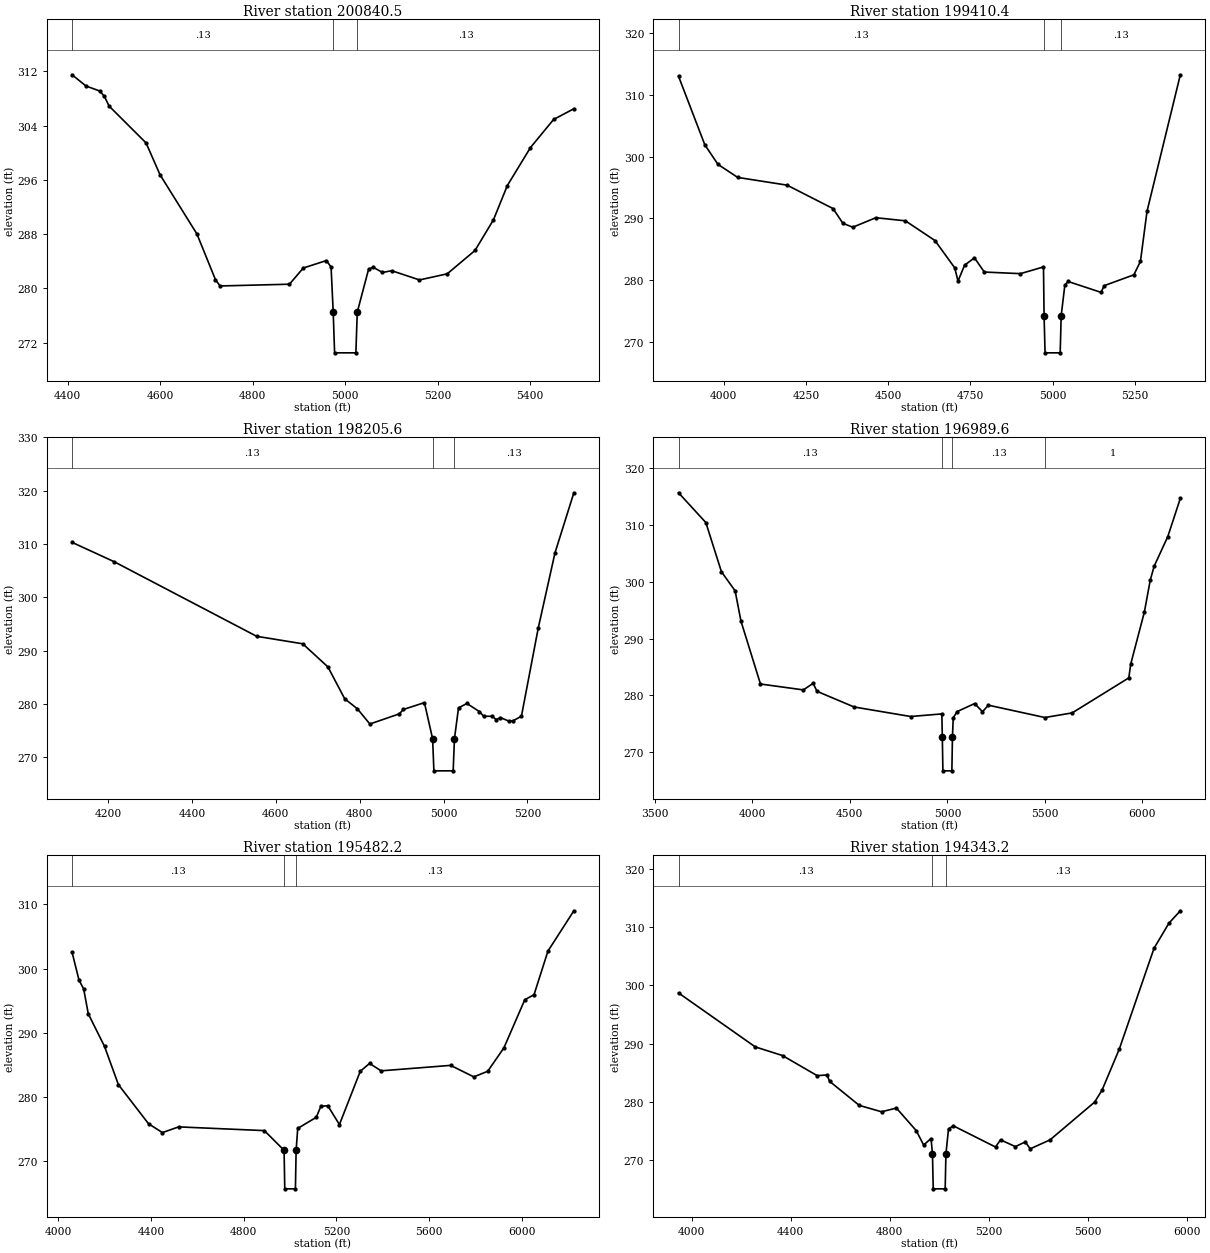
Type RM Length L Ch R = 1 ,200840.5,1430.1,1430.1,1430.1
BEGIN DESCRIPTION:
Sandy Creek 201.0
END DESCRIPTION:
#Sta/Elev= 30
  4409.4  311.51  4439.4  309.86  4469.4  309.11  4479.4  308.31  4489.4   306.9
  4569.4  301.46  4599.4  296.79  4679.4  288.03  4719.4   281.3  4729.4  280.37
  4879.4  280.63  4909.4  283.02  4959.4  284.12  4969.4  283.15    4974  276.51
    4977  270.51    5023  270.51    5026  276.51  5050.5  282.84  5060.5  283.13
  5080.5  282.36  5100.5  282.62  5160.5  281.26  5220.5  282.16  5280.5   285.6
  5320.5  290.13  5350.5  295.18  5400.5  300.78  5450.5  304.92  5494.3   306.5
#Mann= 3 , 1 , 0
 4409.40    0.13       0    4974   0.042       0    5026    0.13       0
Bank Sta=4974.00,5026.00
Exp/Cntr=0.3,0.1

Type RM Length L Ch R = 1 ,199410.4,1204.8,1204.8,1204.8
BEGIN DESCRIPTION:
Sandy Creek 199.0
END DESCRIPTION:
#Sta/Elev= 30
  3862.2  313.03  3942.2  301.92  3982.2  298.75  4042.2  296.64  4192.2  295.39
  4332.2  291.59  4362.2   289.2  4392.2  288.57  4462.2  290.11  4552.2  289.61
  4642.2  286.41  4702.2  281.99  4712.2  279.85  4732.2  282.41  4762.2  283.62
  4792.2  281.31  4902.2  281.05  4972.2  282.14    4974  274.22    4977  268.22
    5023  268.22    5026  274.22  5037.1  279.18  5047.1  279.78  5147.1  278.02
  5157.1  279.11  5247.1  280.86  5267.1  283.04  5287.1  291.15  5388.4  313.27
#Mann= 3 , 1 , 0
 3862.20    0.13       0    4974   0.042       0    5026    0.13       0
Bank Sta=4974.00,5026.00
Exp/Cntr=0.3,0.1

Type RM Length L Ch R = 1 ,198205.6,1216,1216,1216
BEGIN DESCRIPTION:
Sandy Creek 198.0
END DESCRIPTION:
#Sta/Elev= 28
  4114.4  310.29  4214.4  306.68  4554.4  292.68  4664.4  291.27  4724.4  286.93
  4764.4  280.96  4794.4   279.1  4824.4  276.23  4894.4  278.13  4904.4  278.96
  4954.4  280.24    4974  273.45    4977  267.45    5023  267.45    5026  273.45
  5035.7  279.26  5055.7  280.08  5085.7  278.55  5095.7  277.69  5115.7  277.68
  5125.7  277.06  5135.7  277.44  5155.7  276.77  5165.7  276.84  5185.7  277.68
  5225.7  294.19  5265.7  308.32  5310.7  319.59
#Mann= 3 , 1 , 0
 4114.40    0.13       0    4974   0.042       0    5026    0.13       0
Bank Sta=4974.00,5026.00
Exp/Cntr=0.3,0.1

Type RM Length L Ch R = 1 ,196989.6,1507.4,1507.4,1507.4
BEGIN DESCRIPTION:
Sandy Creek 197.0
END DESCRIPTION:
#Sta/Elev= 30
  3621.7   315.7  3761.7  310.45  3841.7  301.77  3911.7  298.42  3941.7  293.08
  4041.7  281.98  4261.7  280.94  4311.7   282.1  4331.7  280.69  4521.7  277.93
  4811.7  276.25  4971.7  276.71    4974  272.67    4977  266.67    5023  266.67
    5026  272.67    5030  276.02    5050  277.12    5140  278.54    5180  277.08
    5210  278.25  5499.9  276.07    5640  276.89    5930  283.06    5940  285.51
    6010  294.69    6040   300.3    6060  302.75    6130  307.98  6194.2  314.71
#Mann= 4 , 1 , 0
 3621.70    0.13       0    4974   0.042       0    5026    0.13       0
  5499.9       1       0
Bank Sta=4974.00,5026.00
Exp/Cntr=0.3,0.1

Type RM Length L Ch R = 1 ,195482.2,1139,1139,1139
BEGIN DESCRIPTION:
Sandy Creek 195.0
END DESCRIPTION:
#Sta/Elev= 30
  4058.9  302.56  4088.9  298.21  4108.9  296.85  4128.9  292.97  4198.9   287.9
  4258.9  281.94  4388.9  275.85  4448.9  274.47  4518.9  275.36  4888.9  274.78
    4974  271.71    4977  265.71    5023  265.71    5026  271.71  5032.9  275.12
  5112.9  276.85  5132.9  278.58  5162.9  278.65  5212.9  275.72  5302.9  284.02
  5342.9  285.24  5392.9  284.09  5692.9  284.94  5792.9  283.15  5852.9  284.02
  5922.9  287.67  6012.9  295.16  6052.9  295.95  6112.9  302.74  6224.8  309.02
#Mann= 3 , 1 , 0
 4058.90    0.13       0    4974   0.042       0    5026    0.13       0
Bank Sta=4974.00,5026.00
Exp/Cntr=0.3,0.1

Type RM Length L Ch R = 1 ,194343.2,1220.9,1220.9,1220.9
BEGIN DESCRIPTION:
Sandy Creek 194.0
END DESCRIPTION:
#Sta/Elev= 30
  3947.2  298.71  4257.2  289.42  4367.2  287.93  4507.2  284.47  4547.2  284.59
  4557.2   283.5  4677.2  279.35  4767.2  278.25  4827.2  278.89  4907.2  275.01
  4937.2  272.53  4967.2  273.64  4972.9  270.98  4975.9  264.98  5024.2  264.98
  5027.2  270.98  5037.7  275.31  5057.7  275.82  5227.7  272.18  5247.7  273.42
  5307.7  272.25  5347.7  273.06  5367.7  271.87  5447.7  273.41  5627.7  279.91
  5657.7  281.96  5727.7  289.07  5867.7  306.39  5927.7  310.71    5974  312.86
#Mann= 3 , 1 , 0
 3947.20    0.13       0  4972.9   0.042       0  5027.2    0.13       0
Bank Sta=4972.90,5027.20
Exp/Cntr=0.3,0.1

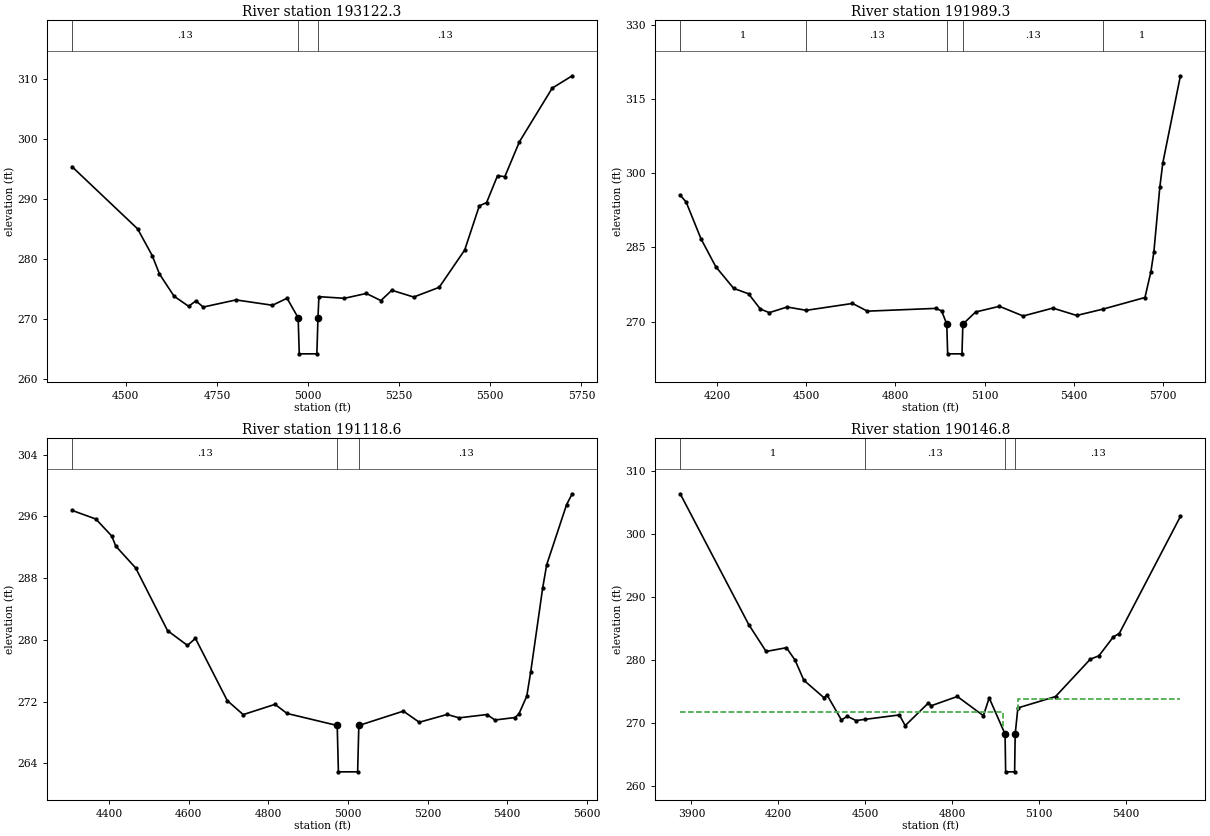
Type RM Length L Ch R = 1 ,193122.3,1133,1133,1133
BEGIN DESCRIPTION:
Sandy Creek 193.0
END DESCRIPTION:
#Sta/Elev= 30
  4352.3  295.41  4532.3  285.04  4572.3  280.59  4592.3  277.51  4632.3  273.81
  4672.3  272.13  4692.3  273.03  4712.3     272  4802.3  273.19  4902.3   272.3
  4942.3  273.47  4972.8   270.2  4975.8   264.2  5024.1   264.2  5027.1   270.2
  5029.7  273.73  5099.7  273.46  5159.7  274.27  5199.7  273.08  5229.7   274.8
  5289.7  273.67  5359.7  275.29  5429.7  281.52  5469.7  288.87  5489.7  289.42
  5519.7   293.9  5539.7  293.74  5579.7  299.55  5669.7   308.5  5724.6  310.56
#Mann= 3 , 1 , 0
 4352.30    0.13       0  4972.8   0.042       0  5027.1    0.13       0
Bank Sta=4972.80,5027.10
Exp/Cntr=0.3,0.1

Type RM Length L Ch R = 1 ,191989.3,870.7,870.7,870.7
BEGIN DESCRIPTION:
Sandy Creek 192.0
END DESCRIPTION:
#Sta/Elev= 30
  4075.6  295.55  4095.6  294.17  4145.6  286.73  4195.6  281.07  4255.6  276.71
  4305.6  275.61  4345.6  272.52  4375.6   271.8  4435.6  272.94  4499.9  272.27
  4655.6  273.66  4705.6   272.1  4935.6  272.66  4955.6  272.15  4972.9  269.47
  4975.9  263.47  5024.1  263.47  5027.1  269.47    5070  271.93    5150  273.08
    5230  271.12    5330  272.72    5410  271.23  5499.9  272.53    5640  274.86
    5660  280.08    5670  284.08    5690  297.16    5700  302.04  5759.3  319.69
#Mann= 5 , 1 , 0
 4075.60       1       0  4499.9    0.13       0  4972.9   0.042       0
  5027.1    0.13       0  5499.9       1       0
Bank Sta=4972.90,5027.10
Exp/Cntr=0.3,0.1

Type RM Length L Ch R = 1 ,191118.6,971.8,971.8,971.8
BEGIN DESCRIPTION:
Sandy Creek 191.0
END DESCRIPTION:
#Sta/Elev= 30
  4306.8  296.77  4366.8  295.65  4406.8  293.44  4416.8  292.14  4466.8  289.31
  4546.8   281.2  4596.8  279.29  4616.8   280.2  4696.8  272.14  4736.8  270.33
  4816.8  271.66  4846.8  270.48  4972.9  268.92  4975.9  262.92  5024.2  262.92
  5027.2  268.92    5139  270.78    5179  269.34    5249  270.35    5279  269.91
    5349  270.34    5369  269.63    5419  269.95    5429  270.39    5449  272.72
    5459   275.9    5489  286.75    5499  289.73    5549  297.52  5563.1  298.92
#Mann= 3 , 1 , 0
 4306.80    0.13       0  4972.9   0.042       0  5027.2    0.13       0
Bank Sta=4972.90,5027.20
Exp/Cntr=0.3,0.1

Type RM Length L Ch R = 1 ,190146.8,38,38,38
BEGIN DESCRIPTION:
Upstream Section of Bridge/Culvert/Weir
END DESCRIPTION:
#Sta/Elev= 30
    3861  306.46  4097.7  285.68  4157.7  281.41  4227.7  282.01  4257.7  280.03
  4287.7  276.85  4357.7  274.05  4367.7  274.52  4417.7  270.52  4437.7  271.12
  4467.7  270.44  4499.9  270.63  4617.7  271.33  4637.7  269.63  4717.7  273.22
  4727.7  272.79  4817.7  274.26  4907.7  271.21  4927.7  274.04  4982.5  268.29
  4984.5  262.29  5015.5  262.29  5017.5  268.29  5026.7  272.44  5156.7  274.25
  5276.7  280.18  5306.7  280.73  5356.7  283.75  5376.7  284.26  5587.8  302.86
#Mann= 4 , 1 , 0
 3861.00       1       0  4499.9    0.13       0  4982.5   0.042       0
  5017.5    0.13       0
#XS Ineff= 2 , 0
       0    4974  271.86    5026       0  273.84
Bank Sta=4982.50,5017.50
Exp/Cntr=0.5,0.3