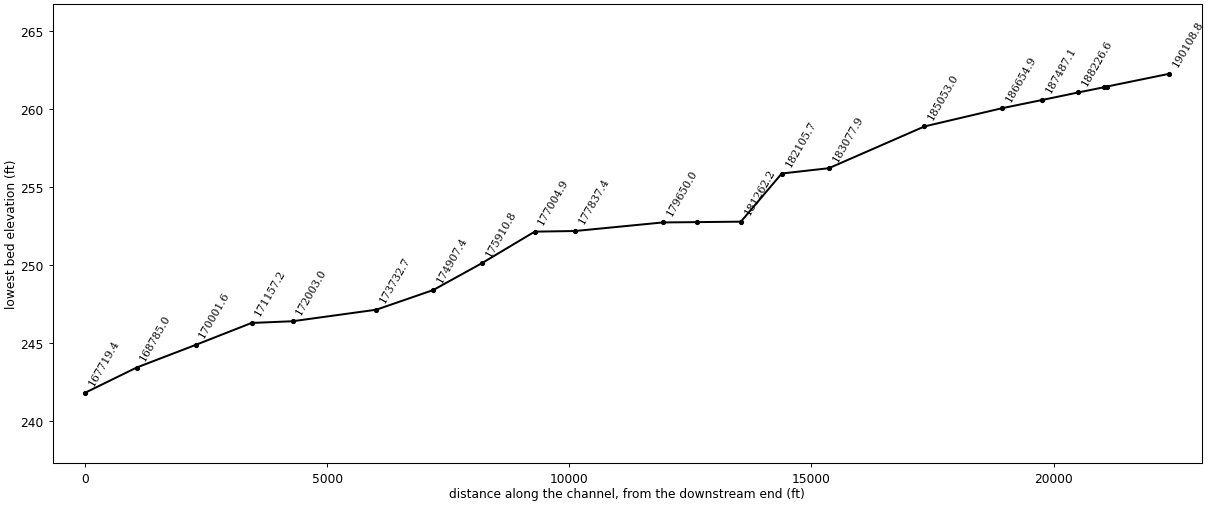
HEC-RAS study 020822_SANDY_CREEK.prj: Sandy Creek

--- 020822_SANDY_CREEK.g01 (geometry) --- (continued)

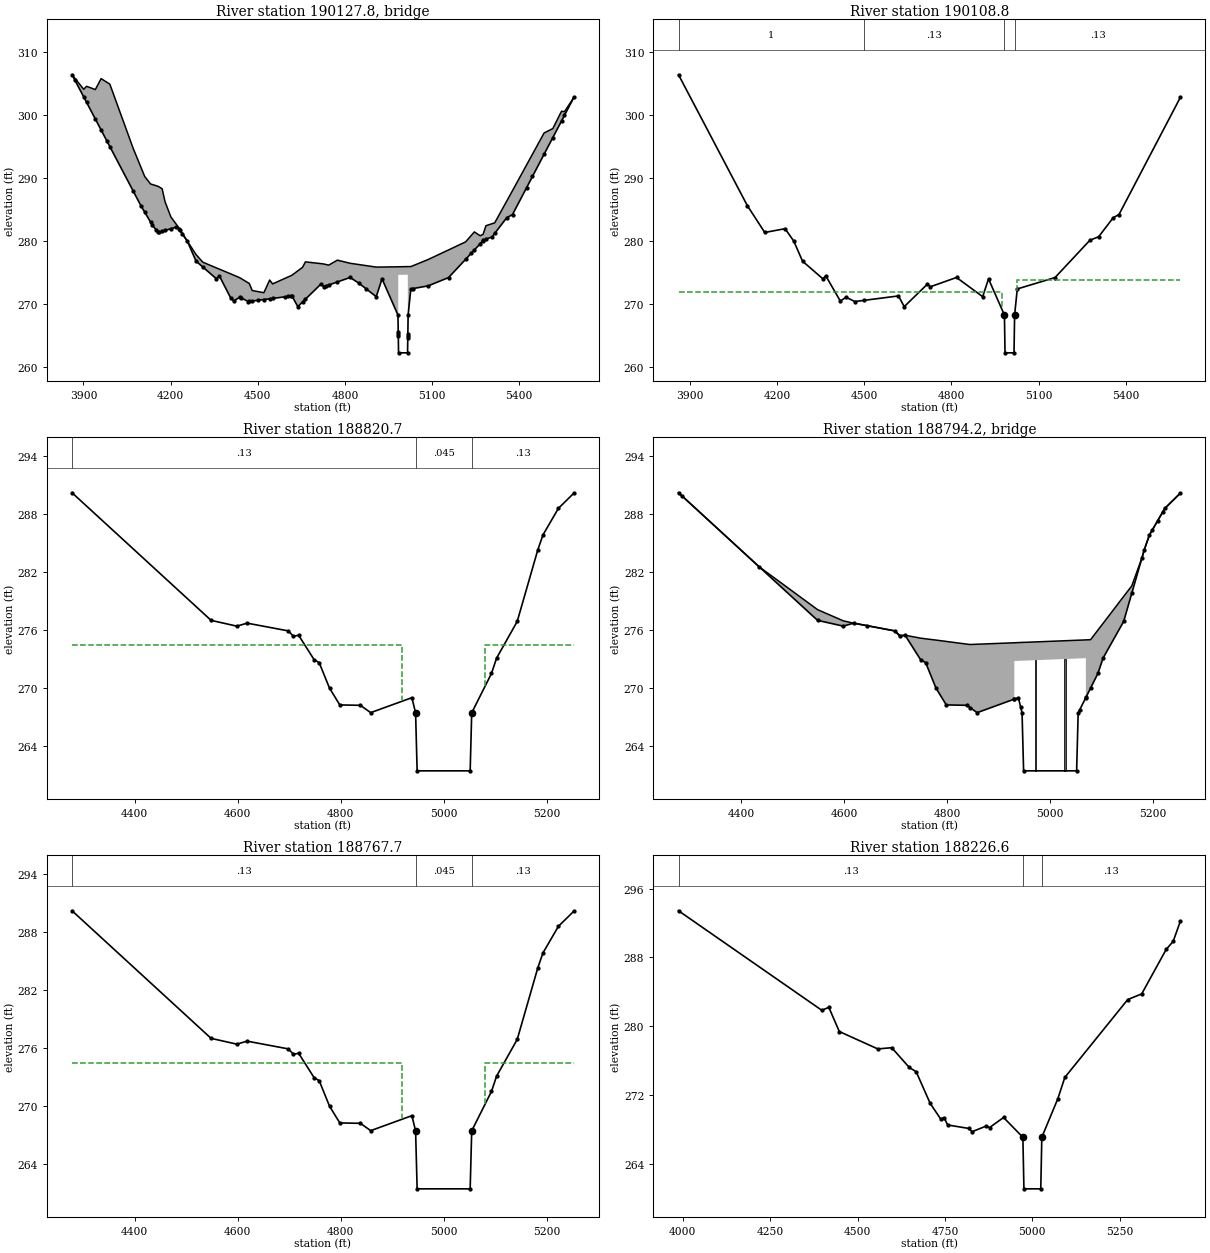
Type RM Length L Ch R = 3 ,190127.8,,,
BEGIN DESCRIPTION:
Hightower Rd-TOR
Structure ID: Hightower Rd-Bridge
Approximate Survey Structure
END DESCRIPTION:
Bridge Culvert--1,0,-1,-1, 0
Deck Dist Width WeirC Skew NumUp NumDn MinLoCord MaxHiCord MaxSubmerge Is_Ogee
10,18,2.6,, 60, 60,,,0.95,0,1,1,,
    3861    3901    3911    3941    3961    3991    4071    4111    4131  4157.7
    4171    4181    4201  4227.7  4257.7  4287.7    4311  4357.7  4367.7  4407.7
  4417.7  4437.7    4471    4481    4521    4541    4551  4617.7  4637.7    4654
    4664  4717.7  4727.7    4744    4774  4817.7  4907.7  4927.7  4982.5 4983.41
  4983.5 5016.39  5016.5  5017.5  5026.7  5086.7  5156.7  5215.4  5245.4  5265.4
  5275.4  5285.4  5315.4  5356.7  5376.7  5485.4  5515.4  5545.4  5555.4  5587.8
  306.46  304.16  304.63  304.11  305.85  304.97  294.81   290.3  289.12  288.73
  288.35  286.29  283.88  282.21  280.03   277.9  276.69  275.78  275.59  274.82
  274.62  274.23   273.3  272.19  271.84  273.86  273.24  274.62  275.31  275.87
  276.74  276.46   276.4  276.22  277.01  276.52  275.91  275.92  275.96  275.96
  275.96  275.99  275.99  275.99  275.99  277.12  278.64  279.92   281.5  280.89
  281.12  282.49  282.94  286.39  288.06  297.22  297.92  300.67  300.59  302.86
  306.46  302.95  302.07  299.44  297.68  295.05  288.02  284.64  283.07  281.41
  281.59  281.73  282.01  282.01  280.03  276.85  275.92  274.05  274.52  270.94
  270.52  271.12  270.46  270.52  270.76  270.87  270.93  271.33  269.63  270.36
  270.81  273.22  272.79  273.06  273.55  274.26  271.21  274.04  268.29  265.56
  274.67   274.7  265.29  268.29  272.44  272.93  274.25  277.15  278.63  279.62
  280.12  280.34  281.26  283.75  284.26  293.84  296.48  299.12  300.01  302.86
    3861    3901    3911    3941    3961    3991    4071    4111    4131  4157.7
    4171    4181    4201  4227.7  4257.7  4287.7    4311  4357.7  4367.7  4407.7
  4417.7  4437.7    4471    4481    4521    4541    4551  4617.7  4637.7    4654
    4664  4717.7  4727.7    4744    4774  4817.7  4907.7  4927.7  4982.5 4983.41
  4983.5 5016.39  5016.5  5017.5  5026.7  5086.7  5156.7  5215.4  5245.4  5265.4
  5275.4  5285.4  5315.4  5356.7  5376.7  5485.4  5515.4  5545.4  5555.4  5587.8
  306.45  304.16  304.63  304.11  305.85  304.97  294.81   290.3  289.12  288.73
  288.35  286.29  283.88  282.21  280.03   277.9  276.69  275.78  275.59  274.82
  274.62  274.23   273.3  272.19  271.84  273.86  273.24  274.62  275.31  275.87
  276.74  276.46   276.4  276.22  277.01  276.52  275.91  275.92  275.96  275.96
  275.96  275.99  275.99  275.99  275.99  277.12  278.64  279.92   281.5  280.89
  281.12  282.49  282.94  286.39  288.06  297.22  297.92  300.67  300.59  302.85
  306.45  302.94  302.06  299.43  297.67  295.04  288.01  284.63  283.06   281.4
  281.58  281.72     282     282  280.02  276.84  275.91  274.04  274.51  270.93
  270.51  271.11  270.45  270.51  270.75  270.86  270.92  271.32  269.62  270.35
   270.8  273.21  272.78  273.05  273.54  274.25   271.2  274.03  268.28  265.55
  274.66  274.69  265.28  268.28  272.43  272.92  274.24  277.14  278.62  279.61
  280.11  280.33  281.25  283.74  284.25  293.83  296.47  299.11     300  302.85
BR Coef= 1 , 1 , 0 ,1.25, 0 ,,,0.8,0,2,0,
Wspro=,,,, 1 ,,,, 0 ,,,, 0 ,,,,-1 ,-1 ,-1 , 0 , 0 , 0 , 0 , 0
BC Design=,, 0 ,, 0 ,,,,,,
BR U #Sta/Elev= 88
    3861  306.46    3871  305.58    3901  302.95    3911  302.07    3941  299.44
    3961  297.68    3981  295.93    3991  295.05    4071  288.02  4097.7  285.68
    4111  284.64    4131  283.07  4137.7  282.54    4151  281.79  4157.7  281.41
    4161  281.46    4171  281.59    4181  281.73    4201  282.01  4217.7  282.24
  4227.7  282.01    4231  281.79    4241  281.13  4257.7  280.03  4287.7  276.85
    4311  275.92  4357.7  274.05  4367.7  274.52  4407.7  270.94  4417.7  270.52
  4437.7  271.12    4441  271.05  4467.7  270.44    4471  270.46    4481  270.52
  4499.9  270.63    4521  270.76    4541  270.87    4551  270.93    4594  271.19
    4604  271.25    4614  271.31  4617.7  271.33  4637.7  269.63    4654  270.36
    4664  270.81  4717.7  273.22  4727.7  272.79    4734  272.89    4744  273.06
    4774  273.55  4817.7  274.26  4847.7  273.37    4874  272.42  4907.7  271.21
  4927.7  274.04  4982.5  268.29 4983.41  265.56  4983.5  265.29  4983.6  264.99
  4984.5  262.29  5015.5  262.29  5016.3  264.69 5016.39  264.96  5016.5  265.29
  5017.5  268.29  5026.7  272.44  5035.4  272.51  5086.7  272.93  5156.7  274.25
  5215.4  277.15  5235.4  278.14  5245.4  278.63  5265.4  279.62  5275.4  280.12
  5276.7  280.18  5285.4  280.34  5306.7  280.73  5315.4  281.26  5356.7  283.75
  5376.7  284.26  5425.4  288.55  5445.4  290.31  5485.4  293.84  5515.4  296.48
  5545.4  299.12  5555.4  300.01  5587.8  302.86
BR U #Mann= 4
 3861.00       1  4499.9    0.13  4982.5   0.042  5017.5    0.13
BR U Banks=4982.50,5017.50
BR D #Sta/Elev= 88
    3861  306.45    3871  305.57    3901  302.94    3911  302.06    3941  299.43
    3961  297.67    3981  295.92    3991  295.04    4071  288.01  4097.7  285.67
    4111  284.63    4131  283.06  4137.7  282.53    4151  281.78  4157.7   281.4
    4161  281.45    4171  281.58    4181  281.72    4201     282  4217.7  282.23
  4227.7     282    4231  281.78    4241  281.12  4257.7  280.02  4287.7  276.84
    4311  275.91  4357.7  274.04  4367.7  274.51  4407.7  270.93  4417.7  270.51
  4437.7  271.11    4441  271.04  4467.7  270.43    4471  270.45    4481  270.51
  4499.9  270.62    4521  270.75    4541  270.86    4551  270.92    4594  271.18
    4604  271.24    4614   271.3  4617.7  271.32  4637.7  269.62    4654  270.35
    4664   270.8  4717.7  273.21  4727.7  272.78    4734  272.88    4744  273.05
    4774  273.54  4817.7  274.25  4847.7  273.36    4874  272.41  4907.7   271.2
  4927.7  274.03  4982.5  268.28 4983.41  265.55  4983.5  265.28  4983.6  264.98
  4984.5  262.28  5015.5  262.28  5016.3  264.68 5016.39  264.95  5016.5  265.28
  5017.5  268.28  5026.7  272.43  5035.4   272.5  5086.7  272.92  5156.7  274.24
  5215.4  277.14  5235.4  278.13  5245.4  278.62  5265.4  279.61  5275.4  280.11
  5276.7  280.17  5285.4  280.33  5306.7  280.72  5315.4  281.25  5356.7  283.74
  5376.7  284.25  5425.4  288.54  5445.4   290.3  5485.4  293.83  5515.4  296.47
  5545.4  299.11  5555.4     300  5587.8  302.85
BR D #Mann= 4
 3861.00       1  4499.9    0.13  4982.5   0.042  5017.5    0.13
BR D Banks=4982.50,5017.50

Type RM Length L Ch R = 1 ,190108.8,1288.1,1288.1,1288.1
BEGIN DESCRIPTION:
Downstream Section of Bridge/Culvert/Weir
END DESCRIPTION:
#Sta/Elev= 30
    3861  306.44  4097.7  285.66  4157.7  281.39  4227.7  281.99  4257.7  280.01
  4287.7  276.83  4357.7  274.03  4367.7   274.5  4417.7   270.5  4437.7   271.1
  4467.7  270.42  4499.9  270.61  4617.7  271.31  4637.7  269.61  4717.7   273.2
  4727.7  272.77  4817.7  274.24  4907.7  271.19  4927.7  274.02  4982.5  268.27
  4984.5  262.27  5015.5  262.27  5017.5  268.27  5026.7  272.42  5156.7  274.23
  5276.7  280.16  5306.7  280.71  5356.7  283.73  5376.7  284.24  5587.8  302.84
#Mann= 4 , 1 , 0
 3861.00       1       0  4499.9    0.13       0  4982.5   0.042       0
  5017.5    0.13       0
#XS Ineff= 2 , 0
       0    4974  271.86    5026       0  273.84
Bank Sta=4982.50,5017.50
Exp/Cntr=0.5,0.3

Type RM Length L Ch R = 1 ,188820.7,53,53,53
BEGIN DESCRIPTION:
Upstream Section of Bridge/Culvert/Weir
END DESCRIPTION:
#Sta/Elev= 25
  4278.3  290.22  4548.3  277.02  4598.3  276.42  4618.3  276.73  4698.3  275.93
  4708.3  275.37  4718.3  275.48  4748.3  272.96  4758.3  272.64  4778.3  270.01
  4798.3  268.27  4838.3  268.23  4858.3  267.47  4938.3  269.02  4945.5  267.45
  4948.5  261.45  5051.5  261.45  5054.5  267.45  5092.9  271.53  5102.9  273.12
  5142.9  276.91  5182.9  284.32  5192.9  285.86  5222.9  288.61  5252.9  290.18
#Mann= 3 , 1 , 0
 4278.30    0.13       0  4945.5   0.045       0  5054.5    0.13       0
#XS Ineff= 2 , 0
       0    4920  274.48    5081       0  274.48
Bank Sta=4945.50,5054.50
Exp/Cntr=0.5,0.3

Type RM Length L Ch R = 3 ,188794.2,,,
BEGIN DESCRIPTION:
US 401-4-TOR
Structure ID: US 401_sandy-Bridge
Approximate Survey Structure
END DESCRIPTION:
Bridge Culvert--1,0,-1,-1, 0
Deck Dist Width WeirC Skew NumUp NumDn MinLoCord MaxHiCord MaxSubmerge Is_Ogee
10,33,2.6,,41,41,,,0.95,0,1,1,,
  4278.3  4284.5  4434.5  4548.3  4598.3  4618.3  4644.5  4698.3  4708.3  4718.3
  4748.3  4758.3  4778.3  4798.3  4838.3  4844.5  4858.3 4930.41  4930.5  4938.3
  4942.5  4945.5  4948.5  5051.5  5054.5  5057.5 5069.39  5069.5  5078.6  5092.9
  5102.9  5142.9  5158.6  5178.6  5182.9  5192.9  5198.6  5208.6  5218.6  5222.9
  5252.9
  290.21  289.91  282.57  278.12  276.96  276.72  276.46  275.92  275.45  275.47
  275.17   275.1  274.97  274.83  274.55  274.51  274.54  274.69  274.69  274.71
  274.72  274.73  274.73  274.95  274.96  274.96  274.99  274.99  275.01  276.01
   276.7  279.49  280.58  283.51  284.31  285.85  286.37  287.29  288.21   288.6
  290.17
  290.21  289.91  282.57  277.01  276.41  276.72  276.46  275.92  275.36  275.47
  272.95  272.63     270  268.26  268.22  267.98  267.46  268.86   272.8  272.82
  272.83  272.84  272.84  273.06  273.07  273.07   273.1  269.03     270  271.52
  273.11   276.9  279.81  283.51  284.31  285.85  286.37  287.29  288.21   288.6
  290.17
  4278.3  4284.5  4434.5  4548.3  4598.3  4618.3  4644.5  4698.3  4708.3  4718.3
  4748.3  4758.3  4778.3  4798.3  4838.3  4844.5  4858.3 4930.41  4930.5  4938.3
  4942.5  4945.5  4948.5  5051.5  5054.5  5057.5 5069.39  5069.5  5078.6  5092.9
  5102.9  5142.9  5158.6  5178.6  5182.9  5192.9  5198.6  5208.6  5218.6  5222.9
  5252.9
   290.2  289.91  282.57  278.12  276.96  276.72  276.46  275.92  275.45  275.47
  275.17   275.1  274.97  274.83  274.55  274.51  274.54  274.69  274.69  274.71
  274.72  274.73  274.73  274.95  274.96  274.96  274.99  274.99  275.01  276.01
   276.7  279.49  280.58  283.51  284.31  285.85  286.37  287.29  288.21  288.59
  290.16
  290.19  289.89  282.55  276.99  276.39   276.7  276.44   275.9  275.34  275.45
  272.93  272.61  269.98  268.24   268.2  267.96  267.44  268.84  272.78   272.8
  272.81  272.82  272.82  273.04  273.05  273.05  273.08  269.01  269.98   271.5
  273.09  276.88  279.79  283.49  284.29  285.83  286.35  287.27  288.19  288.58
  290.15
Pier Skew, UpSta & Num, DnSta & Num=,4971.3, 2 ,4971.3, 2 , 0 , 0 , 0 ,,
       3       3
  260.44  273.89
       3       3
  260.42  273.87
Pier Skew, UpSta & Num, DnSta & Num=,5028.8, 2 ,5028.8, 2 , 0 , 0 , 0 ,,
       3       3
  260.44  274.01
       3       3
  260.42  273.99
Abutment Skew #Up #Dn=, 2 , 2
 4930.30 4942.50
  272.80  268.09
 4930.30 4942.50
  272.78  268.07
Abutment Skew #Up #Dn=, 2 , 2
 5057.50 5069.59
  267.76  273.10
 5057.50 5069.59
  267.74  273.08
BR Coef= 1 , 1 , 0 ,1.25, 0 ,,,0.8,0,2,0,
Wspro=,,,, 1 ,,,, 0 ,,,, 0 ,,,,-1 ,-1 ,-1 , 0 , 0 , 0 , 0 , 0
BC Design=,, 0 ,, 0 ,,,,,,
BR U #Sta/Elev= 41
  4278.3  290.21  4284.5  289.91  4434.5  282.57  4548.3  277.01  4598.3  276.41
  4618.3  276.72  4644.5  276.46  4698.3  275.92  4708.3  275.36  4718.3  275.47
  4748.3  272.95  4758.3  272.63  4778.3     270  4798.3  268.26  4838.3  268.22
  4844.5  267.98  4858.3  267.46 4930.41  268.86  4930.5  268.86  4938.3  269.01
  4942.5  268.09  4945.5  267.44  4948.5  261.44  5051.5  261.44  5054.5  267.44
  5057.5  267.76 5069.39  269.02  5069.5  269.03  5078.6     270  5092.9  271.52
  5102.9  273.11  5142.9   276.9  5158.6  279.81  5178.6  283.51  5182.9  284.31
  5192.9  285.85  5198.6  286.37  5208.6  287.29  5218.6  288.21  5222.9   288.6
  5252.9  290.17
BR U #Mann= 3
 4278.30    0.13  4945.5   0.045  5054.5    0.13
BR U Banks=4945.50,5054.50
BR D #Sta/Elev= 41
  4278.3  290.19  4284.5  289.89  4434.5  282.55  4548.3  276.99  4598.3  276.39
  4618.3   276.7  4644.5  276.44  4698.3   275.9  4708.3  275.34  4718.3  275.45
  4748.3  272.93  4758.3  272.61  4778.3  269.98  4798.3  268.24  4838.3   268.2
  4844.5  267.96  4858.3  267.44 4930.41  268.84  4930.5  268.84  4938.3  268.99
  4942.5  268.07  4945.5  267.42  4948.5  261.42  5051.5  261.42  5054.5  267.42
  5057.5  267.74 5069.39     269  5069.5  269.01  5078.6  269.98  5092.9   271.5
  5102.9  273.09  5142.9  276.88  5158.6  279.79  5178.6  283.49  5182.9  284.29
  5192.9  285.83  5198.6  286.35  5208.6  287.27  5218.6  288.19  5222.9  288.58
  5252.9  290.15
BR D #Mann= 3
 4278.30    0.13  4945.5   0.045  5054.5    0.13
BR D Banks=4945.50,5054.50

Type RM Length L Ch R = 1 ,188767.7,541.1,541.1,541.1
BEGIN DESCRIPTION:
Downstream Section of Bridge/Culvert/Weir
END DESCRIPTION:
#Sta/Elev= 25
  4278.3  290.18  4548.3  276.98  4598.3  276.38  4618.3  276.69  4698.3  275.89
  4708.3  275.33  4718.3  275.44  4748.3  272.92  4758.3   272.6  4778.3  269.97
  4798.3  268.23  4838.3  268.19  4858.3  267.43  4938.3  268.98  4945.5  267.41
  4948.5  261.41  5051.5  261.41  5054.5  267.41  5092.9  271.49  5102.9  273.08
  5142.9  276.87  5182.9  284.28  5192.9  285.82  5222.9  288.57  5252.9  290.14
#Mann= 3 , 1 , 0
 4278.30    0.13       0  4945.5   0.045       0  5054.5    0.13       0
#XS Ineff= 2 , 0
       0    4920  274.48    5081       0  274.48
Bank Sta=4945.50,5054.50
Exp/Cntr=0.5,0.3

Type RM Length L Ch R = 1 ,188226.6,739.5,739.5,739.5
BEGIN DESCRIPTION:
Sandy Creek 188.0
END DESCRIPTION:
#Sta/Elev= 28
  3987.7  293.42  4397.7  281.84  4417.7  282.19  4447.7  279.37  4557.7  277.35
  4597.7  277.49  4647.7   275.2  4667.7  274.69  4707.7  271.01  4737.7   269.2
  4747.7  269.33  4757.7   268.5  4817.7   268.1  4827.7  267.72  4867.7  268.37
  4877.7   268.2  4917.7  269.37  4972.9  267.07  4975.9  261.07  5024.1  261.07
  5027.1  267.07  5072.9  271.55  5092.9  274.03  5272.9  283.09  5312.9  283.75
  5382.9  288.92  5402.9  289.86  5423.4  292.19
#Mann= 3 , 1 , 0
 3987.70    0.13       0  4972.9   0.042       0  5027.1    0.13       0
Bank Sta=4972.90,5027.10
Exp/Cntr=0.3,0.1

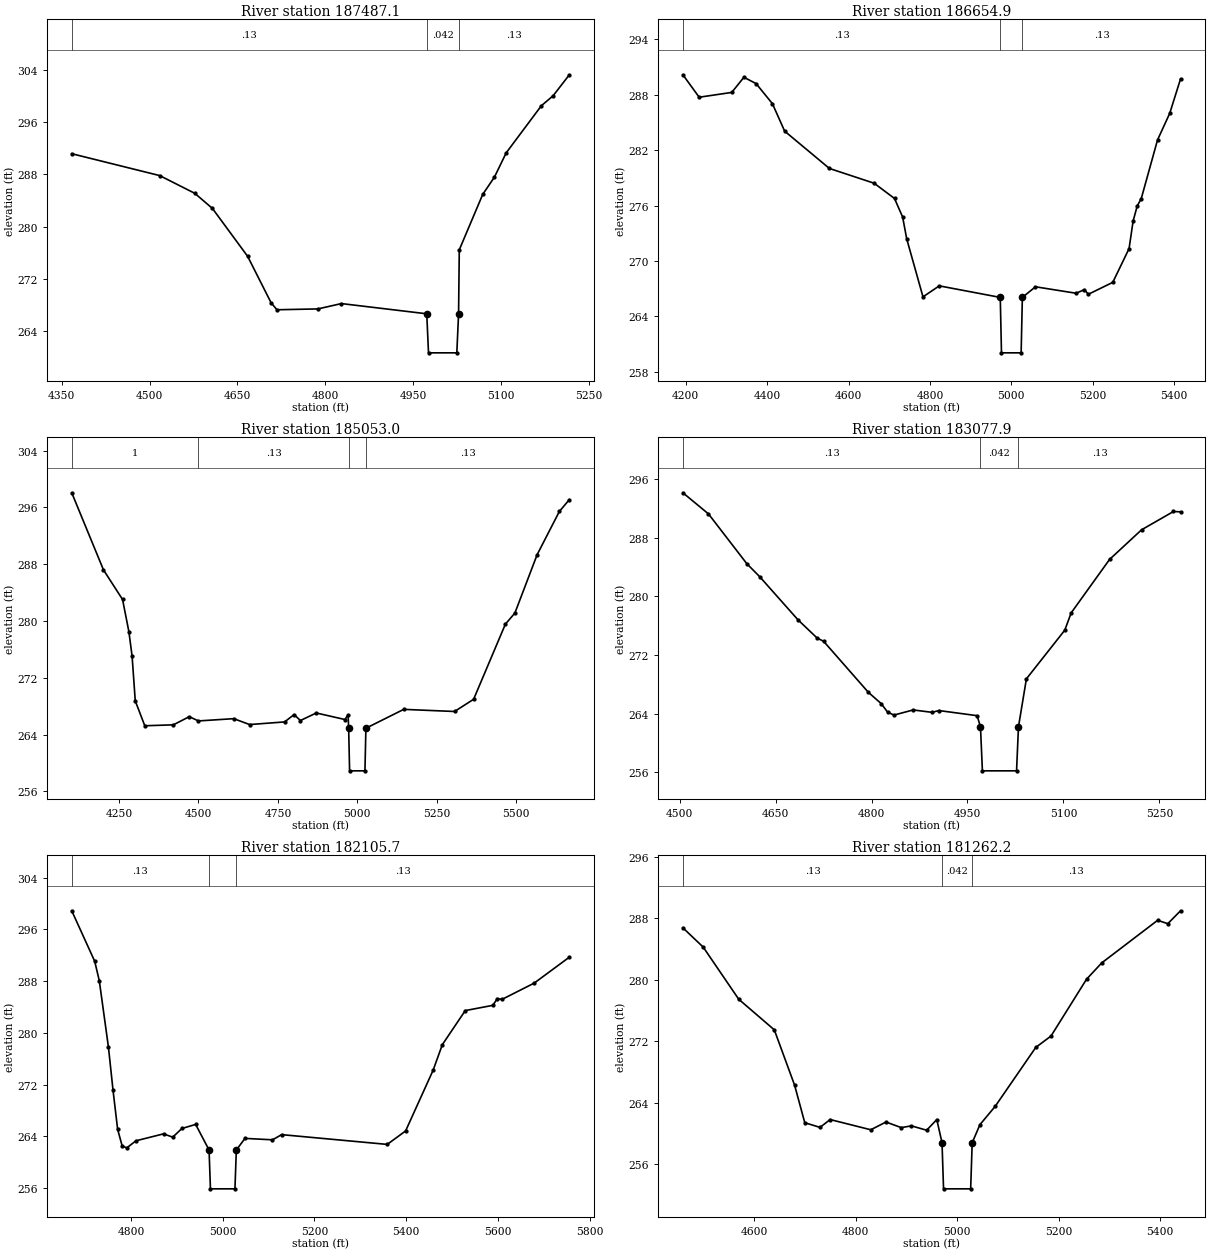
Type RM Length L Ch R = 1 ,187487.1,832.2,832.2,832.2
BEGIN DESCRIPTION:
Sandy Creek 187.0
END DESCRIPTION:
#Sta/Elev= 20
  4367.3  291.19  4517.3  287.83  4577.3   285.1  4607.3  282.78  4667.3  275.43
  4707.3   268.3  4717.3  267.21  4787.3  267.34  4827.3  268.16  4972.9  266.59
  4975.9  260.59  5024.2  260.59  5027.2  266.59  5028.4  276.42  5068.4  284.94
  5088.4   287.6  5108.4  291.32  5168.4  298.56  5188.4  300.09  5216.2  303.32
#Mann= 3 , 1 , 0
 4367.30    0.13       0  4972.9   0.042       0  5027.2    0.13       0
Bank Sta=4972.90,5027.20
Exp/Cntr=0.3,0.1

Type RM Length L Ch R = 1 ,186654.9,1601.9,1601.9,1601.9
BEGIN DESCRIPTION:
Sandy Creek 186.0
END DESCRIPTION:
#Sta/Elev= 30
  4192.9  290.16  4232.9  287.73  4312.9  288.25  4342.9  289.89  4372.9   289.2
  4412.9  287.03  4442.9  284.06  4552.9  280.02  4662.9  278.42  4712.9  276.77
  4732.9  274.76  4742.9   272.4  4782.9  266.12  4822.9  267.31  4972.8  266.06
  4975.8  260.06  5024.1  260.06  5027.1  266.06  5059.3  267.21  5159.3  266.51
  5179.3   266.9  5189.3   266.4  5249.3  267.69  5289.3  271.34  5299.3  274.33
  5309.3  275.95  5319.3  276.76  5359.3  283.11  5389.3  285.99  5415.8  289.71
#Mann= 3 , 1 , 0
 4192.90    0.13       0  4972.8   0.042       0  5027.1    0.13       0
Bank Sta=4972.80,5027.10
Exp/Cntr=0.3,0.1

Type RM Length L Ch R = 1 ,185053.0,1975.1,1975.1,1975.1
BEGIN DESCRIPTION:
Sandy Creek 185.0
END DESCRIPTION:
#Sta/Elev= 30
    4101  298.06    4201  287.19    4261  283.03    4281  278.48    4291  275.06
    4301  268.74    4331  265.24    4421  265.37    4471  266.52  4499.9  265.92
    4611  266.24    4661  265.41    4771  265.78    4801  266.81    4821  265.98
    4871  267.04    4961  266.12    4971  266.79  4972.8  264.89  4975.8  258.89
  5024.1  258.89  5027.1  264.89  5146.2  267.55  5306.2  267.25  5366.2  268.97
  5466.2  279.55  5496.2  281.12  5566.2  289.34  5636.2  295.43  5667.7   297.1
#Mann= 4 , 1 , 0
 4101.00       1       0  4499.9    0.13       0  4972.8   0.042       0
  5027.1    0.13       0
Bank Sta=4972.80,5027.10
Exp/Cntr=0.3,0.1

Type RM Length L Ch R = 1 ,183077.9,972.2,972.2,972.2
BEGIN DESCRIPTION:
Sandy Creek 183.0
END DESCRIPTION:
#Sta/Elev= 26
    4505  294.11    4545  291.23    4605  284.44    4625  282.68    4685  276.79
    4715   274.3    4725  273.87    4795  266.91    4815  265.38    4825  264.22
    4835  263.81    4865  264.51    4895  264.18    4905  264.43    4965  263.73
  4970.3  262.21  4973.3  256.21  5026.7  256.21  5029.7  262.21  5042.1  268.75
  5102.1  275.38  5112.1  277.74  5172.1  285.02  5222.1  289.06  5272.1  291.56
  5283.1  291.51
#Mann= 3 , 1 , 0
 4505.00    0.13       0  4970.3   0.042       0  5029.7    0.13       0
Bank Sta=4970.30,5029.70
Exp/Cntr=0.3,0.1

Type RM Length L Ch R = 1 ,182105.7,843.5,843.5,843.5
BEGIN DESCRIPTION:
Sandy Creek 182.0
END DESCRIPTION:
#Sta/Elev= 30
  4671.1  298.86  4721.1  291.06  4731.1  288.06  4751.1  277.76  4761.1  271.09
  4771.1  265.07  4781.1  262.47  4791.1  262.21  4811.1   263.3  4871.1  264.37
  4891.1  263.86  4911.1   265.2  4941.1  265.83  4970.3  261.87  4973.3  255.87
  5026.7  255.87  5029.7  261.87  5048.5  263.67  5108.5  263.45  5128.5  264.25
  5358.5  262.74  5398.5  264.82  5458.5  274.22  5478.5  278.16  5528.5  283.43
  5588.5  284.24  5598.5  285.29  5608.5  285.16  5678.5  287.67  5755.3  291.69
#Mann= 3 , 1 , 0
 4671.10    0.13       0  4970.3   0.042       0  5029.7    0.13       0
Bank Sta=4970.30,5029.70
Exp/Cntr=0.3,0.1

Type RM Length L Ch R = 1 ,181262.2,916.3,916.3,916.3
BEGIN DESCRIPTION:
Sandy Creek 181.0
END DESCRIPTION:
#Sta/Elev= 27
    4460  286.76    4500  284.25    4570  277.46    4640  273.48    4680  266.27
    4700  261.39    4730  260.78    4750   261.8    4830  260.47    4860  261.48
    4890  260.75    4910  260.98    4940  260.41    4960   261.8  4970.3  258.78
  4973.3  252.78  5026.7  252.78  5029.7  258.78  5044.9  261.13  5074.9  263.51
  5154.9  271.19  5184.9  272.67  5254.9  280.07  5284.9   282.2  5394.9  287.74
  5414.9   287.3    5440  288.98
#Mann= 3 , 1 , 0
 4460.00    0.13       0  4970.3   0.042       0  5029.7    0.13       0
Bank Sta=4970.30,5029.70
Exp/Cntr=0.3,0.1

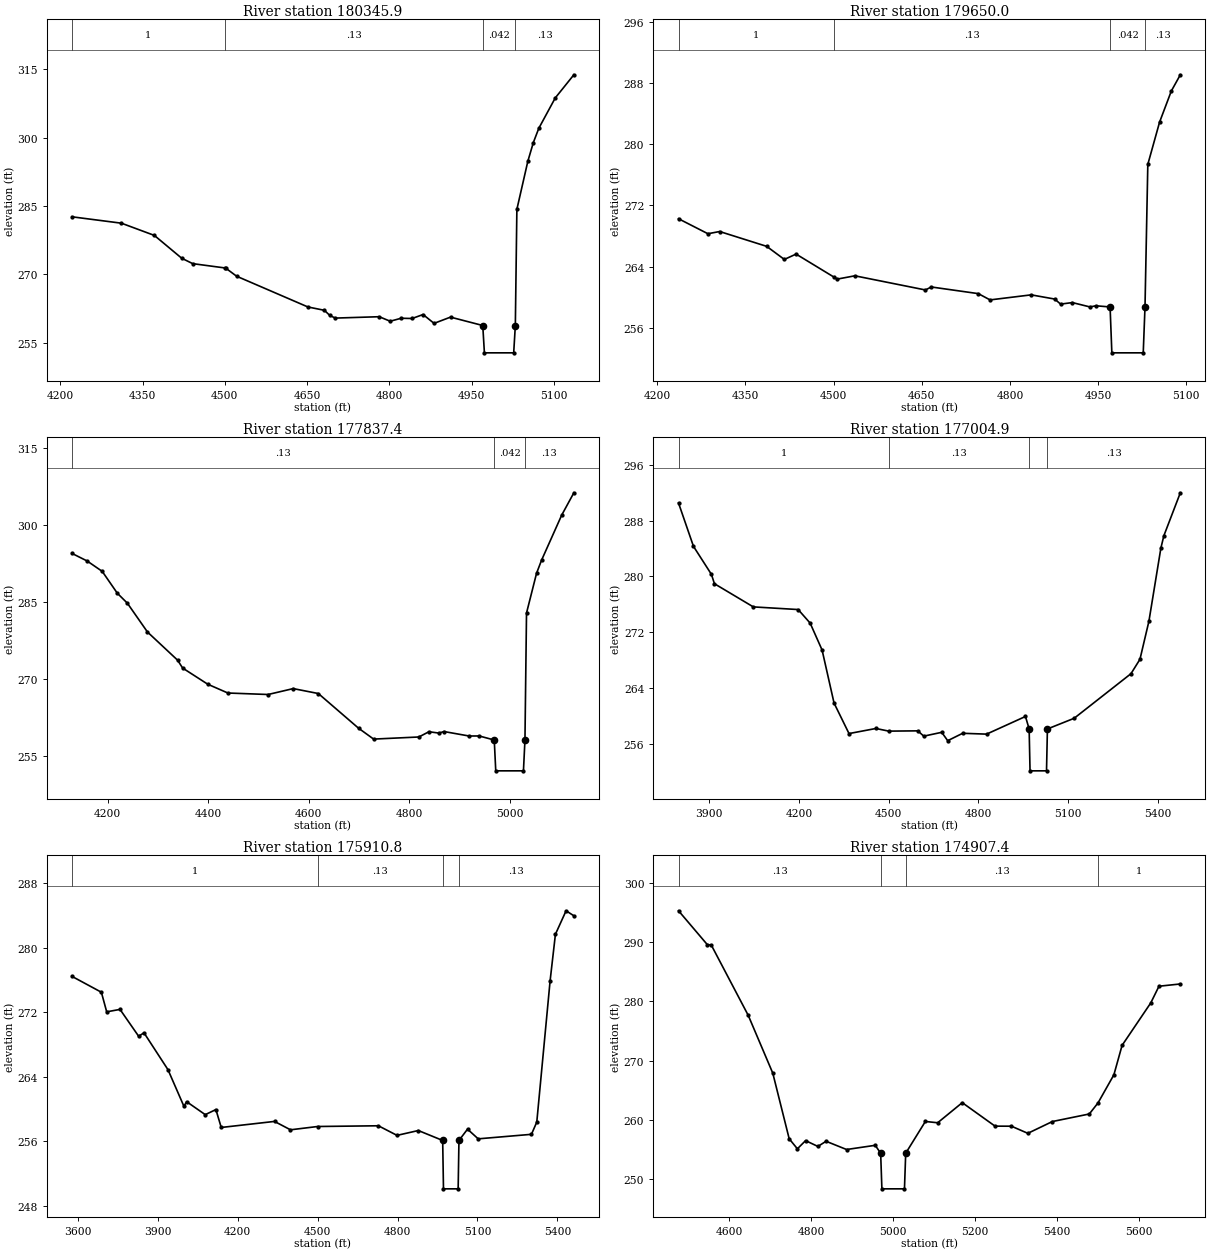
Type RM Length L Ch R = 1 ,180345.9,695.9,695.9,695.9
BEGIN DESCRIPTION:
Sandy Creek 180.0
END DESCRIPTION:
#Sta/Elev= 29
  4221.5  282.61  4311.5  281.21  4371.5  278.53  4421.5  273.51  4441.5  272.33
  4499.9  271.39  4501.5  271.36  4521.5  269.57  4651.5  262.82  4681.5  262.09
  4691.5  260.95  4701.5  260.38  4781.5  260.68  4801.5  259.69  4821.5  260.34
  4841.5  260.29  4861.5  261.16  4881.5  259.22  4911.5  260.59  4970.3  258.75
  4973.3  252.75  5026.7  252.75  5029.7  258.75  5032.5  284.25  5052.5  294.81
  5062.5   298.9  5072.5  302.05  5102.5  308.71  5136.4  313.79
#Mann= 4 , 1 , 0
 4221.50       1       0  4499.9    0.13       0  4970.3   0.042       0
  5029.7    0.13       0
Bank Sta=4970.30,5029.70
Exp/Cntr=0.3,0.1

Type RM Length L Ch R = 1 ,179650.0,1812.6,1812.6,1812.6
BEGIN DESCRIPTION:
Sandy Creek 179.0
END DESCRIPTION:
#Sta/Elev= 27
  4236.1  270.26  4286.1   268.3  4306.1  268.59  4386.1  266.65  4416.1  264.94
  4436.1  265.64  4499.9  262.66  4506.1  262.37  4536.1   262.8  4656.1  260.95
  4666.1  261.34  4746.1  260.47  4766.1  259.65  4836.1  260.31  4876.1  259.76
  4886.1   259.1  4906.1   259.3  4936.1  258.73  4946.1  258.88  4970.3  258.73
  4973.3  252.73  5026.7  252.73  5029.7  258.73  5034.5  277.37  5054.5  282.89
  5074.5  286.96  5089.8  289.08
#Mann= 4 , 1 , 0
 4236.10       1       0  4499.9    0.13       0  4970.3   0.042       0
  5029.7    0.13       0
Bank Sta=4970.30,5029.70
Exp/Cntr=0.3,0.1

Type RM Length L Ch R = 1 ,177837.4,832.5,832.5,832.5
BEGIN DESCRIPTION:
Sandy Creek 178.0
END DESCRIPTION:
#Sta/Elev= 30
  4129.5   294.5  4159.5  293.03  4189.5  291.01  4219.5  286.76  4239.5  284.82
  4279.5  279.21  4339.5  273.72  4349.5  272.19  4399.5  269.04  4439.5  267.33
  4519.5  267.04  4569.5  268.19  4619.5  267.23  4699.5  260.48  4729.5  258.36
  4819.5  258.77  4839.5  259.79  4859.5  259.53  4869.5  259.83  4919.5  258.96
  4939.5  258.97  4969.5  258.18  4972.5  252.18  5027.6  252.18  5030.6  258.18
  5033.7   282.9  5053.7  290.65  5063.7   293.2  5103.7  301.96  5127.9  306.31
#Mann= 3 , 1 , 0
 4129.50    0.13       0  4969.5   0.042       0  5030.6    0.13       0
Bank Sta=4969.50,5030.60
Exp/Cntr=0.3,0.1

Type RM Length L Ch R = 1 ,177004.9,1094.1,1094.1,1094.1
BEGIN DESCRIPTION:
Sandy Creek 177.0
END DESCRIPTION:
#Sta/Elev= 30
  3797.2  290.51  3847.2   284.3  3907.2  280.29  3917.2  278.95  4047.2  275.63
  4197.2  275.25  4237.2  273.31  4277.2  269.45  4317.2  261.85  4367.2  257.48
  4457.2  258.21  4499.9  257.83  4597.2  257.87  4617.2  257.11  4677.2  257.66
  4697.2  256.46  4747.2  257.52  4827.2   257.4  4957.2  259.93  4969.5  258.14
  4972.5  252.14  5027.6  252.14  5030.6  258.14    5120  259.67    5310  266.06
    5340  268.12    5370  273.58    5410  284.06    5420  285.83    5475  291.98
#Mann= 4 , 1 , 0
 3797.20       1       0  4499.9    0.13       0  4969.5   0.042       0
  5030.6    0.13       0
Bank Sta=4969.50,5030.60
Exp/Cntr=0.3,0.1

Type RM Length L Ch R = 1 ,175910.8,1003.4,1003.4,1003.4
BEGIN DESCRIPTION:
Sandy Creek 176.0
END DESCRIPTION:
#Sta/Elev= 30
    3578  276.45    3688  274.49    3708  272.06    3758  272.36    3828  269.03
    3848  269.46    3938  264.89    3998  260.34    4008  260.92    4078  259.31
    4118  259.94    4138  257.72    4338  258.47    4398  257.43  4499.9  257.84
    4728  257.93    4798  256.74    4878  257.34  4969.4  256.11  4972.4  250.11
  5027.5  250.11  5030.5  256.11  5062.7  257.51  5102.7  256.31  5302.7  256.87
  5322.7  258.39  5372.7   275.9  5392.7  281.68  5432.7  284.59  5461.9  283.97
#Mann= 4 , 1 , 0
 3578.00       1       0  4499.9    0.13       0  4969.4   0.042       0
  5030.5    0.13       0
Bank Sta=4969.40,5030.50
Exp/Cntr=0.3,0.1

Type RM Length L Ch R = 1 ,174907.4,1174.7,1174.7,1174.7
BEGIN DESCRIPTION:
Sandy Creek 175.0
END DESCRIPTION:
#Sta/Elev= 30
  4476.3  295.27  4546.3  289.58  4556.3  289.48  4646.3  277.65  4706.3  267.89
  4746.3  256.83  4766.3  255.14  4786.3  256.52  4816.3  255.54  4836.3  256.41
  4886.3  255.02  4956.3  255.73  4969.5  254.39  4972.5  248.39  5027.6  248.39
  5030.6  254.39  5078.6  259.75  5108.6  259.53  5168.6  262.92  5248.6  258.96
  5288.6  258.95  5328.6  257.75  5388.6  259.74  5478.6  261.01  5499.9  262.88
  5538.6  267.62  5558.6  272.58  5628.6  279.74  5648.6  282.55  5700.7  282.93
#Mann= 4 , 1 , 0
 4476.30    0.13       0  4969.5   0.042       0  5030.6    0.13       0
  5499.9       1       0
Bank Sta=4969.50,5030.60
Exp/Cntr=0.3,0.1

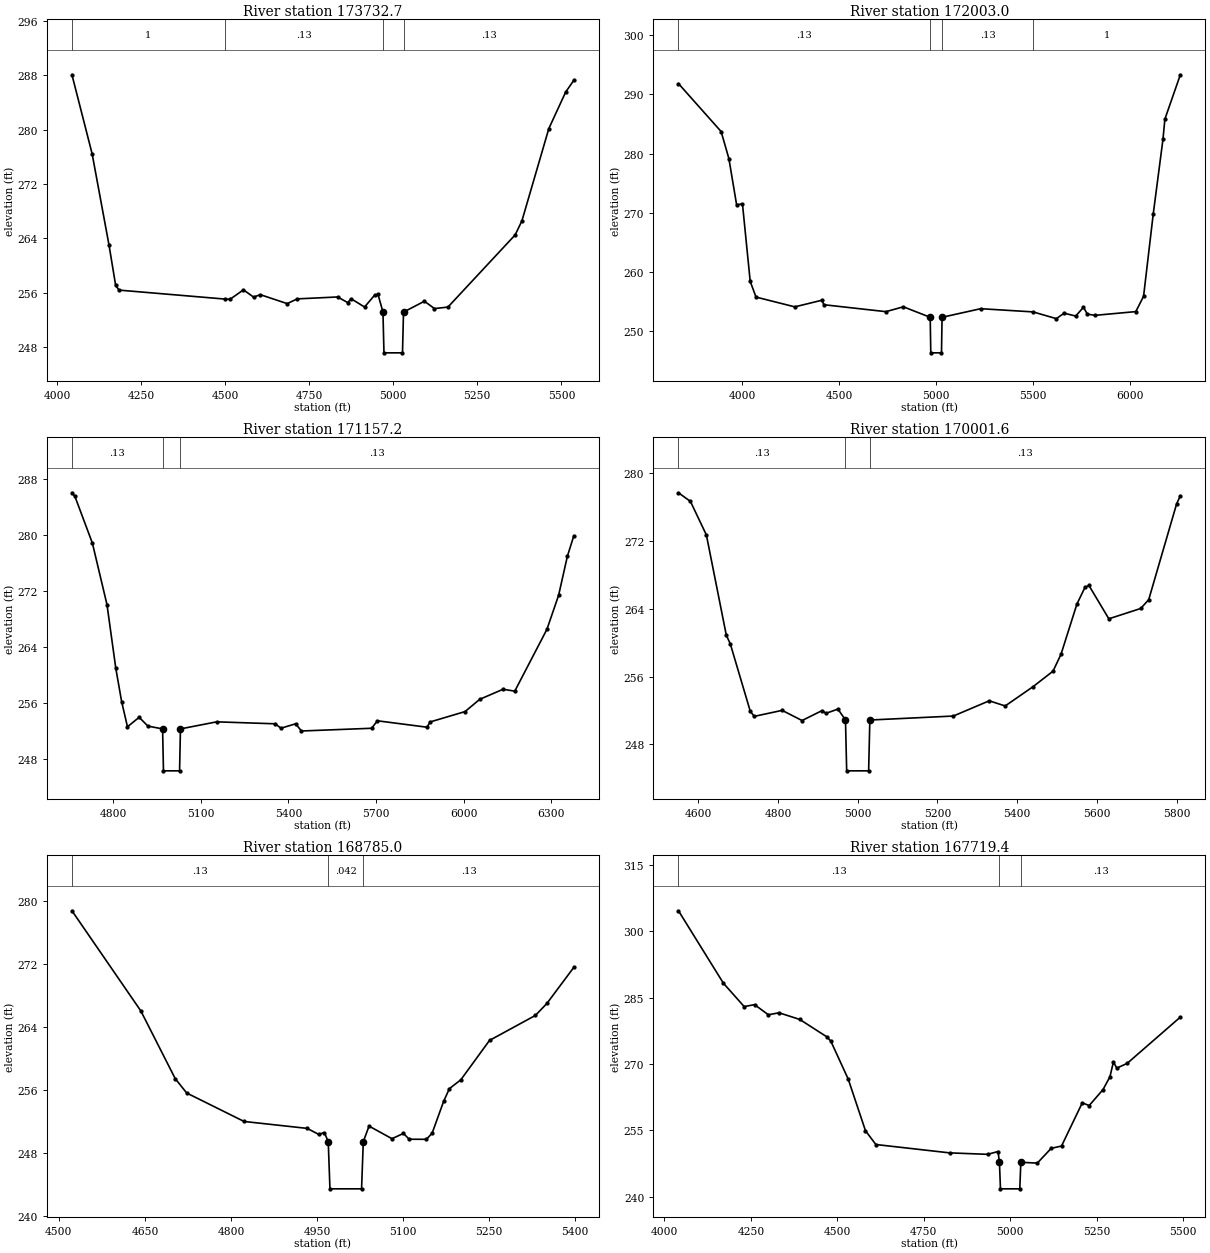
Type RM Length L Ch R = 1 ,173732.7,1729.7,1729.7,1729.7
BEGIN DESCRIPTION:
Sandy Creek 174.0
END DESCRIPTION:
#Sta/Elev= 30
  4044.8  288.09  4104.8  276.45  4154.8  263.06  4174.8  257.06  4184.8  256.37
  4499.9  255.05  4514.8  255.02  4554.8  256.41  4584.8  255.34  4604.8   255.7
  4684.8  254.38  4714.8  255.08  4834.8  255.36  4864.8  254.53  4874.8   255.1
  4914.8  253.88  4944.8  255.63  4954.8  255.74  4969.5  253.13  4972.5  247.13
  5027.6  247.13  5030.6  253.13  5092.7  254.73  5122.7  253.65  5162.7  253.87
  5362.7  264.51  5382.7  266.58  5462.7  280.17  5512.7  285.54  5536.9  287.27
#Mann= 4 , 1 , 0
 4044.80       1       0  4499.9    0.13       0  4969.5   0.042       0
  5030.6    0.13       0
Bank Sta=4969.50,5030.60
Exp/Cntr=0.3,0.1

Type RM Length L Ch R = 1 ,172003.0,845.8,845.8,845.8
BEGIN DESCRIPTION:
Sandy Creek 172.0
END DESCRIPTION:
#Sta/Elev= 30
  3670.9  291.83  3890.9  283.74  3930.9  279.18  3970.9  271.36  4000.9  271.55
  4040.9  258.45  4070.9   255.8  4270.9  254.15  4410.9  255.27  4420.9  254.51
  4740.9  253.34  4830.9  254.16  4969.4  252.39  4972.4  246.39  5027.6  246.39
  5030.6  252.39    5230  253.84  5499.9   253.3    5620  252.16    5660  253.08
    5720   252.6    5760  254.08    5780  252.92    5820  252.72    6030  253.35
    6070  255.93    6120  269.85    6170  282.41    6180  285.84  6259.6  293.32
#Mann= 4 , 1 , 0
 3670.90    0.13       0  4969.4   0.042       0  5030.6    0.13       0
  5499.9       1       0
Bank Sta=4969.40,5030.60
Exp/Cntr=0.3,0.1

Type RM Length L Ch R = 1 ,171157.2,1155.6,1155.6,1155.6
BEGIN DESCRIPTION:
Sandy Creek 171.0
END DESCRIPTION:
#Sta/Elev= 30
  4659.2  286.06  4669.2  285.56  4729.2  278.85  4779.2  270.04  4809.2  260.97
  4829.2  256.19  4849.2  252.58  4889.2  253.94  4919.2  252.68  4969.4  252.28
  4972.4  246.28  5027.5  246.28  5030.5  252.28  5154.6  253.29  5354.6  253.01
  5374.6  252.38  5424.6  253.01  5444.6  251.98  5684.6  252.37  5704.6  253.44
  5874.6  252.52  5884.6  253.27  6004.6  254.76  6054.6  256.51  6134.6  257.95
  6174.6  257.68  6284.6  266.52  6324.6  271.39  6354.6  276.97  6376.6   279.9
#Mann= 3 , 1 , 0
 4659.20    0.13       0  4969.4   0.042       0  5030.5    0.13       0
Bank Sta=4969.40,5030.50
Exp/Cntr=0.3,0.1

Type RM Length L Ch R = 1 ,170001.6,1216.6,1216.6,1216.6
BEGIN DESCRIPTION:
Sandy Creek 170.0
END DESCRIPTION:
#Sta/Elev= 30
  4550.5   277.7  4580.5  276.68  4620.5  272.72  4670.5  260.88  4680.5  259.86
  4730.5  251.92  4740.5   251.3  4810.5  252.01  4860.5  250.81  4910.5  251.98
  4920.5  251.66  4950.5  252.16  4969.4  250.87  4972.4  244.87  5027.5  244.87
  5030.5  250.87    5240  251.34    5330  253.14    5370  252.53    5440  254.81
    5490  256.64    5510  258.63    5550  264.57    5570  266.52    5580  266.76
    5630  262.82    5710  264.04    5730  265.08    5800  276.39  5809.3  277.34
#Mann= 3 , 1 , 0
 4550.50    0.13       0  4969.4   0.042       0  5030.5    0.13       0
Bank Sta=4969.40,5030.50
Exp/Cntr=0.3,0.1

Type RM Length L Ch R = 1 ,168785.0,1065.6,1065.6,1065.6
BEGIN DESCRIPTION:
Sandy Creek 169.0
END DESCRIPTION:
#Sta/Elev= 25
  4522.8  278.79  4642.8  266.06  4702.8  257.44  4722.8  255.61  4822.8  251.99
  4932.8  251.11  4952.8  250.35  4962.8  250.58  4969.5  249.42  4972.5  243.42
  5027.6  243.42  5030.6  249.42  5040.6   251.4  5080.6   249.8  5100.6  250.47
  5110.6  249.73  5140.6  249.72  5150.6   250.5  5170.6  254.54  5180.6  256.16
  5200.6  257.29  5250.6   262.3  5330.6  265.48  5350.6     267  5397.5  271.59
#Mann= 3 , 1 , 0
 4522.80    0.13       0  4969.5   0.042       0  5030.6    0.13       0
Bank Sta=4969.50,5030.60
Exp/Cntr=0.3,0.1

Type RM Length L Ch R = 1 ,167719.4,408.9,408.9,408.9
BEGIN DESCRIPTION:
Sandy Creek 166.0
END DESCRIPTION:
#Sta/Elev= 30
  4040.7  304.66  4170.7  288.28  4230.7     283  4260.7  283.44  4300.7  281.15
  4331.6   281.6  4391.6  280.09  4471.6  276.07  4481.6  275.14  4531.6  266.62
  4581.6  254.93  4611.6  251.82    4825  249.93    4935   249.6    4965  250.24
    4969   247.8    4972   241.8  5027.9   241.8  5030.9   247.8  5078.6  247.62
  5118.6  250.95  5148.6  251.48  5208.6  261.24  5228.6  260.63  5268.6  264.24
  5288.6  267.13  5298.6  270.46  5308.6  269.09  5338.6  270.17  5492.2  280.62
#Mann= 3 , 1 , 0
 4040.70    0.13       0    4969   0.042       0  5030.9    0.13       0
Bank Sta=4969.00,5030.90
Exp/Cntr=0.3,0.1