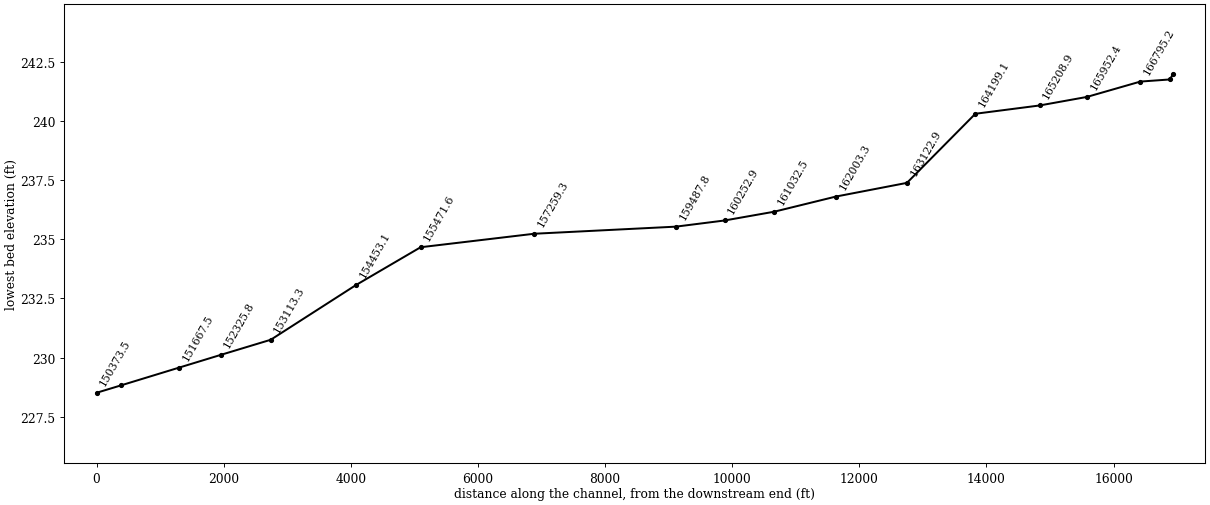
HEC-RAS study 020822_SANDY_CREEK.prj: Sandy Creek

--- 020822_SANDY_CREEK.g01 (geometry) --- (continued)

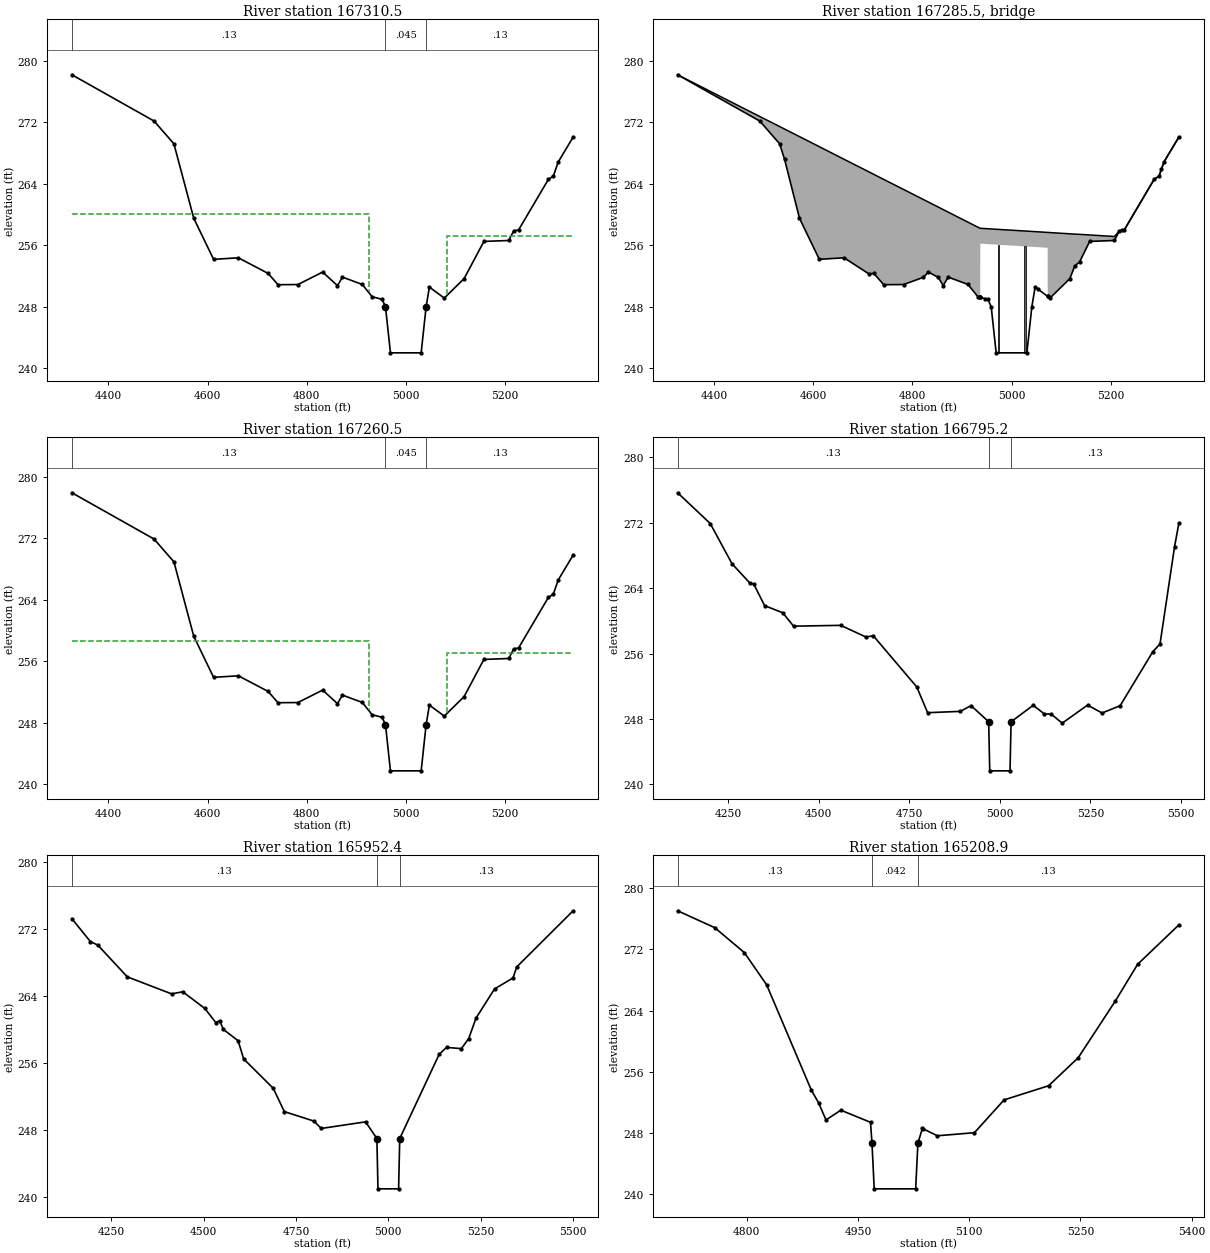
Type RM Length L Ch R = 1 ,167310.5,50,50,50
BEGIN DESCRIPTION:
Upstream Section of Bridge/Culvert/Weir
END DESCRIPTION:
#Sta/Elev= 30
  4326.4  278.15  4492.2  272.13  4532.2  269.17  4572.2  259.49  4612.2  254.15
  4662.2  254.35  4722.2  252.32  4742.2  250.85  4782.2  250.87  4832.2  252.49
  4862.2  250.73  4872.2  251.84  4912.2  250.88  4932.2  249.28  4952.2  248.95
    4959  247.99    4969  241.99    5031  241.99    5041  247.99  5047.6  250.54
  5077.6  249.11  5117.6  251.64  5157.6  256.48  5207.6   256.6  5217.6  257.84
  5227.6  257.98  5287.6  264.54  5297.6  264.97  5307.6  266.82  5337.6  270.05
#Mann= 3 , 1 , 0
 4326.40    0.13       0    4959   0.045       0    5041    0.13       0
#XS Ineff= 2 , 0
       0    4925     260 5083.54       0  257.13
Bank Sta=4959.00,5041.00
Exp/Cntr=0.5,0.3

Type RM Length L Ch R = 3 ,167285.5,,,
BEGIN DESCRIPTION:
Pete Smith Rd-2-TOR
Structure ID: Pete Smith Rd_sandy-Bridge
Approximate Survey Structure
END DESCRIPTION:
Bridge Culvert--1,0,-1,-1, 0
Deck Dist Width WeirC Skew NumUp NumDn MinLoCord MaxHiCord MaxSubmerge Is_Ogee
10,30,2.6,,45,45,,,0.95,0,1,1,,
  4326.4  4492.2  4532.2  4542.2  4572.2  4612.2  4662.2  4712.2  4722.2  4742.2
  4782.2  4822.2  4832.2  4852.2  4862.2  4872.2  4912.2  4932.2  4936.4 4936.91
    4937  4946.5  4952.2    4959    4969    5031    5041  5047.6  5053.5 5072.89
    5073  5077.6  5117.6  5127.6  5137.6  5157.6  5207.6  5217.6  5222.5  5227.6
  5287.6  5297.6  5302.5  5307.6  5337.6
  278.16  272.73  271.43   271.1  270.12  268.81  267.17  265.54  265.21  264.55
  263.25  261.94  261.61  260.96  260.63   260.3  258.99  258.34   258.2   258.2
   258.2  258.16  258.14  258.11  258.07  257.83  257.79  257.76  257.74  257.66
  257.66  257.64  257.48  257.44  257.41  257.33  257.13  257.86  257.93     258
  264.56  264.99   265.9  266.83  270.06
  278.16  272.14  269.18  267.15   259.5  254.16  254.36  252.27  252.33  250.86
  250.88  251.82   252.5  251.82  250.74  251.85  250.89  249.29  249.22  249.21
   256.2  256.16  256.14  256.11  256.07  255.83  255.79  255.76  255.74  255.66
  249.34  249.12  251.65  253.29  253.85  256.49  256.61  257.85  257.92  257.99
  264.55  264.98  265.89  266.83  270.06
  4326.4  4492.2  4532.2  4542.2  4572.2  4612.2  4662.2  4712.2  4722.2  4742.2
  4782.2  4822.2  4832.2  4852.2  4862.2  4872.2  4912.2  4932.2  4936.4 4936.91
    4937  4946.5  4952.2    4959    4969    5031    5041  5047.6  5053.5 5072.89
    5073  5077.6  5117.6  5127.6  5137.6  5157.6  5207.6  5217.6  5222.5  5227.6
  5287.6  5297.6  5302.5  5307.6  5337.6
  278.16  272.73  271.43   271.1  270.12  268.81  267.17  265.54  265.21  264.55
  263.25  261.94  261.61  260.96  260.63   260.3  258.99  258.34   258.2   258.2
   258.2  258.16  258.14  258.11  258.07  257.83  257.79  257.76  257.74  257.66
  257.66  257.64  257.48  257.44  257.41  257.33  257.13  257.86  257.93     258
  264.56  264.99   265.9  266.83  270.06
  277.91  271.89  268.93   266.9  259.25  253.91  254.11  252.02  252.08  250.61
  250.63  251.57  252.25  251.57  250.49   251.6  250.64  249.04  248.97  248.96
  255.95  255.91  255.89  255.86  255.82  255.58  255.54  255.51  255.49  255.41
  249.09  248.87   251.4  253.04   253.6  256.24  256.36   257.6  257.67  257.74
   264.3  264.73  265.64  266.58  269.81
Pier Skew, UpSta & Num, DnSta & Num=,4973.3, 2 ,4973.3, 2 , 0 , 0 , 0 ,,
       3       3
     241  257.06
       3       3
  240.75  256.81
Pier Skew, UpSta & Num, DnSta & Num=,5026.8, 2 ,5026.8, 2 , 0 , 0 , 0 ,,
       3       3
     241  256.85
       3       3
  240.75   256.6
Abutment Skew #Up #Dn=, 2 , 2
 4936.80 4946.50
  256.20  249.05
 4936.80 4946.50
  255.95  248.80
Abutment Skew #Up #Dn=, 2 , 2
 5053.50 5073.09
  250.27  255.66
 5053.50 5073.09
  250.02  255.41
BR Coef= 1 , 1 , 0 ,1.25, 0 ,,,0.8,0,2,0,
Wspro=,,,, 1 ,,,, 0 ,,,, 0 ,,,,-1 ,-1 ,-1 , 0 , 0 , 0 , 0 , 0
BC Design=,, 0 ,, 0 ,,,,,,
BR U #Sta/Elev= 45
  4326.4  278.16  4492.2  272.14  4532.2  269.18  4542.2  267.15  4572.2   259.5
  4612.2  254.16  4662.2  254.36  4712.2  252.27  4722.2  252.33  4742.2  250.86
  4782.2  250.88  4822.2  251.82  4832.2   252.5  4852.2  251.82  4862.2  250.74
  4872.2  251.85  4912.2  250.89  4932.2  249.29  4936.4  249.22 4936.91  249.21
    4937  249.21  4946.5  249.05  4952.2  248.96    4959     248    4969     242
    5031     242    5041     248  5047.6  250.55  5053.5  250.27 5072.89  249.34
    5073  249.34  5077.6  249.12  5117.6  251.65  5127.6  253.29  5137.6  253.85
  5157.6  256.49  5207.6  256.61  5217.6  257.85  5222.5  257.92  5227.6  257.99
  5287.6  264.55  5297.6  264.98  5302.5  265.89  5307.6  266.83  5337.6  270.06
BR U #Mann= 3
 4326.40    0.13    4959   0.045    5041    0.13
BR U Banks=4959.00,5041.00
BR D #Sta/Elev= 45
  4326.4  277.91  4492.2  271.89  4532.2  268.93  4542.2   266.9  4572.2  259.25
  4612.2  253.91  4662.2  254.11  4712.2  252.02  4722.2  252.08  4742.2  250.61
  4782.2  250.63  4822.2  251.57  4832.2  252.25  4852.2  251.57  4862.2  250.49
  4872.2   251.6  4912.2  250.64  4932.2  249.04  4936.4  248.97 4936.91  248.96
    4937  248.96  4946.5   248.8  4952.2  248.71    4959  247.75    4969  241.75
    5031  241.75    5041  247.75  5047.6   250.3  5053.5  250.02 5072.89  249.09
    5073  249.09  5077.6  248.87  5117.6   251.4  5127.6  253.04  5137.6   253.6
  5157.6  256.24  5207.6  256.36  5217.6   257.6  5222.5  257.67  5227.6  257.74
  5287.6   264.3  5297.6  264.73  5302.5  265.64  5307.6  266.58  5337.6  269.81
BR D #Mann= 3
 4326.40    0.13    4959   0.045    5041    0.13
BR D Banks=4959.00,5041.00

Type RM Length L Ch R = 1 ,167260.5,465.3,465.3,465.3
BEGIN DESCRIPTION:
Downstream Section of Bridge/Culvert/Weir
END DESCRIPTION:
#Sta/Elev= 30
  4326.4  277.91  4492.2  271.89  4532.2  268.93  4572.2  259.25  4612.2  253.91
  4662.2  254.11  4722.2  252.08  4742.2  250.61  4782.2  250.63  4832.2  252.25
  4862.2  250.49  4872.2   251.6  4912.2  250.64  4932.2  249.04  4952.2  248.71
    4959  247.75    4969  241.75    5031  241.75    5041  247.75  5047.6   250.3
  5077.6  248.87  5117.6   251.4  5157.6  256.24  5207.6  256.36  5217.6   257.6
  5227.6  257.74  5287.6   264.3  5297.6  264.73  5307.6  266.58  5337.6  269.81
#Mann= 3 , 1 , 0
 4326.40    0.13       0    4959   0.045       0    5041    0.13       0
#XS Ineff= 2 , 0
       0    4925  258.62 5083.54       0  257.13
Bank Sta=4959.00,5041.00
Exp/Cntr=0.5,0.3

Type RM Length L Ch R = 1 ,166795.2,842.8,842.8,842.8
BEGIN DESCRIPTION:
Sandy Creek 167.0
END DESCRIPTION:
#Sta/Elev= 30
  4110.6  275.66  4200.6   271.9  4260.6  266.99  4310.6  264.59  4320.6  264.51
  4350.6  261.86  4400.6  260.99  4430.6  259.35  4560.6  259.45  4630.6  258.02
  4650.6  258.18  4770.6  251.92  4800.6  248.77  4890.6  248.93  4920.6  249.63
  4969.1  247.66  4972.1  241.66    5028  241.66    5031  247.66  5092.1  249.68
  5122.1  248.64  5142.1  248.58  5172.1  247.49  5242.1   249.7  5282.1  248.73
  5332.1  249.63  5422.1  256.22  5442.1  257.18  5482.1  269.03  5494.1  271.94
#Mann= 3 , 1 , 0
 4110.60    0.13       0  4969.1   0.042       0    5031    0.13       0
Bank Sta=4969.10,5031.00
Exp/Cntr=0.3,0.1

Type RM Length L Ch R = 1 ,165952.4,743.5,743.5,743.5
BEGIN DESCRIPTION:
Sandy Creek 165.5
END DESCRIPTION:
#Sta/Elev= 30
  4143.2  273.22  4193.2   270.5  4213.2  270.08  4293.2  266.29  4413.2  264.26
  4443.2  264.51  4503.2  262.52  4533.2  260.82  4543.2  261.07  4553.2  260.03
  4593.2  258.67  4608.4   256.5  4688.4     253  4718.4  250.22  4798.4  249.09
  4818.4  248.21  4938.4     249    4969  247.01    4972  241.01  5027.9  241.01
  5030.9  247.01  5137.7  257.05  5157.7  257.88  5197.7  257.73  5217.7  258.93
  5237.7  261.39  5287.7  264.85  5337.7  266.16  5347.7  267.47  5500.5  274.17
#Mann= 3 , 1 , 0
 4143.20    0.13       0    4969   0.042       0  5030.9    0.13       0
Bank Sta=4969.00,5030.90
Exp/Cntr=0.3,0.1

Type RM Length L Ch R = 1 ,165208.9,1009.8,1009.8,1009.8
BEGIN DESCRIPTION:
Sandy Creek 165.0
END DESCRIPTION:
#Sta/Elev= 23
    4707  277.06    4757  274.85    4797  271.58    4827  267.36    4887  253.63
    4897  251.91    4907  249.67    4927  250.95    4967  249.36    4969  246.65
    4972  240.65  5027.9  240.65  5030.9  246.65    5037  248.56  5037.1  248.55
  5057.1   247.6  5107.1     248  5147.1   252.3  5207.1  254.15  5247.1  257.83
  5297.1  265.25  5327.1  270.05  5382.7  275.21
#Mann= 3 , 1 , 0
 4707.00    0.13       0    4969   0.042       0  5030.9    0.13       0
Bank Sta=4969.00,5030.90
Exp/Cntr=0.3,0.1

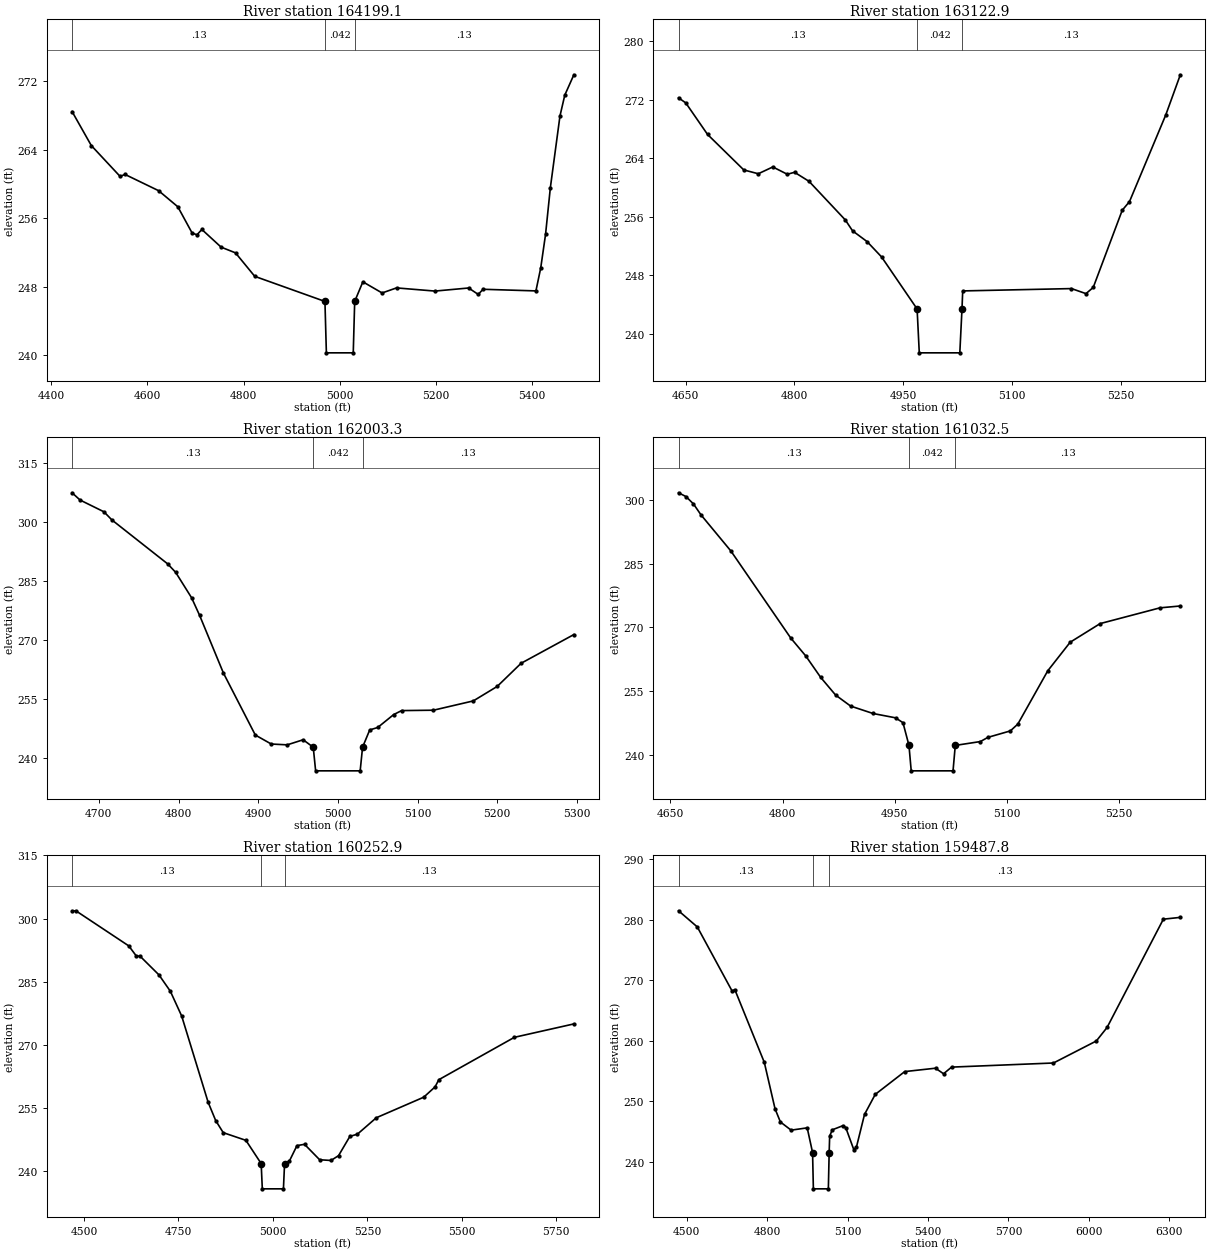
Type RM Length L Ch R = 1 ,164199.1,1076.2,1076.2,1076.2
BEGIN DESCRIPTION:
Sandy Creek 164.0
END DESCRIPTION:
#Sta/Elev= 30
  4443.1  268.47  4483.1   264.5  4543.1  260.89  4553.1  261.13  4623.1  259.23
  4663.1  257.35  4693.1  254.26  4703.1  254.09  4713.1   254.7  4753.1  252.64
  4783.1  251.97  4823.1  249.23  4969.1   246.3  4972.1   240.3    5028   240.3
    5031   246.3    5048  248.59    5088  247.29    5118  247.88    5198  247.51
    5268  247.87    5288  247.12    5298  247.72    5408  247.53    5418  250.22
    5428  254.12    5438  259.58    5458  267.95    5468  270.38  5486.9  272.76
#Mann= 3 , 1 , 0
 4443.10    0.13       0  4969.1   0.042       0    5031    0.13       0
Bank Sta=4969.10,5031.00
Exp/Cntr=0.3,0.1

Type RM Length L Ch R = 1 ,163122.9,1119.6,1119.6,1119.6
BEGIN DESCRIPTION:
Sandy Creek 163.0
END DESCRIPTION:
#Sta/Elev= 25
  4640.1  272.27  4650.1  271.57  4680.1  267.26  4730.1   262.4  4750.1  261.88
  4770.1  262.81  4790.1  261.81  4800.1  262.08  4820.1  260.84  4870.1  255.56
  4880.1  254.07  4900.1   252.6  4920.1   250.5  4969.1  243.38  4972.1  237.38
    5028  237.38    5031  243.38    5032  245.85    5182  246.17    5202  245.48
    5212  246.33    5252  256.89    5262  258.07    5312  269.92  5332.1  275.42
#Mann= 3 , 1 , 0
 4640.10    0.13       0  4969.1   0.042       0    5031    0.13       0
Bank Sta=4969.10,5031.00
Exp/Cntr=0.3,0.1

Type RM Length L Ch R = 1 ,162003.3,970.8,970.8,970.8
BEGIN DESCRIPTION:
Sandy Creek 162.0
END DESCRIPTION:
#Sta/Elev= 26
  4666.4  307.42  4676.4  305.58  4706.4  302.59  4716.4  300.52  4786.4  289.36
  4796.4  287.22  4816.4  280.76  4826.4  276.32  4856.4  261.62  4896.4  245.89
  4916.4  243.61  4936.4   243.4  4956.4  244.69  4969.1   242.8  4972.1   236.8
    5028   236.8    5031   242.8    5040  247.19    5050  247.81    5070  251.08
    5080   252.1    5120   252.2    5170  254.56    5200  258.24    5230  264.12
  5296.2  271.41
#Mann= 3 , 1 , 0
 4666.40    0.13       0  4969.1   0.042       0    5031    0.13       0
Bank Sta=4969.10,5031.00
Exp/Cntr=0.3,0.1

Type RM Length L Ch R = 1 ,161032.5,779.6,779.6,779.6
BEGIN DESCRIPTION:
Sandy Creek 161.0
END DESCRIPTION:
#Sta/Elev= 26
    4661  301.77    4671  300.87    4681  299.13    4691  296.56    4731  288.03
    4811  267.49    4831  263.28    4851  258.21    4871  254.03    4891  251.44
    4921  249.69    4951  248.67    4961  247.52    4969  242.16    4972  236.16
  5027.9  236.16  5030.9  242.16  5064.5  243.07  5074.5  244.06  5104.5  245.58
  5114.5  247.19  5154.5  259.76  5184.5  266.51  5224.5   270.9  5304.5  274.62
  5331.7  275.06
#Mann= 3 , 1 , 0
 4661.00    0.13       0    4969   0.042       0  5030.9    0.13       0
Bank Sta=4969.00,5030.90
Exp/Cntr=0.3,0.1

Type RM Length L Ch R = 1 ,160252.9,765.1,765.1,765.1
BEGIN DESCRIPTION:
Sandy Creek 160.0
END DESCRIPTION:
#Sta/Elev= 30
  4468.6  301.77  4478.6  301.85  4618.6  293.51  4638.6  291.11  4648.6  291.06
  4698.6  286.61  4728.6  282.74  4758.6  276.86  4828.6  256.37  4848.6  252.02
  4868.6  249.14  4928.6  247.31    4969  241.79    4972  235.79  5027.9  235.79
  5030.9  241.79  5043.7   242.4  5063.7  246.06  5083.7  246.37  5123.7   242.7
  5153.7  242.53  5173.7  243.67  5203.7  248.25  5223.7  248.78  5273.7  252.68
  5399.1  257.56  5429.1  260.01  5439.1  261.72  5639.1  271.79  5796.4  274.97
#Mann= 3 , 1 , 0
 4468.60    0.13       0    4969   0.042       0  5030.9    0.13       0
Bank Sta=4969.00,5030.90
Exp/Cntr=0.3,0.1

Type RM Length L Ch R = 1 ,159487.8,2228.5,2228.5,2228.5
BEGIN DESCRIPTION:
Sandy Creek 159.0
END DESCRIPTION:
#Sta/Elev= 30
  4469.1  281.49  4539.1  278.82  4669.1  268.21  4679.1  268.46  4789.1  256.43
  4829.1  248.76  4849.1  246.58  4889.1  245.23  4949.1  245.61  4969.1  241.53
  4972.1  235.53    5028  235.53    5031  241.53  5032.9  244.27  5042.9  245.29
  5082.9  245.98  5092.9  245.65  5122.9  242.01  5132.9  242.46  5162.9  247.83
  5202.9  251.14  5312.9  254.91  5427.7  255.47  5457.7  254.55  5487.7  255.65
  5867.7  256.33  6027.7  259.97  6067.7   262.2  6277.7   280.1    6341   280.4
#Mann= 3 , 1 , 0
 4469.10    0.13       0  4969.1   0.042       0    5031    0.13       0
Bank Sta=4969.10,5031.00
Exp/Cntr=0.3,0.1

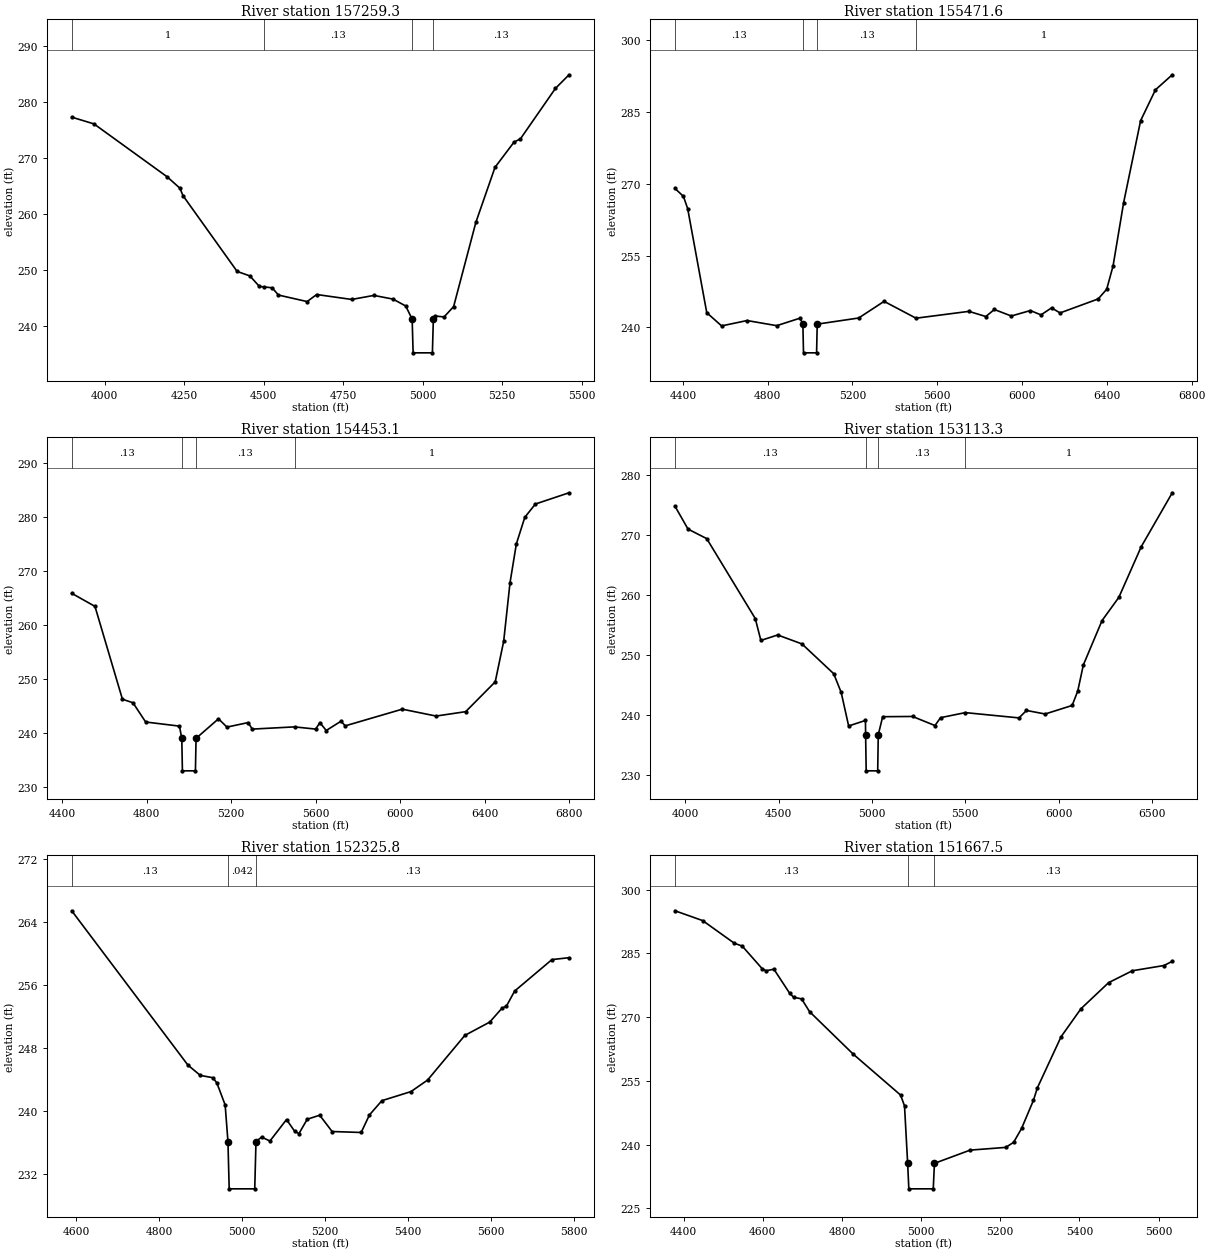
Type RM Length L Ch R = 1 ,157259.3,1787.7,1787.7,1787.7
BEGIN DESCRIPTION:
Sandy Creek 157.0
END DESCRIPTION:
#Sta/Elev= 30
  3896.5   277.3  3966.5  276.09  4196.5  266.65  4236.5  264.62  4246.5  263.27
  4416.5  249.76  4456.5  248.96  4486.5  247.08  4499.9     247  4526.5  246.84
  4546.5  245.54  4636.5  244.38  4666.5  245.64  4776.5  244.76  4846.5  245.48
  4906.5  244.82  4946.5  243.59  4966.7  241.23  4969.7  235.23  5030.3  235.23
  5033.3  241.23    5037  241.81    5067  241.64    5097  243.48    5167  258.53
    5227  268.33    5287  272.85    5307  273.42    5417  282.42  5459.8  284.86
#Mann= 4 , 1 , 0
 3896.50       1       0  4499.9    0.13       0  4966.7   0.042       0
  5033.3    0.13       0
Bank Sta=4966.70,5033.30
Exp/Cntr=0.3,0.1

Type RM Length L Ch R = 1 ,155471.6,1018.5,1018.5,1018.5
BEGIN DESCRIPTION:
Sandy Creek 155.0
END DESCRIPTION:
#Sta/Elev= 30
  4362.9  269.02  4402.9  267.36  4422.9  264.79  4512.9  243.05  4582.9  240.29
  4702.9  241.41  4842.9  240.34  4952.9  241.91  4966.2  240.66  4969.2  234.66
  5030.9  234.66  5033.9  240.66  5229.3  241.94  5349.3  245.42  5499.9   241.9
  5749.3  243.33  5829.3  242.25  5869.3  243.72  5949.3  242.36  6039.3   243.5
  6089.3  242.59  6139.3  244.06  6179.3     243  6359.3  245.93  6399.3  247.96
  6429.3  252.81  6479.3  266.08  6559.3  283.19  6629.3  289.64  6708.6  292.78
#Mann= 4 , 1 , 0
 4362.90    0.13       0  4966.2   0.042       0  5033.9    0.13       0
  5499.9       1       0
Bank Sta=4966.20,5033.90
Exp/Cntr=0.3,0.1

Type RM Length L Ch R = 1 ,154453.1,1339.8,1339.8,1339.8
BEGIN DESCRIPTION:
Sandy Creek 154.0
END DESCRIPTION:
#Sta/Elev= 30
  4445.2  265.85  4555.2  263.44  4685.2  246.29  4735.2  245.63  4795.2  242.08
  4955.2  241.32  4966.2  239.06  4969.2  233.06  5030.8  233.06  5033.8  239.06
    5140  242.67    5180  241.14    5280  241.97    5300  240.77  5499.9  241.18
    5600  240.77    5620  241.96    5650  240.51    5720  242.23    5740  241.37
    6010  244.45    6170  243.18    6310  243.99    6450   249.5    6490     257
    6520  267.81    6550  274.98    6590  279.89    6640  282.34  6799.3  284.42
#Mann= 4 , 1 , 0
 4445.20    0.13       0  4966.2   0.042       0  5033.8    0.13       0
  5499.9       1       0
Bank Sta=4966.20,5033.80
Exp/Cntr=0.3,0.1

Type RM Length L Ch R = 1 ,153113.3,787.5,787.5,787.5
BEGIN DESCRIPTION:
Sandy Creek 153.0
END DESCRIPTION:
#Sta/Elev= 30
  3945.2  274.75  4015.2  270.94  4115.2  269.36  4375.2  256.07  4405.2  252.43
  4495.2  253.34  4625.2  251.85  4795.2   246.9  4835.2  243.79  4875.2  238.21
  4965.2  239.13  4966.1  236.75  4969.1  230.75  5030.8  230.75  5033.8  236.75
  5057.4  239.75  5217.4  239.79  5337.4  238.28  5367.4  239.59  5499.9  240.43
  5787.4  239.55  5827.4  240.79  5927.4   240.2    6072  241.62    6102  244.02
    6132  248.36    6232  255.73    6322  259.59    6442  268.02  6608.1  276.98
#Mann= 4 , 1 , 0
 3945.20    0.13       0  4966.1   0.042       0  5033.8    0.13       0
  5499.9       1       0
Bank Sta=4966.10,5033.80
Exp/Cntr=0.3,0.1

Type RM Length L Ch R = 1 ,152325.8,658.3,658.3,658.3
BEGIN DESCRIPTION:
Sandy Creek 152.5
END DESCRIPTION:
#Sta/Elev= 30
  4589.5  265.43  4869.5  245.84  4899.5  244.52  4929.5  244.23  4939.5  243.56
  4959.5  240.76  4966.2  236.11  4969.2  230.11  5030.8  230.11  5033.8  236.11
  5047.4  236.69  5067.4  236.18  5107.4  238.91  5127.4   237.4  5137.4  237.13
  5157.4  238.95  5187.4  239.46  5217.4  237.39  5287.4  237.27  5307.4   239.5
  5337.4  241.31  5407.4  242.46  5447.4  243.92  5537.4   249.6  5597.4  251.29
  5627.4  253.08  5637.4  253.29  5657.4  255.23  5747.4  259.23  5788.6  259.47
#Mann= 3 , 1 , 0
 4589.50    0.13       0  4966.2   0.042       0  5033.8    0.13       0
Bank Sta=4966.20,5033.80
Exp/Cntr=0.3,0.1

Type RM Length L Ch R = 1 ,151667.5,913.5,913.5,913.5
BEGIN DESCRIPTION:
Sandy Creek 152.0
END DESCRIPTION:
#Sta/Elev= 30
  4378.2     295  4448.2  292.69  4528.2  287.36  4548.2  286.69  4598.2  281.41
  4608.2  280.89  4628.2  281.25  4668.2  275.56  4678.2  274.64  4698.2  274.27
  4718.2  271.27  4828.2   261.3  4948.2  251.64  4958.2  249.09  4966.1  235.57
  4969.1  229.57  5030.8  229.57  5033.8  235.57  5123.9  238.68  5213.9  239.32
  5233.9  240.52  5253.9  243.77  5283.9  250.39  5293.9  253.34  5353.9  265.38
  5403.9  271.94  5473.9  278.09  5533.9  280.89  5613.9  282.12  5634.7  283.11
#Mann= 3 , 1 , 0
 4378.20    0.13       0  4966.1   0.042       0  5033.8    0.13       0
Bank Sta=4966.10,5033.80
Exp/Cntr=0.3,0.1

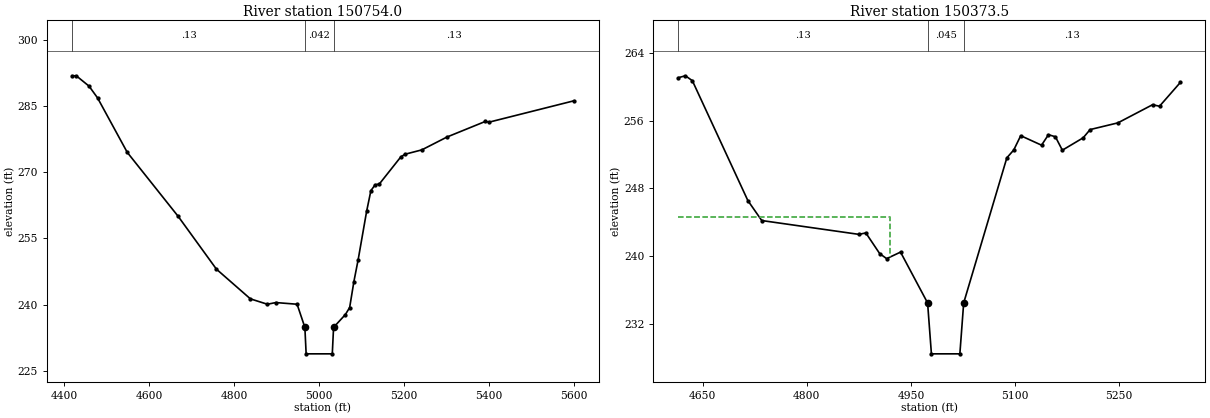
Type RM Length L Ch R = 1 ,150754.0,380.5,380.5,380.5
BEGIN DESCRIPTION:
Sandy Creek 150.5
END DESCRIPTION:
#Sta/Elev= 30
  4417.9  291.83  4427.9  291.82  4457.9  289.48  4477.9  286.82  4547.9  274.47
  4667.9  259.96  4757.9  248.01  4837.9  241.28  4877.9  240.06  4897.9  240.44
  4947.9  240.06  4966.2  234.82  4969.2  228.82  5030.8  228.82  5033.8  234.82
  5061.7  237.73  5071.7  239.32  5081.7  245.21  5091.7  250.14  5111.7  261.14
  5121.7   265.8  5131.7  267.12  5141.7  267.32  5191.7  273.39  5201.7  274.04
  5241.7  275.04  5300.9  277.95  5390.9  281.47  5400.9  281.34  5599.9  286.16
#Mann= 3 , 1 , 0
 4417.90    0.13       0  4966.2   0.042       0  5033.8    0.13       0
Bank Sta=4966.20,5033.80
Exp/Cntr=0.3,0.1

Type RM Length L Ch R = 1 ,150373.5,41,41,41
BEGIN DESCRIPTION:
Upstream Section of Bridge/Culvert/Weir
END DESCRIPTION:
#Sta/Elev= 27
    4615  261.06    4625  261.28    4635   260.7    4715  246.57    4735  244.22
    4875  242.59    4885  242.76    4905  240.32    4915  239.73    4935   240.5
    4974  234.51  4979.5  228.51  5020.5  228.51    5026  234.51  5088.2  251.61
  5098.2  252.54  5108.2  254.22  5138.2   253.1  5148.2  254.34  5158.2  254.09
  5168.2  252.51  5198.2  253.97  5208.2  254.94  5248.2  255.73  5298.2  257.87
  5308.2  257.69  5338.2  260.49
#Mann= 3 , 1 , 0
 4615.00    0.13       0    4974   0.045       0    5026    0.13       0
#XS Ineff= 2 , 0
       0 4920.13  244.67    5069       0  245.98
Bank Sta=4974.00,5026.00
Exp/Cntr=0.5,0.3