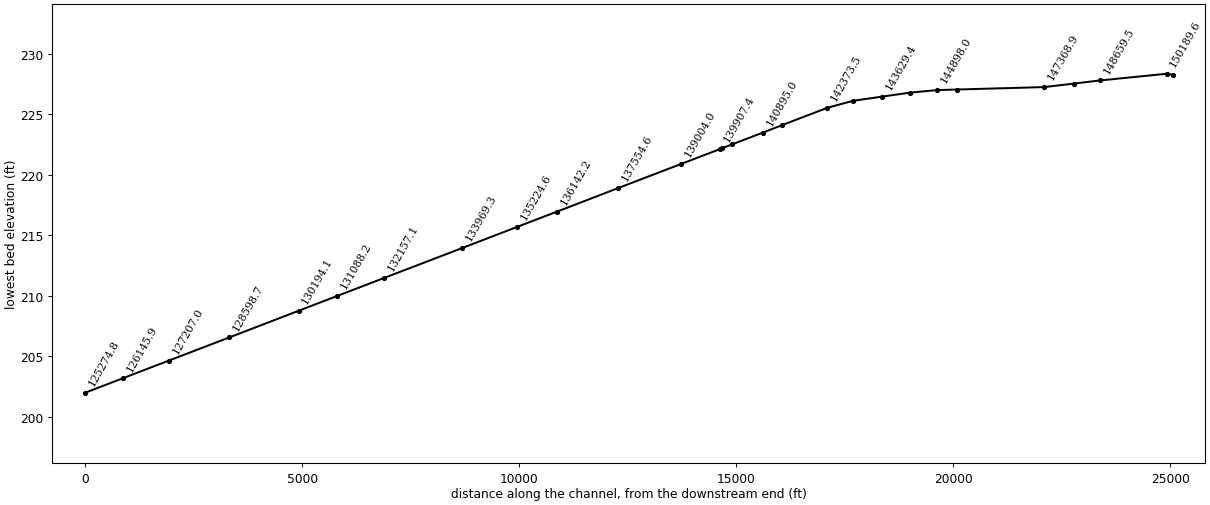
HEC-RAS study 020822_SANDY_CREEK.prj: Sandy Creek

--- 020822_SANDY_CREEK.g01 (geometry) --- (continued)

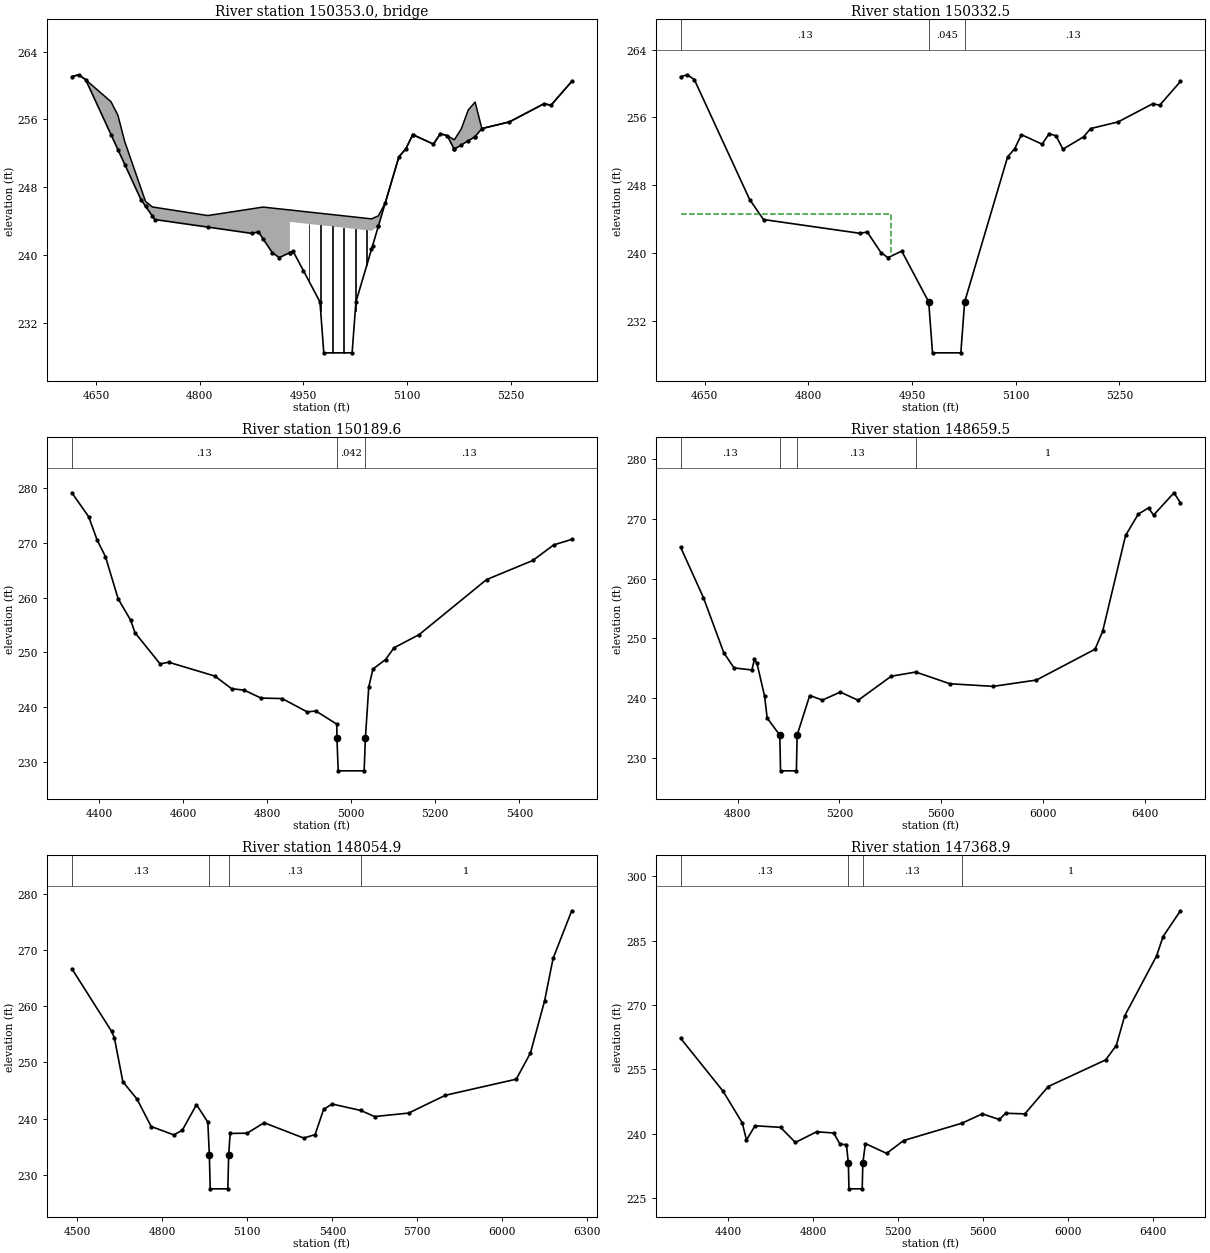
Type RM Length L Ch R = 3 ,150353.0,,,
BEGIN DESCRIPTION:
Person Rd-1-TOR
Structure ID: Person Rd-Bridge
Approximate Survey Structure
END DESCRIPTION:
Bridge Culvert--1,0,-1,-1, 0
Deck Dist Width WeirC Skew NumUp NumDn MinLoCord MaxHiCord MaxSubmerge Is_Ogee
10,21,2.6,,47,47,,,0.95,0,1,1,,
    4615    4625    4635  4671.6  4681.6  4691.6    4715  4721.6  4731.6    4735
  4811.6    4875    4885  4891.6    4905    4915 4930.41  4930.5    4935    4950
    4974  4979.5  5020.5    5026  5048.5    5050 5058.39  5058.5  5068.5  5088.2
  5098.2  5108.2  5108.5  5138.2  5148.2  5158.2  5168.2  5168.5  5178.5  5188.5
  5198.2  5198.5  5208.2  5248.2  5298.2  5308.2  5338.2
  261.05  261.27  260.69   258.1  256.51  253.38  247.89  246.34  245.69  245.65
  244.68  245.47   245.6  245.68  245.56  245.47  245.34  245.34   245.3  245.16
  244.95   244.9  244.54  244.49  244.29  244.34  244.64  244.65  246.19  251.61
  252.54  254.22  254.21   253.1  254.34  254.09  253.61  253.62   254.9  257.12
  258.02  258.05  254.93  255.72  257.86  257.68  260.48
  261.05  261.27  260.69  254.23  252.46  250.69  246.56  245.78  244.61  244.21
  243.32  242.58  242.75  241.94  240.31  239.72  240.31  243.94   243.9  243.76
  243.55   243.5  243.14  243.09  242.89  242.94   243.4  243.43  246.18   251.6
  252.53  254.21   254.2  253.09  254.33  254.08   252.5  252.51     253  253.49
  253.96  253.99  254.93  255.72  257.86  257.68  260.48
    4615    4625    4635  4671.6  4681.6  4691.6    4715  4721.6  4731.6    4735
  4811.6    4875    4885  4891.6    4905    4915 4930.41  4930.5    4935    4950
    4974  4979.5  5020.5    5026  5048.5    5050 5058.39  5058.5  5068.5  5088.2
  5098.2  5108.2  5108.5  5138.2  5148.2  5158.2  5168.2  5168.5  5178.5  5188.5
  5198.2  5198.5  5208.2  5248.2  5298.2  5308.2  5338.2
  261.05  261.27  260.69   258.1  256.51  253.38  247.89  246.34  245.69  245.65
  244.68  245.47   245.6  245.68  245.56  245.47  245.34  245.34   245.3  245.16
  244.95   244.9  244.54  244.49  244.29  244.34  244.64  244.65  246.19  251.61
  252.54  254.22  254.21   253.1  254.34  254.09  253.61  253.62   254.9  257.12
  258.02  258.05  254.93  255.72  257.86  257.68  260.48
  260.81  261.03  260.45  253.99  252.22  250.45  246.32  245.54  244.37  243.97
  243.08  242.34  242.51   241.7  240.07  239.48  240.07   243.7  243.66  243.52
  243.31  243.26   242.9  242.85  242.65   242.7  243.16  243.19  245.94  251.36
  252.29  253.97  253.96  252.85  254.09  253.84  252.26  252.27  252.76  253.25
  253.72  253.75  254.69  255.48  257.62  257.44  260.24
Pier Skew, UpSta & Num, DnSta & Num=,4958.3, 2 ,4958.3, 2 , 0 , 0 , 0 ,,
       1       1
  235.84  244.69
       1       1
   235.6  244.45
Pier Skew, UpSta & Num, DnSta & Num=,4975.0, 2 ,4975.0, 2 , 0 , 0 , 0 ,,
       1       1
  231.86  244.55
       1       1
  231.62  244.31
Pier Skew, UpSta & Num, DnSta & Num=,4991.7, 2 ,4991.7, 2 , 0 , 0 , 0 ,,
       1       1
   227.5   244.4
       1       1
  227.26  244.16
Pier Skew, UpSta & Num, DnSta & Num=,5008.3, 2 ,5008.3, 2 , 0 , 0 , 0 ,,
       1       1
   227.5  244.25
       1       1
  227.26  244.01
Pier Skew, UpSta & Num, DnSta & Num=,5025.0, 2 ,5025.0, 2 , 0 , 0 , 0 ,,
       1       1
  231.86   244.1
       1       1
  231.62  243.86
Pier Skew, UpSta & Num, DnSta & Num=,5041.7, 2 ,5041.7, 2 , 0 , 0 , 0 ,,
       1       1
  237.68  243.95
       1       1
  237.44  243.71
Abutment Skew #Up #Dn=, 2 , 2
 4930.30 4950.00
  243.94  238.19
 4930.30 4950.00
  243.70  237.95
Abutment Skew #Up #Dn=, 2 , 2
 5050.00 5058.59
  241.10  243.40
 5050.00 5058.59
  240.86  243.16
BR Coef= 1 , 1 , 0 ,1.25, 0 ,,,0.8,0,2,0,
Wspro=,,,, 1 ,,,, 0 ,,,, 0 ,,,,-1 ,-1 ,-1 , 0 , 0 , 0 , 0 , 0
BC Design=,, 0 ,, 0 ,,,,,,
BR U #Sta/Elev= 47
    4615  261.05    4625  261.27    4635  260.69  4671.6  254.23  4681.6  252.46
  4691.6  250.69    4715  246.56  4721.6  245.78  4731.6  244.61    4735  244.21
  4811.6  243.32    4875  242.58    4885  242.75  4891.6  241.94    4905  240.31
    4915  239.72 4930.41  240.31  4930.5  240.32    4935  240.49    4950  238.19
    4974   234.5  4979.5   228.5  5020.5   228.5    5026   234.5  5048.5  240.69
    5050   241.1 5058.39   243.4  5058.5  243.43  5068.5  246.18  5088.2   251.6
  5098.2  252.53  5108.2  254.21  5108.5   254.2  5138.2  253.09  5148.2  254.33
  5158.2  254.08  5168.2   252.5  5168.5  252.51  5178.5     253  5188.5  253.49
  5198.2  253.96  5198.5  253.99  5208.2  254.93  5248.2  255.72  5298.2  257.86
  5308.2  257.68  5338.2  260.48
BR U #Mann= 3
 4615.00    0.13    4974   0.045    5026    0.13
BR U Banks=4974.00,5026.00
BR D #Sta/Elev= 47
    4615  260.81    4625  261.03    4635  260.45  4671.6  253.99  4681.6  252.22
  4691.6  250.45    4715  246.32  4721.6  245.54  4731.6  244.37    4735  243.97
  4811.6  243.08    4875  242.34    4885  242.51  4891.6   241.7    4905  240.07
    4915  239.48 4930.41  240.07  4930.5  240.08    4935  240.25    4950  237.95
    4974  234.26  4979.5  228.26  5020.5  228.26    5026  234.26  5048.5  240.45
    5050  240.86 5058.39  243.16  5058.5  243.19  5068.5  245.94  5088.2  251.36
  5098.2  252.29  5108.2  253.97  5108.5  253.96  5138.2  252.85  5148.2  254.09
  5158.2  253.84  5168.2  252.26  5168.5  252.27  5178.5  252.76  5188.5  253.25
  5198.2  253.72  5198.5  253.75  5208.2  254.69  5248.2  255.48  5298.2  257.62
  5308.2  257.44  5338.2  260.24
BR D #Mann= 3
 4615.00    0.13    4974   0.045    5026    0.13
BR D Banks=4974.00,5026.00

Type RM Length L Ch R = 1 ,150332.5,142.9,142.9,142.9
BEGIN DESCRIPTION:
Downstream Section of Bridge/Culvert/Weir
END DESCRIPTION:
#Sta/Elev= 27
    4615  260.81    4625  261.03    4635  260.45    4715  246.32    4735  243.97
    4875  242.34    4885  242.51    4905  240.07    4915  239.48    4935  240.25
    4974  234.26  4979.5  228.26  5020.5  228.26    5026  234.26  5088.2  251.36
  5098.2  252.29  5108.2  253.97  5138.2  252.85  5148.2  254.09  5158.2  253.84
  5168.2  252.26  5198.2  253.72  5208.2  254.69  5248.2  255.48  5298.2  257.62
  5308.2  257.44  5338.2  260.24
#Mann= 3 , 1 , 0
 4615.00    0.13       0    4974   0.045       0    5026    0.13       0
#XS Ineff= 2 , 0
       0 4920.13  244.67    5069       0  245.98
Bank Sta=4974.00,5026.00
Exp/Cntr=0.5,0.3

Type RM Length L Ch R = 1 ,150189.6,1530.1,1530.1,1530.1
BEGIN DESCRIPTION:
Sandy Creek 150.0
END DESCRIPTION:
#Sta/Elev= 30
  4335.7  279.21  4375.7  274.83  4395.7  270.59  4415.7  267.52  4445.7  259.82
  4475.7  255.87  4485.7  253.62  4545.7  247.89  4565.7  248.21  4675.7  245.67
  4715.7  243.36  4745.7  243.09  4785.7  241.64  4835.7  241.56  4895.7   239.1
  4915.7  239.29  4965.7  236.88  4966.1  234.33  4969.1  228.33  5030.8  228.33
  5033.8  234.33  5041.8   243.7  5051.8  246.96  5081.8   248.7  5101.8  250.84
  5161.8  253.27  5321.8  263.32  5431.8  266.82  5481.8  269.68  5524.4  270.67
#Mann= 3 , 1 , 0
 4335.70    0.13       0  4966.1   0.042       0  5033.8    0.13       0
Bank Sta=4966.10,5033.80
Exp/Cntr=0.3,0.1

Type RM Length L Ch R = 1 ,148659.5,604.6,604.6,604.6
BEGIN DESCRIPTION:
Sandy Creek 149.0
END DESCRIPTION:
#Sta/Elev= 30
  4576.4  265.26  4666.4  256.77  4746.4  247.54  4786.4  245.02  4856.4  244.68
  4866.4  246.45  4876.4  245.79  4906.4  240.25  4916.4  236.62  4965.9  233.78
  4968.9  227.78  5031.1  227.78  5034.1  233.78  5083.5   240.4  5133.5  239.63
  5203.5  240.98  5273.5   239.6  5403.5  243.63  5499.9  244.33  5633.5  242.37
  5803.5  241.93  5973.5  242.99  6203.5  248.15  6233.5  251.15  6323.5  267.22
  6373.5  270.79  6413.5  271.82  6433.5  270.62  6513.5  274.36  6538.8  272.67
#Mann= 4 , 1 , 0
 4576.40    0.13       0  4965.9   0.042       0  5034.1    0.13       0
  5499.9       1       0
Bank Sta=4965.90,5034.10
Exp/Cntr=0.3,0.1

Type RM Length L Ch R = 1 ,148054.9,686,686,686
BEGIN DESCRIPTION:
Sandy Creek 148.0
END DESCRIPTION:
#Sta/Elev= 30
  4480.5  266.69  4620.5  255.56  4630.5  254.43  4660.5  246.58  4710.5  243.49
  4760.5  238.61  4840.5  237.12  4870.5  237.96  4920.5   242.5  4960.5  239.38
  4965.9  233.52  4968.9  227.52  5031.1  227.52  5034.1  233.52  5039.2  237.38
  5099.2  237.42  5159.2  239.28  5299.2  236.55  5339.2  237.18  5369.2  241.66
  5399.2  242.61  5499.9  241.47  5549.2  240.38  5669.2     241  5799.2  244.17
  6049.2  247.03  6099.2  251.68  6149.2  260.96  6179.2  268.52  6244.9  276.99
#Mann= 4 , 1 , 0
 4480.50    0.13       0  4965.9   0.042       0  5034.1    0.13       0
  5499.9       1       0
Bank Sta=4965.90,5034.10
Exp/Cntr=0.3,0.1

Type RM Length L Ch R = 1 ,147368.9,2004.7,2004.7,2004.7
BEGIN DESCRIPTION:
Sandy Creek 146.0
END DESCRIPTION:
#Sta/Elev= 30
  4176.9  262.28  4376.9  249.94  4466.9  242.59  4486.9  238.58  4526.9  241.91
  4646.9  241.54  4716.9  238.03  4816.9  240.51  4896.9  240.22  4926.9   237.6
  4956.9  237.53  4965.9  233.23  4968.9  227.23  5031.1  227.23  5034.1  233.23
  5045.9  237.77  5145.9  235.48  5225.9  238.47  5499.9   242.5  5595.9  244.67
  5675.9  243.37  5705.9  244.82  5795.9  244.67  5905.9  251.04  6175.9  257.23
  6225.9  260.58  6265.9  267.52  6415.9  281.47  6445.9  285.93  6527.6  291.93
#Mann= 4 , 1 , 0
 4176.90    0.13       0  4965.9   0.042       0  5034.1    0.13       0
  5499.9       1       0
Bank Sta=4965.90,5034.10
Exp/Cntr=0.3,0.1

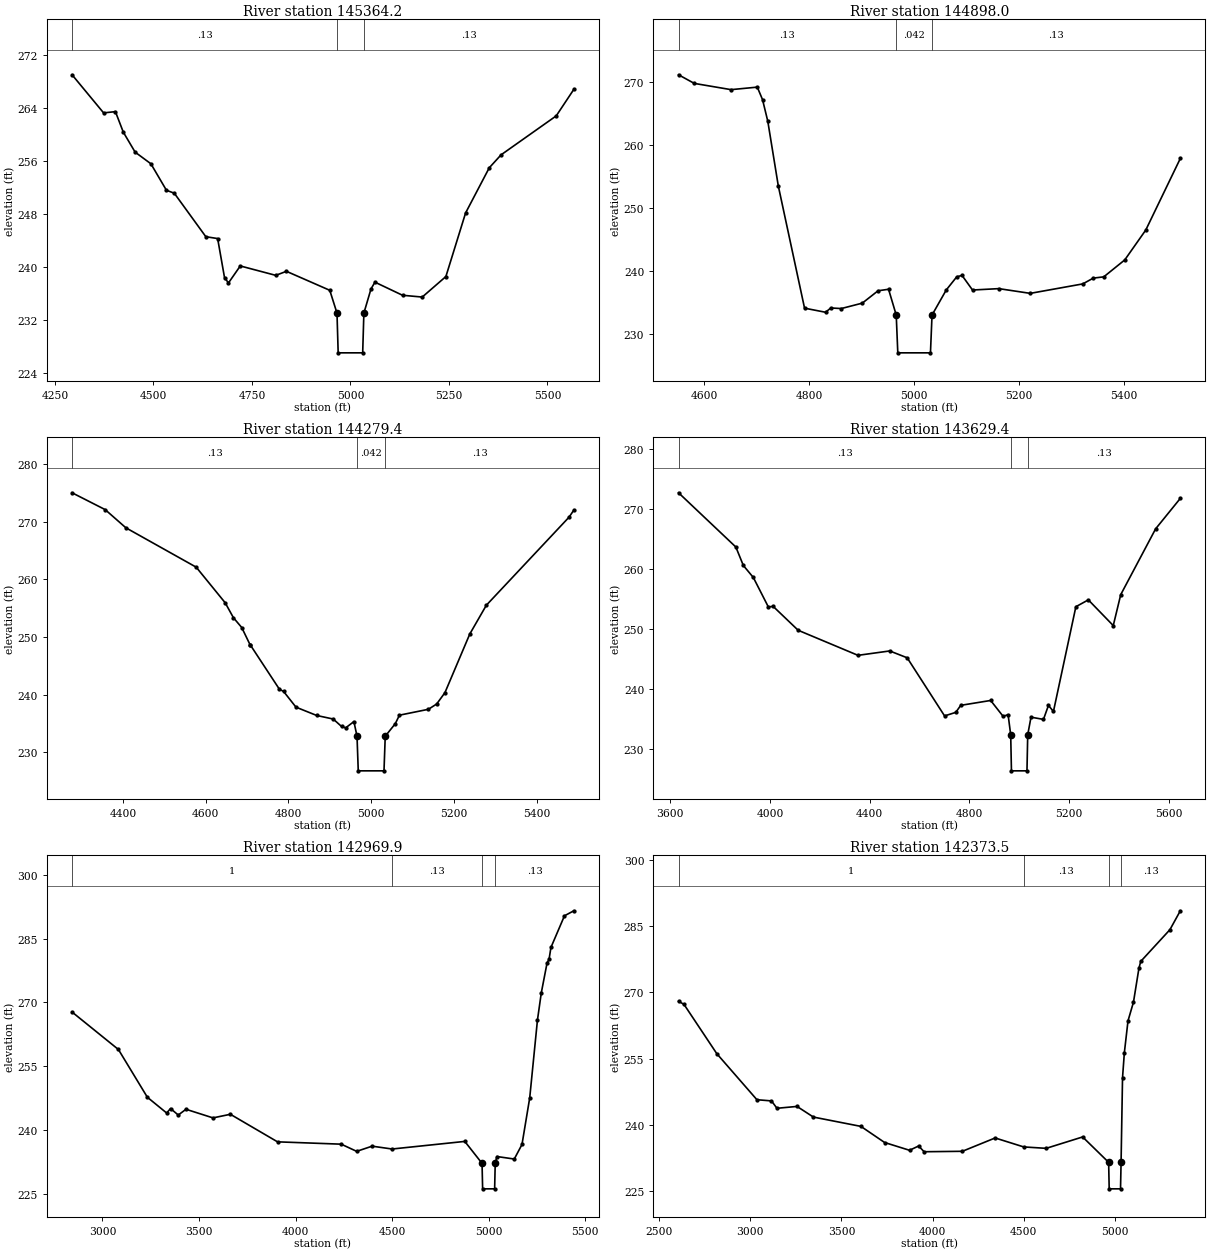
Type RM Length L Ch R = 1 ,145364.2,466.2,466.2,466.2
BEGIN DESCRIPTION:
Sandy Creek 145.5
END DESCRIPTION:
#Sta/Elev= 30
  4293.7  269.05  4373.7  263.29  4403.7  263.48  4423.7  260.38  4453.7  257.36
  4493.7   255.6  4533.1   251.6  4553.1  251.15  4633.1  244.58  4663.1   244.3
  4680.5  238.41  4690.5  237.59  4720.5  240.16  4810.5  238.74  4837.6  239.35
  4947.6  236.48  4965.9  233.03  4968.9  227.03  5031.1  227.03  5034.1  233.03
  5052.2  236.69  5062.2  237.71  5132.2  235.73  5182.2  235.46  5242.2  238.56
  5292.2  248.17  5352.2  254.99  5382.2  256.95  5522.2  262.84  5566.9  266.85
#Mann= 3 , 1 , 0
 4293.70    0.13       0  4965.9   0.042       0  5034.1    0.13       0
Bank Sta=4965.90,5034.10
Exp/Cntr=0.3,0.1

Type RM Length L Ch R = 1 ,144898.0,618.6,618.6,618.6
BEGIN DESCRIPTION:
Sandy Creek 145.0
END DESCRIPTION:
#Sta/Elev= 30
  4551.3  271.11  4581.3  269.74  4651.3  268.75  4701.3  269.15  4711.3  267.16
  4721.3  263.73  4741.3  253.47  4791.3  234.07  4831.3  233.42  4841.3   234.1
  4861.3  234.01  4901.3  234.87  4931.3  236.83  4951.3  237.07  4965.9  232.98
  4968.9  226.98  5031.1  226.98  5034.1  232.98  5061.2  236.96  5081.2  239.05
  5091.2  239.27  5111.2  236.95  5161.2  237.17  5221.2  236.42  5321.2  237.92
  5341.2  238.84  5361.2  239.04  5401.2  241.73  5441.2  246.47    5507  257.83
#Mann= 3 , 1 , 0
 4551.30    0.13       0  4965.9   0.042       0  5034.1    0.13       0
Bank Sta=4965.90,5034.10
Exp/Cntr=0.3,0.1

Type RM Length L Ch R = 1 ,144279.4,650,650,650
BEGIN DESCRIPTION:
Sandy Creek 141.7
END DESCRIPTION:
#Sta/Elev= 30
  4277.3  274.98  4357.3  272.06  4407.3  268.91  4577.3  262.08  4647.3  255.91
  4667.3  253.31  4687.3  251.62  4707.3  248.65  4708.4  248.56  4778.4  240.91
  4788.4  240.54  4818.4  237.81  4868.4  236.37  4908.4  235.75  4928.4  234.47
  4938.4  234.22  4958.4  235.31  4965.9  232.77  4968.9  226.77  5031.1  226.77
  5034.1  232.77  5058.4  234.95  5068.4  236.42  5138.4  237.44  5158.4  238.36
  5178.4  240.33  5238.4  250.49  5278.4  255.48  5478.4  270.76  5489.9  271.98
#Mann= 3 , 1 , 0
 4277.30    0.13       0  4965.9   0.042       0  5034.1    0.13       0
Bank Sta=4965.90,5034.10
Exp/Cntr=0.3,0.1

Type RM Length L Ch R = 1 ,143629.4,659.5,659.5,659.5
BEGIN DESCRIPTION:
Sandy Creek 144.5
END DESCRIPTION:
#Sta/Elev= 30
  3633.2  272.71  3863.2  263.68  3893.2  260.61  3933.2  258.62  3993.2  253.74
  4013.2  253.79  4113.2  249.83  4353.2  245.66  4480.6  246.39  4550.6  245.25
  4700.6  235.58  4745.5  236.17  4765.5  237.34  4885.5  238.15  4935.5  235.51
  4955.5  235.79  4965.9  232.44  4968.9  226.44  5031.2  226.44  5034.2  232.44
  5047.4  235.37  5097.4     235  5117.4  237.33  5137.4  236.32  5227.4  253.75
  5277.4  254.89  5377.4  250.61  5407.4  255.76  5547.4  266.71  5646.5  271.78
#Mann= 3 , 1 , 0
 3633.20    0.13       0  4965.9   0.042       0  5034.2    0.13       0
Bank Sta=4965.90,5034.20
Exp/Cntr=0.3,0.1

Type RM Length L Ch R = 1 ,142969.9,596.4,596.4,596.4
BEGIN DESCRIPTION:
Sandy Creek 144.0
END DESCRIPTION:
#Sta/Elev= 30
  2842.4  267.74  3082.4  258.92  3232.4  247.67  3332.4  243.96  3352.4  245.02
  3392.4  243.48  3432.4  244.84  3572.4  242.81  3662.4  243.66  3906.5  237.17
  4236.5  236.62  4316.5  234.93  4396.5  236.15  4499.9  235.48  4876.5  237.27
  4965.9   232.1  4968.9   226.1  5031.1   226.1  5034.1   232.1  5042.8  233.71
  5132.8  233.12  5172.8  236.55  5212.8  247.53  5252.8  265.83  5272.8  272.27
  5302.8  279.34  5312.8  280.12  5322.8  282.96  5392.8  290.41  5441.4  291.59
#Mann= 4 , 1 , 0
 2842.40       1       0  4499.9    0.13       0  4965.9   0.042       0
  5034.1    0.13       0
Bank Sta=4965.90,5034.10
Exp/Cntr=0.3,0.1

Type RM Length L Ch R = 1 ,142373.5,1047.1,1047.1,1047.1
BEGIN DESCRIPTION:
Sandy Creek 141.5
END DESCRIPTION:
#Sta/Elev= 30
  2606.1     268  2636.1  267.28  2816.1  256.12  3036.1   245.7  3116.1  245.43
  3146.1  243.76  3256.1  244.18  3346.1  241.77  3606.8  239.66  3736.8  236.01
  3873.4  234.25  3923.4  235.22  3953.4  233.92  4163.2  234.02  4343.2  237.04
  4499.9  235.01  4623.2  234.69  4823.2  237.27  4965.9  231.52  4968.9  225.52
  5031.1  225.52  5034.1  231.52  5042.1  250.69  5052.1  256.34  5072.1  263.55
  5102.1  267.79  5132.1  275.47  5142.1  277.02  5302.1   284.2  5359.2  288.48
#Mann= 4 , 1 , 0
 2606.10       1       0  4499.9    0.13       0  4965.9   0.042       0
  5034.1    0.13       0
Bank Sta=4965.90,5034.10
Exp/Cntr=0.3,0.1

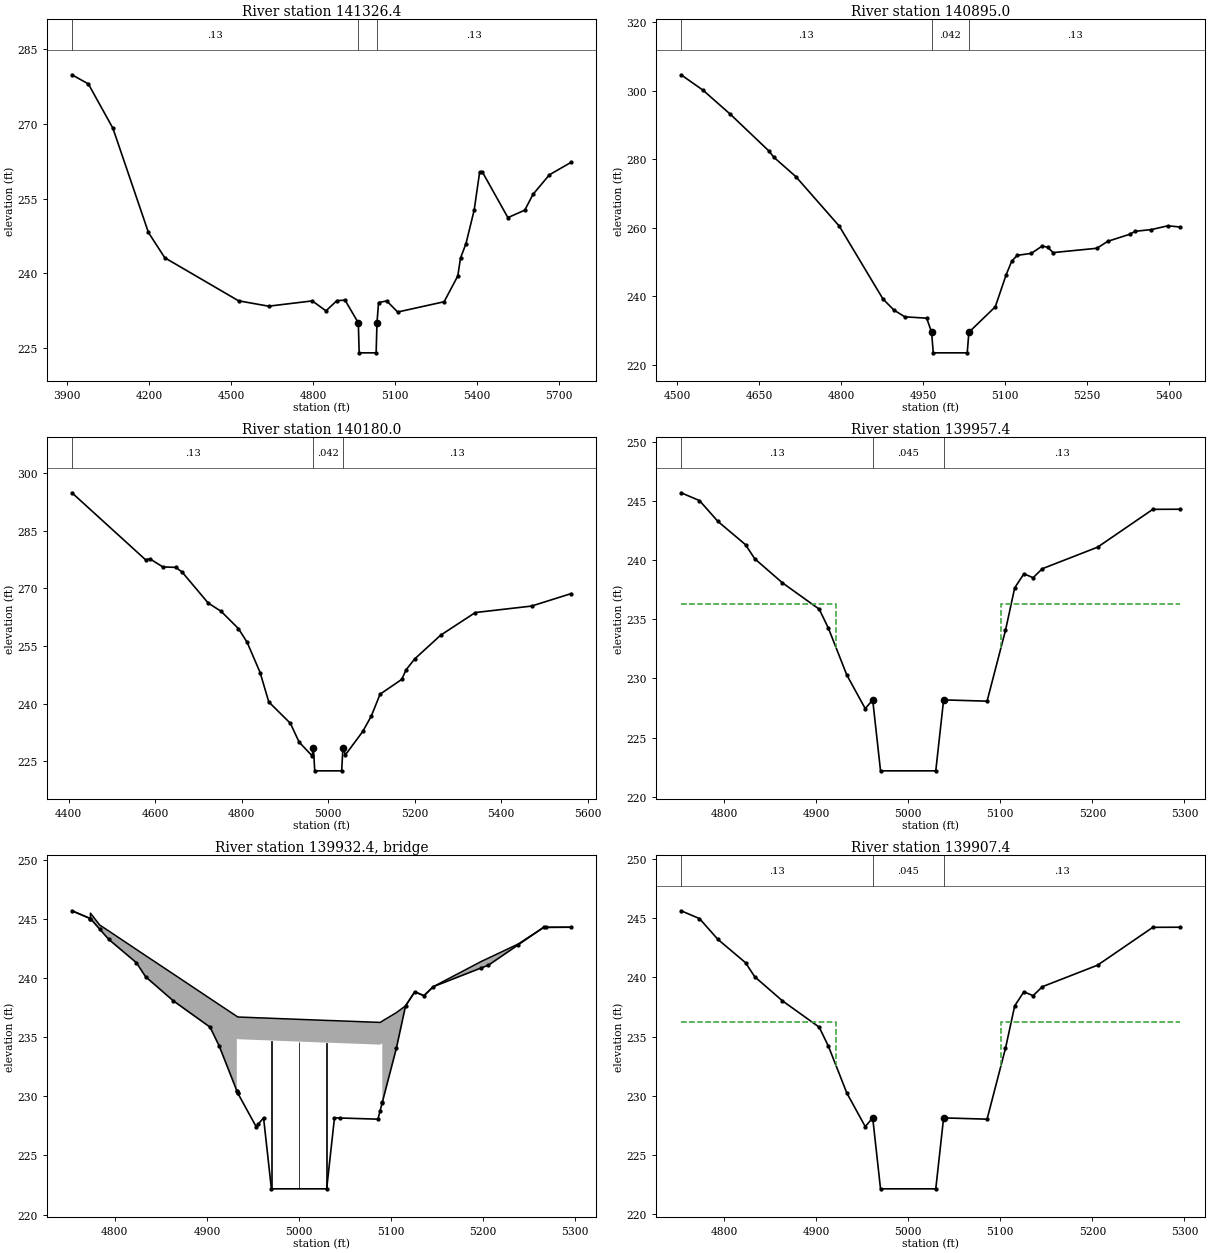
Type RM Length L Ch R = 1 ,141326.4,431.4,431.4,431.4
BEGIN DESCRIPTION:
Sandy Creek 141.0
END DESCRIPTION:
#Sta/Elev= 30
  3917.3  279.87  3977.3  278.04  4067.3  269.14  4197.3  248.23  4257.3  243.15
  4527.3  234.52  4637.3  233.44  4797.3   234.5  4847.3   232.5  4887.3  234.55
  4917.3  234.65  4965.9  230.08  4968.9  224.08  5031.1  224.08  5034.1  230.08
    5040  234.18    5070  234.49    5110  232.27    5280  234.33    5330   239.5
    5340   243.1    5360  245.99    5390  252.72    5410  260.32    5420  260.37
  5513.5  251.21  5575.4  252.71  5605.4  255.88  5665.4   259.8  5745.7  262.33
#Mann= 3 , 1 , 0
 3917.30    0.13       0  4965.9   0.042       0  5034.1    0.13       0
Bank Sta=4965.90,5034.10
Exp/Cntr=0.3,0.1

Type RM Length L Ch R = 1 ,140895.0,715,715,715
BEGIN DESCRIPTION:
Sandy Creek 140.0
END DESCRIPTION:
#Sta/Elev= 30
  4507.4  304.64  4547.4  300.16  4597.4  293.14  4667.4  282.51  4677.4  280.54
  4717.4  274.92  4796.9  260.47  4876.9  239.19  4896.9  235.97  4916.9  233.99
  4956.9   233.6  4965.9  229.48  4968.9  223.48  5031.1  223.48  5034.1  229.48
  5082.4  236.91  5102.4   246.3  5112.4  250.18  5122.4  251.93  5148.3  252.51
  5168.3  254.66  5178.3  254.31  5188.3  252.74  5268.3     254  5288.3  256.03
  5328.3  258.08  5338.3  258.95  5368.3  259.46  5398.3  260.56  5421.3   260.2
#Mann= 3 , 1 , 0
 4507.40    0.13       0  4965.9   0.042       0  5034.1    0.13       0
Bank Sta=4965.90,5034.10
Exp/Cntr=0.3,0.1

Type RM Length L Ch R = 1 ,140180.0,222.6,222.6,222.6
BEGIN DESCRIPTION:
Sandy Creek 139.5
END DESCRIPTION:
#Sta/Elev= 30
  4407.9  294.93  4577.9  277.49  4587.9  277.73  4617.9  275.62  4647.9   275.5
  4662.7  274.25  4722.7  266.21  4752.7  264.04  4792.7  259.54  4812.7  255.98
  4842.7  248.11  4862.7  240.45  4912.7  234.87  4932.7  230.01  4962.7  226.42
  4965.9   228.5  4968.9   222.5  5031.1   222.5  5034.1   228.5  5039.9  226.68
  5079.9  232.76  5099.9  236.84  5119.9  242.47  5169.9  246.31  5179.9  248.81
  5199.9  251.65  5259.9  257.84  5339.9  263.73  5469.9  265.42  5561.8  268.68
#Mann= 3 , 1 , 0
 4407.90    0.13       0  4965.9   0.042       0  5034.1    0.13       0
Bank Sta=4965.90,5034.10
Exp/Cntr=0.3,0.1

Type RM Length L Ch R = 1 ,139957.4,50,50,50
BEGIN DESCRIPTION:
Upstream Section of Bridge/Culvert/Weir
END DESCRIPTION:
#Sta/Elev= 23
  4753.4   245.7  4773.4  245.04  4793.4  243.28  4823.4  241.31  4833.4  240.12
  4863.4  238.09  4903.4  235.86  4913.4  234.25  4933.4  230.29  4953.4  227.45
  4961.5  228.19    4970  222.19    5030  222.19  5038.5  228.19  5085.7  228.08
  5105.7  234.07  5115.7  237.66  5125.7  238.85  5135.7  238.52  5145.7  239.28
  5205.7   241.1  5265.7   244.3  5295.7  244.31
#Mann= 3 , 1 , 0
 4753.40    0.13       0  4961.5   0.045       0  5038.5    0.13       0
#XS Ineff= 2 , 0
       0    4922  236.26 5100.66       0  236.26
Bank Sta=4961.50,5038.50
Exp/Cntr=0.5,0.3

Type RM Length L Ch R = 3 ,139932.4,,,
BEGIN DESCRIPTION:
Laurel Mill Rd-2-TOR
Structure ID: Laurel Mill-Centerville Rd-Bridge
Approximate Survey Structure
END DESCRIPTION:
Bridge Culvert--1,0,-1,-1, 0
Deck Dist Width WeirC Skew NumUp NumDn MinLoCord MaxHiCord MaxSubmerge Is_Ogee
10,30,2.6,,36,36,,,0.95,0,1,1,,
  4753.4  4773.4  4773.5  4783.5  4793.4  4823.4  4833.4  4863.4  4903.4  4913.4
 4932.41  4932.5  4933.4  4933.5  4953.4  4955.5  4961.5    4970    5030  5038.5
  5044.5  5085.7    5088 5090.39  5090.5  5105.7  5115.7  5125.7  5135.7  5145.7
    5198  5205.7    5238  5265.7    5268  5295.7
  245.69  245.03  245.49  244.49  243.98  242.42   241.9  240.35  238.27  237.75
  236.77  236.76  236.72  236.71  236.65  236.64  236.63   236.6  236.42   236.4
  236.38  236.26  236.25  236.36  236.37  237.08  237.65  238.84  238.51  239.27
  241.41  241.69  242.88  244.29  244.29   244.3
  245.69  245.03  245.02  244.14  243.27   241.3  240.11  238.08  235.85  234.24
  230.48  234.88  234.84  234.83  234.77  234.76  234.75  234.72  234.54  234.52
   234.5  234.38  234.37  234.48  229.51  234.06  237.65  238.84  238.51  239.27
  240.86  241.09  242.81  244.29  244.29   244.3
  4753.4  4773.4  4773.5  4783.5  4793.4  4823.4  4833.4  4863.4  4903.4  4913.4
 4932.41  4932.5  4933.4  4933.5  4953.4  4955.5  4961.5    4970    5030  5038.5
  5044.5  5085.7    5088 5090.39  5090.5  5105.7  5115.7  5125.7  5135.7  5145.7
    5198  5205.7    5238  5265.7    5268  5295.7
  245.67  245.01  245.49  244.49  243.98  242.42   241.9  240.35  238.27  237.75
  236.77  236.76  236.72  236.71  236.65  236.64  236.63   236.6  236.42   236.4
  236.38  236.26  236.25  236.36  236.37  237.08  237.64  238.83  238.49  239.26
  241.41  241.69  242.88  244.28  244.28  244.28
  245.65  244.99  244.98   244.1  243.23  241.26  240.07  238.04  235.81   234.2
  230.44  234.84   234.8  234.79  234.73  234.72  234.71  234.68   234.5  234.48
  234.46  234.34  234.33  234.44  229.47  234.02  237.61   238.8  238.47  239.23
  240.82  241.05  242.77  244.25  244.25  244.26
Pier Skew, UpSta & Num, DnSta & Num=,4970.3, 2 ,4970.3, 2 , 0 , 0 , 0 ,,
       1       1
  221.18  235.72
       1       1
  221.14  235.68
Pier Skew, UpSta & Num, DnSta & Num=,5000.0, 2 ,5000.0, 2 , 0 , 0 , 0 ,,
       1       1
  221.18  235.63
       1       1
  221.14  235.59
Pier Skew, UpSta & Num, DnSta & Num=,5029.6, 2 ,5029.6, 2 , 0 , 0 , 0 ,,
       1       1
  221.18  235.54
       1       1
  221.14   235.5
Abutment Skew #Up #Dn=, 2 , 2
 4932.30 4955.50
  234.88  227.63
 4932.30 4955.50
  234.84  227.59
Abutment Skew #Up #Dn=, 2 , 2
 5044.50 5090.59
  228.17  234.48
 5044.50 5090.59
  228.13  234.44
BR Coef= 1 , 1 , 0 ,1.25, 0 ,,,0.8,0,2,0,
Wspro=,,,, 1 ,,,, 0 ,,,, 0 ,,,,-1 ,-1 ,-1 , 0 , 0 , 0 , 0 , 0
BC Design=,, 0 ,, 0 ,,,,,,
BR U #Sta/Elev= 36
  4753.4  245.69  4773.4  245.03  4773.5  245.02  4783.5  244.14  4793.4  243.27
  4823.4   241.3  4833.4  240.11  4863.4  238.08  4903.4  235.85  4913.4  234.24
 4932.41  230.48  4932.5  230.46  4933.4  230.28  4933.5  230.27  4953.4  227.44
  4955.5  227.63  4961.5  228.18    4970  222.18    5030  222.18  5038.5  228.18
  5044.5  228.17  5085.7  228.07    5088  228.76 5090.39  229.47  5090.5  229.51
  5105.7  234.06  5115.7  237.65  5125.7  238.84  5135.7  238.51  5145.7  239.27
    5198  240.86  5205.7  241.09    5238  242.81  5265.7  244.29    5268  244.29
  5295.7   244.3
BR U #Mann= 3
 4753.40    0.13  4961.5   0.045  5038.5    0.13
BR U Banks=4961.50,5038.50
BR D #Sta/Elev= 36
  4753.4  245.65  4773.4  244.99  4773.5  244.98  4783.5   244.1  4793.4  243.23
  4823.4  241.26  4833.4  240.07  4863.4  238.04  4903.4  235.81  4913.4   234.2
 4932.41  230.44  4932.5  230.42  4933.4  230.24  4933.5  230.23  4953.4   227.4
  4955.5  227.59  4961.5  228.14    4970  222.14    5030  222.14  5038.5  228.14
  5044.5  228.13  5085.7  228.03    5088  228.72 5090.39  229.43  5090.5  229.47
  5105.7  234.02  5115.7  237.61  5125.7   238.8  5135.7  238.47  5145.7  239.23
    5198  240.82  5205.7  241.05    5238  242.77  5265.7  244.25    5268  244.25
  5295.7  244.26
BR D #Mann= 3
 4753.40    0.13  4961.5   0.045  5038.5    0.13
BR D Banks=4961.50,5038.50

Type RM Length L Ch R = 1 ,139907.4,903.4,903.4,903.4
BEGIN DESCRIPTION:
Downstream Section of Bridge/Culvert/Weir
END DESCRIPTION:
#Sta/Elev= 23
  4753.4  245.63  4773.4  244.97  4793.4  243.21  4823.4  241.24  4833.4  240.05
  4863.4  238.02  4903.4  235.79  4913.4  234.18  4933.4  230.22  4953.4  227.38
  4961.5  228.12    4970  222.12    5030  222.12  5038.5  228.12  5085.7  228.01
  5105.7     234  5115.7  237.59  5125.7  238.78  5135.7  238.45  5145.7  239.21
  5205.7  241.03  5265.7  244.23  5295.7  244.24
#Mann= 3 , 1 , 0
 4753.40    0.13       0  4961.5   0.045       0  5038.5    0.13       0
#XS Ineff= 2 , 0
       0    4922  236.26 5100.66       0  236.26
Bank Sta=4961.50,5038.50
Exp/Cntr=0.5,0.3

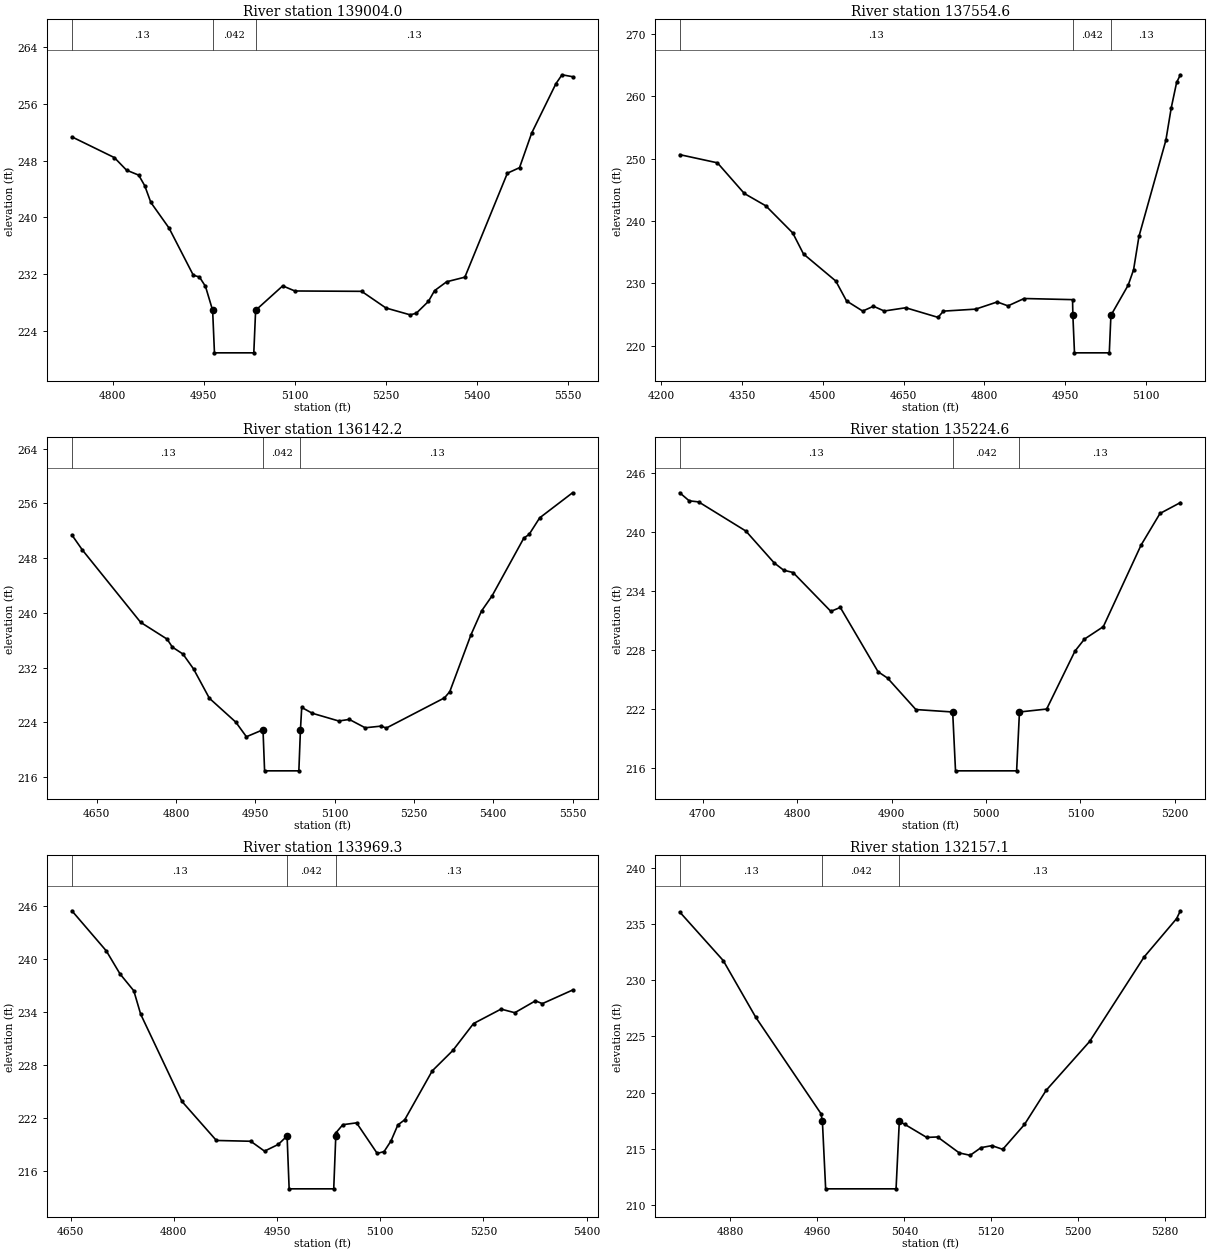
Type RM Length L Ch R = 1 ,139004.0,1449.4,1449.4,1449.4
BEGIN DESCRIPTION:
Sandy Creek 139.0
END DESCRIPTION:
#Sta/Elev= 30
  4732.8  251.36  4802.8  248.43  4822.8  246.66  4842.8  245.96  4852.8  244.46
  4862.8  242.11  4892.8  238.49  4932.8  231.83  4942.8  231.59  4952.8  230.26
  4964.6  226.88  4967.6  220.88  5032.4  220.88  5035.4  226.88    5080  230.33
    5100  229.61    5210  229.56    5250  227.21    5290  226.24    5300  226.47
    5320  228.14    5330  229.65    5350  230.91    5380  231.56    5450  246.23
    5470  247.01    5490  251.89    5530  258.87    5540  260.12  5557.3  259.85
#Mann= 3 , 1 , 0
 4732.80    0.13       0  4964.6   0.042       0  5035.4    0.13       0
Bank Sta=4964.60,5035.40
Exp/Cntr=0.3,0.1

Type RM Length L Ch R = 1 ,137554.6,1412.4,1412.4,1412.4
BEGIN DESCRIPTION:
Sandy Creek 137.0
END DESCRIPTION:
#Sta/Elev= 30
  4234.1  250.63  4304.1  249.32  4354.1  244.41  4394.1  242.43  4444.1  238.09
  4464.1  234.72  4524.1  230.39  4544.1   227.2  4574.1  225.58  4594.1  226.35
  4614.1  225.59  4654.1  226.11  4714.1  224.57  4724.1  225.57  4784.1  225.89
  4824.1  227.04  4844.1  226.41  4874.1  227.59  4964.1  227.41  4964.7  224.89
  4967.7  218.89  5032.4  218.89  5035.4  224.89  5067.5  229.73  5077.5  232.19
  5087.5  237.53  5137.5  252.92  5147.5  258.12  5157.5  262.19  5164.5  263.42
#Mann= 3 , 1 , 0
 4234.10    0.13       0  4964.7   0.042       0  5035.4    0.13       0
Bank Sta=4964.70,5035.40
Exp/Cntr=0.3,0.1

Type RM Length L Ch R = 1 ,136142.2,917.6,917.6,917.6
BEGIN DESCRIPTION:
Sandy Creek 136.0
END DESCRIPTION:
#Sta/Elev= 30
  4603.2  251.39  4623.2  249.18  4733.2  238.63  4783.2  236.18  4793.2  235.01
  4813.2     234  4833.2  231.83  4863.2  227.54  4913.2  224.05  4933.2  221.92
  4964.6  222.94  4967.6  216.94  5032.4  216.94  5035.4  222.94  5037.8   226.2
  5057.8  225.35  5107.8  224.22  5127.8  224.45  5157.8  223.23  5187.8  223.47
  5197.8  223.19  5307.8   227.6  5317.8  228.51  5357.8   236.8  5377.8  240.28
  5397.8   242.5  5457.8  250.93  5467.8  251.47  5487.8  253.89  5549.9  257.55
#Mann= 3 , 1 , 0
 4603.20    0.13       0  4964.6   0.042       0  5035.4    0.13       0
Bank Sta=4964.60,5035.40
Exp/Cntr=0.3,0.1

Type RM Length L Ch R = 1 ,135224.6,1255.3,1255.3,1255.3
BEGIN DESCRIPTION:
Sandy Creek 135.0
END DESCRIPTION:
#Sta/Elev= 23
  4675.7  244.03  4685.7  243.21  4695.7   243.1  4745.7  240.13  4775.7  236.88
  4785.7  236.14  4795.7   235.9  4835.7  231.94  4845.7  232.34  4885.7  225.78
  4895.7  225.14  4925.7  221.93  4964.7  221.68  4967.7  215.68  5032.4  215.68
  5035.4  221.68  5064.2  221.98  5094.2  227.89  5104.2  229.11  5124.2  230.38
  5164.2   238.7  5184.2  241.92  5205.8  243.03
#Mann= 3 , 1 , 0
 4675.70    0.13       0  4964.7   0.042       0  5035.4    0.13       0
Bank Sta=4964.70,5035.40
Exp/Cntr=0.3,0.1

Type RM Length L Ch R = 1 ,133969.3,1812.2,1812.2,1812.2
BEGIN DESCRIPTION:
Sandy Creek 134.0
END DESCRIPTION:
#Sta/Elev= 30
  4651.8  245.51  4701.8  240.96  4721.8  238.34  4741.8  236.43  4751.8  233.77
  4811.8  223.87  4861.8  219.44  4911.8  219.35  4931.8  218.23  4951.8  218.99
  4964.6  219.95  4967.6  213.95  5032.4  213.95  5035.4  219.95  5035.6  220.31
  5045.6  221.23  5065.6  221.44  5095.6  217.97  5105.6  218.18  5115.6  219.38
  5125.6   221.2  5135.6  221.79  5175.6  227.34  5205.6  229.66  5235.6  232.71
  5275.6  234.35  5295.6  233.94  5325.6  235.29  5335.6  234.97  5379.5  236.51
#Mann= 3 , 1 , 0
 4651.80    0.13       0  4964.6   0.042       0  5035.4    0.13       0
Bank Sta=4964.60,5035.40
Exp/Cntr=0.3,0.1

Type RM Length L Ch R = 1 ,132157.1,1068.9,1068.9,1068.9
BEGIN DESCRIPTION:
Sandy Creek 132.0
END DESCRIPTION:
#Sta/Elev= 22
  4833.3  236.06  4873.3  231.75  4903.3   226.7  4963.3  218.14  4964.6  217.46
  4967.6  211.46  5032.4  211.46  5035.4  217.46  5040.6  217.18  5060.6  216.03
  5070.6  216.07  5090.6  214.65  5100.6  214.44  5110.6  215.12  5120.6   215.3
  5130.6  214.97  5150.6  217.18  5170.6  220.22  5210.6  224.56  5260.6  232.05
  5290.6  235.47  5294.1  236.17
#Mann= 3 , 1 , 0
 4833.30    0.13       0  4964.6   0.042       0  5035.4    0.13       0
Bank Sta=4964.60,5035.40
Exp/Cntr=0.3,0.1

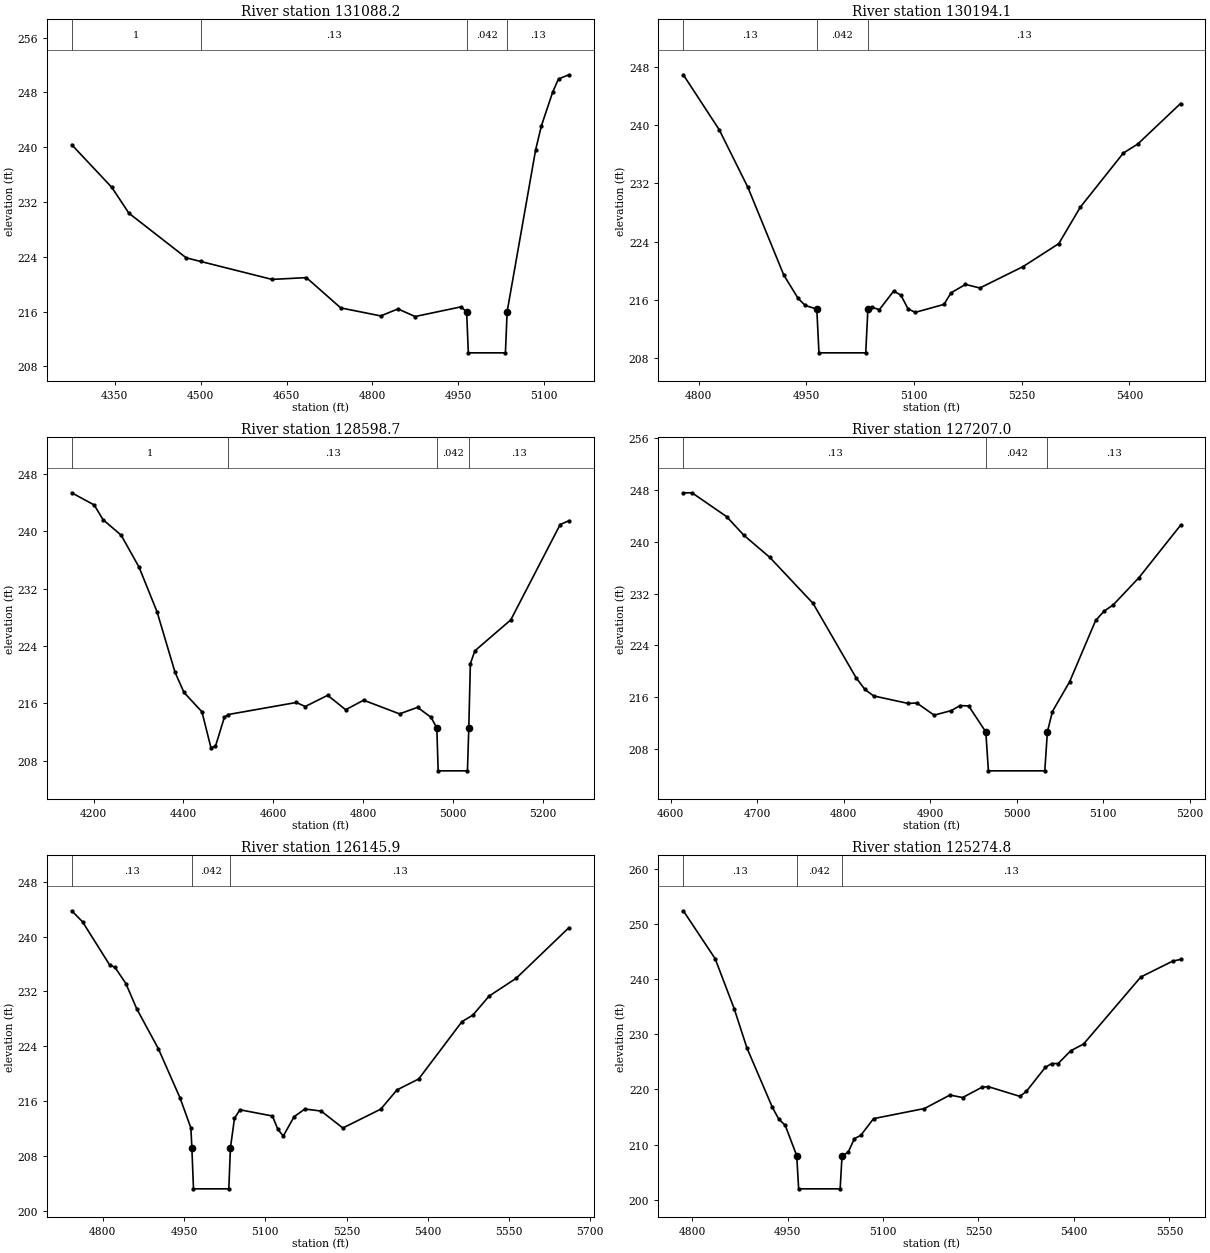
Type RM Length L Ch R = 1 ,131088.2,894.1,894.1,894.1
BEGIN DESCRIPTION:
Sandy Creek 131.0
END DESCRIPTION:
#Sta/Elev= 22
  4274.6  240.37  4344.6  234.15  4374.6  230.37  4474.6  223.86  4499.9  223.33
  4624.6  220.71  4684.6  220.97  4744.6  216.55  4814.6  215.38  4844.6   216.4
  4874.6  215.29  4954.6   216.7  4964.5  215.99  4964.6  216.08  4967.6  209.99
  5032.4  209.99  5035.4  215.99  5085.2  239.62  5095.2  243.11  5115.2   248.1
  5125.2  249.98  5143.4  250.58
#Mann= 4 , 1 , 0
 4274.60       1       0  4499.9    0.13       0  4964.5   0.042       0
  5035.4    0.13       0
Bank Sta=4964.50,5035.40
Exp/Cntr=0.3,0.1

Type RM Length L Ch R = 1 ,130194.1,1595.4,1595.4,1595.4
BEGIN DESCRIPTION:
Sandy Creek 130.0
END DESCRIPTION:
#Sta/Elev= 26
  4778.4  246.88  4828.4  239.35  4868.4  231.44  4918.4  219.42  4938.4  216.22
  4948.4  215.25  4964.4  214.76  4967.4  208.76  5032.6  208.76  5035.6  214.76
  5041.6  214.99  5051.6  214.68  5071.6  217.24  5081.6  216.66  5091.6  214.78
  5101.6  214.31  5141.6   215.4  5151.6     217  5171.6  218.14  5191.6  217.65
  5251.6  220.57  5301.6  223.73  5331.6  228.73  5391.6  236.15  5411.6  237.38
  5471.3  242.94
#Mann= 3 , 1 , 0
 4778.40    0.13       0  4964.4   0.042       0  5035.6    0.13       0
Bank Sta=4964.40,5035.60
Exp/Cntr=0.3,0.1

Type RM Length L Ch R = 1 ,128598.7,1391.7,1391.7,1391.7
BEGIN DESCRIPTION:
Sandy Creek 128.0
END DESCRIPTION:
#Sta/Elev= 30
  4151.4  245.37  4201.4  243.67  4221.4   241.6  4261.4  239.46  4301.4  234.98
  4341.4  228.76  4381.4  220.33  4401.4   217.5  4441.4   214.8  4461.4  209.79
  4471.4  209.97  4491.4  214.05  4499.9  214.42  4651.4   216.1  4671.4  215.54
  4721.4   217.1  4761.4  215.09  4801.4  216.42  4881.4  214.51  4921.4  215.42
  4951.4  214.04  4964.4  212.56  4967.4  206.56  5032.6  206.56  5035.6  212.56
  5039.1  221.51  5049.1  223.31  5129.1  227.63  5239.1  240.94  5258.6  241.47
#Mann= 4 , 1 , 0
 4151.40       1       0  4499.9    0.13       0  4964.4   0.042       0
  5035.6    0.13       0
Bank Sta=4964.40,5035.60
Exp/Cntr=0.3,0.1

Type RM Length L Ch R = 1 ,127207.0,1061.1,1061.1,1061.1
BEGIN DESCRIPTION:
Sandy Creek 127.0
END DESCRIPTION:
#Sta/Elev= 26
  4614.6  247.54  4624.6  247.55  4664.6  243.88  4684.6     241  4714.6  237.58
  4764.6  230.49  4814.6  218.96  4824.6  217.21  4834.6  216.21  4874.6  215.05
  4884.6  215.12  4904.6  213.24  4924.6  213.95  4934.6  214.72  4944.6  214.66
  4964.4  210.65  4967.4  204.65  5032.6  204.65  5035.6  210.65  5041.4   213.8
  5061.4  218.42  5091.4  227.85  5101.4  229.32  5111.4  230.21  5141.4  234.44
  5189.6  242.54
#Mann= 3 , 1 , 0
 4614.60    0.13       0  4964.4   0.042       0  5035.6    0.13       0
Bank Sta=4964.40,5035.60
Exp/Cntr=0.3,0.1

Type RM Length L Ch R = 1 ,126145.9,871.1,871.1,871.1
BEGIN DESCRIPTION:
Sandy Creek 126.0
END DESCRIPTION:
#Sta/Elev= 30
  4742.6  243.77  4762.6  242.16  4812.6  235.87  4822.6   235.5  4842.6  233.15
  4862.6  229.47  4902.6  223.63  4942.6  216.45  4962.6  212.08  4964.4  209.19
  4967.4  203.19  5032.6  203.19  5035.6  209.19  5043.1  213.48  5053.1  214.73
  5113.1  213.82  5123.1  211.89  5133.1  210.89  5153.1  213.72  5173.1  214.84
  5203.1  214.54  5243.1  212.07  5313.1  214.82  5343.1  217.63  5383.1  219.22
  5463.1   227.6  5483.1  228.54  5513.1  231.32  5563.1  233.92  5660.5  241.31
#Mann= 3 , 1 , 0
 4742.60    0.13       0  4964.4   0.042       0  5035.6    0.13       0
Bank Sta=4964.40,5035.60
Exp/Cntr=0.3,0.1

Type RM Length L Ch R = 1 ,125274.8,1440.2,1440.2,1440.2
BEGIN DESCRIPTION:
Sandy Creek 125.0
END DESCRIPTION:
#Sta/Elev= 30
  4786.2  252.36  4836.2  243.68  4866.2   234.6  4886.2  227.49  4926.2  216.73
  4936.2  214.62  4946.2  213.52  4964.4  207.99  4967.4  201.99  5032.6  201.99
  5035.6  207.99  5045.1   208.6  5055.1  211.09  5065.1  211.68  5085.1  214.71
  5165.1  216.54  5205.1  218.98  5225.1  218.53  5255.1  220.37  5265.1  220.51
  5315.1  218.74  5325.1  219.63  5355.1  224.01  5365.1  224.68  5375.1  224.69
  5395.1  227.01  5415.1  228.22  5505.1  240.37  5555.1  243.24  5567.5  243.55
#Mann= 3 , 1 , 0
 4786.20    0.13       0  4964.4   0.042       0  5035.6    0.13       0
Bank Sta=4964.40,5035.60
Exp/Cntr=0.3,0.1