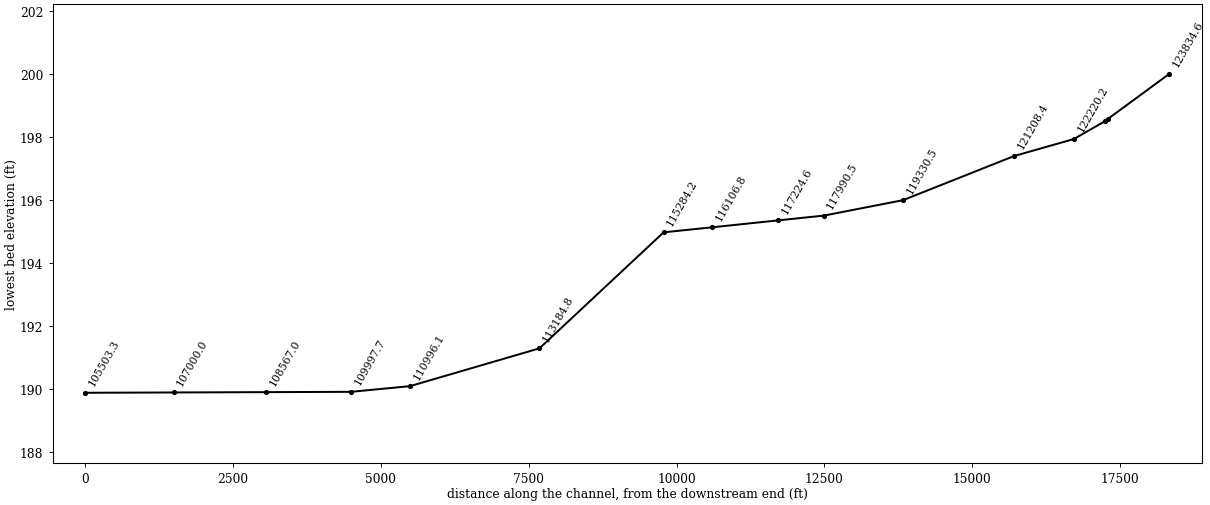
HEC-RAS study 020822_SANDY_CREEK.prj: Sandy Creek

--- 020822_SANDY_CREEK.g01 (geometry) --- (continued)

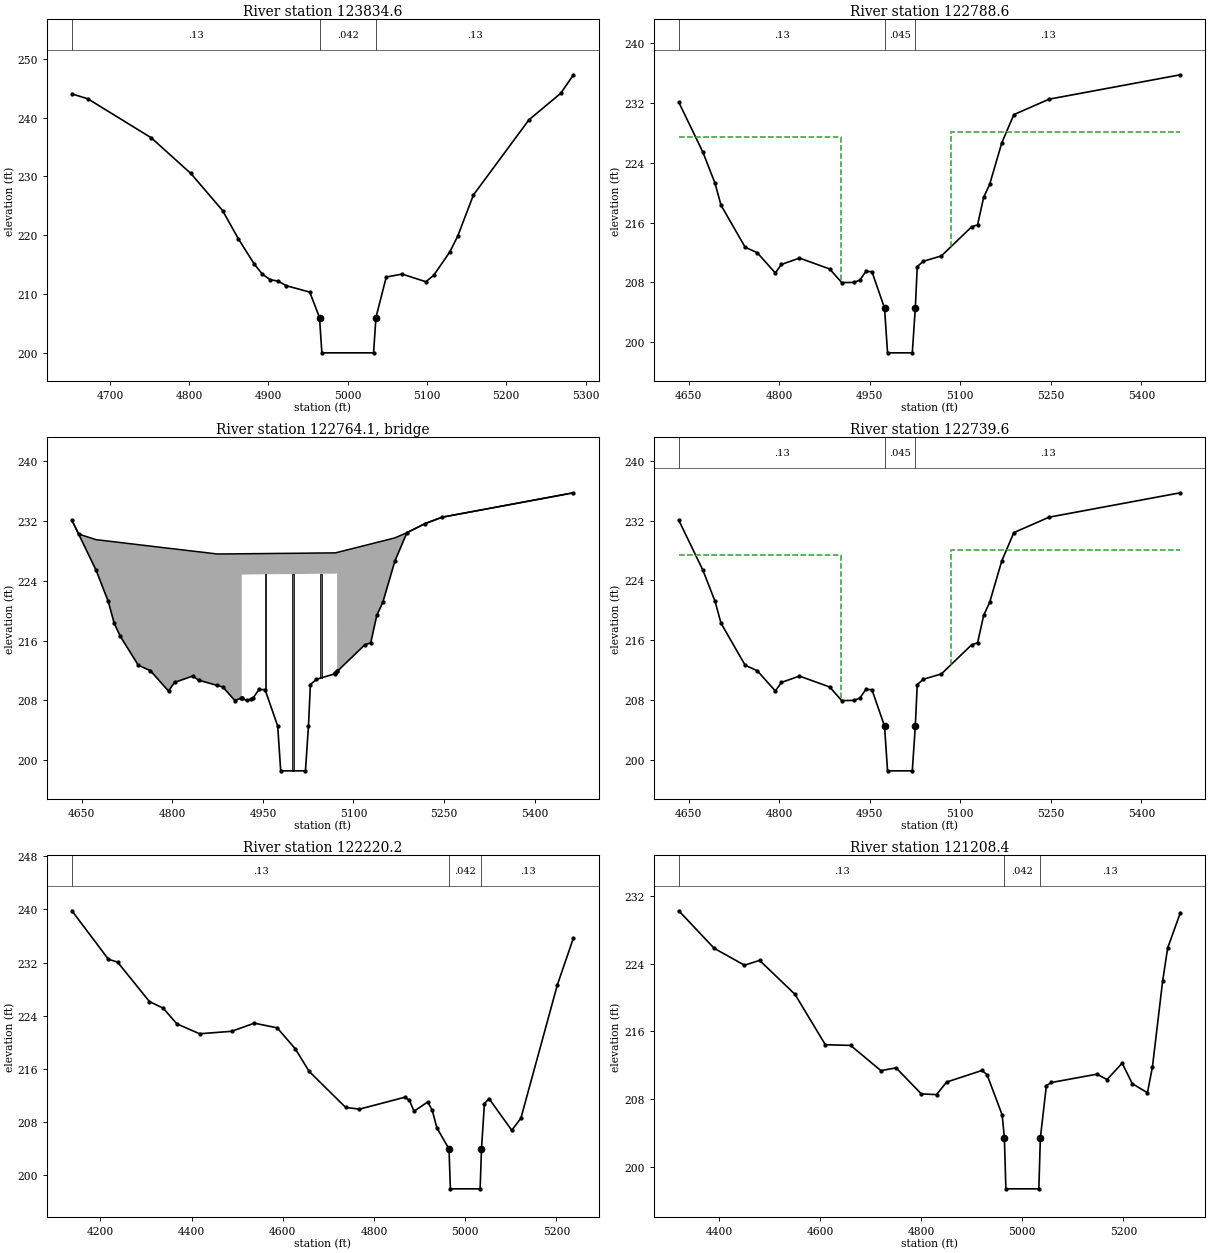
Type RM Length L Ch R = 1 ,123834.6,1046,1046,1046
BEGIN DESCRIPTION:
Sandy Creek 124.0
END DESCRIPTION:
#Sta/Elev= 26
  4652.1  244.04  4672.1  243.21  4752.1  236.58  4802.1  230.51  4842.1  224.21
  4862.1  219.39  4882.1   215.1  4892.1  213.43  4902.1  212.44  4912.1  212.22
  4922.1  211.44  4952.1  210.34  4964.4  206.01  4967.4  200.01  5032.6  200.01
  5035.6  206.01  5048.6   212.9  5068.6   213.4  5098.6   212.1  5108.6  213.22
  5128.6  217.12  5138.6  219.81  5158.6  226.86  5228.6  239.63  5268.6  244.13
  5284.8  247.29
#Mann= 3 , 1 , 0
 4652.10    0.13       0  4964.4   0.042       0  5035.6    0.13       0
Bank Sta=4964.40,5035.60
Exp/Cntr=0.3,0.1

Type RM Length L Ch R = 1 ,122788.6,49,49,49
BEGIN DESCRIPTION:
Upstream Section of Bridge/Culvert/Weir
END DESCRIPTION:
#Sta/Elev= 30
  4633.6  232.13  4673.6  225.44  4693.6  221.29  4703.6  218.34  4743.6  212.71
  4763.6  211.98  4793.6  209.26  4803.6  210.41  4833.6  211.26  4883.6   209.8
  4903.6  207.98  4923.6     208  4933.6  208.31  4943.6  209.47  4953.6  209.44
  4974.5  204.57  4979.5  198.57  5020.5  198.57  5025.5  204.57  5028.7  210.12
  5038.7  210.83  5068.7  211.55  5118.7  215.44  5128.7  215.72  5138.7  219.39
  5148.7  221.14  5168.7  226.67  5188.7  230.47    5247  232.54  5464.6  235.81
#Mann= 3 , 1 , 0
 4633.60    0.13       0  4974.5   0.045       0  5025.5    0.13       0
#XS Ineff= 2 , 0
       0    4903  227.47    5084       0  228.13
Bank Sta=4974.50,5025.50
Exp/Cntr=0.5,0.3

Type RM Length L Ch R = 3 ,122764.1,,,
BEGIN DESCRIPTION:
NC 561-1-TOR
Structure ID: NC 561-Bridge
Approximate Survey Structure
END DESCRIPTION:
Bridge Culvert--1,0,-1,-1, 0
Deck Dist Width WeirC Skew NumUp NumDn MinLoCord MaxHiCord MaxSubmerge Is_Ogee
10,29,2.6,,43,43,,,0.95,0,1,1,,
  4633.6  4644.6  4673.6  4693.6  4703.6  4713.6  4743.6  4763.6  4793.6  4803.6
  4833.6  4843.6  4874.6  4883.6  4903.6  4913.6 4914.91    4915  4923.6  4930.5
  4933.6  4943.6  4953.6  4974.5  4979.5  5020.5  5025.5  5028.7  5038.7  5068.7
  5069.5    5070 5072.89    5073  5118.7  5128.7  5138.7  5148.7  5168.7  5188.7
  5218.7    5247  5464.6
  232.11  230.27  229.51  229.32  229.23  229.13  228.84  228.65  228.36  228.27
  227.98  227.89  227.59   227.6  227.61  227.62  227.62  227.62  227.63  227.63
  227.64  227.64  227.65  227.67  227.67   227.7  227.71  227.71  227.72  227.74
  227.74  227.74   227.8   227.8  228.73  228.93  229.14  229.34  229.75  230.45
  231.66  232.52  235.79
  232.11  230.27  225.42  221.27  218.32  216.58  212.69  211.96  209.24  210.39
  211.24  210.69  209.98  209.78  207.96  208.28  208.24  224.84  224.85  224.85
  224.86  224.86  224.87  224.89  224.89  224.92  224.93  224.93  224.94  224.96
  224.96  224.96  225.02  211.86  215.42   215.7  219.37  221.12  226.65  230.45
  231.66  232.52  235.79
  4633.6  4644.6  4673.6  4693.6  4703.6  4713.6  4743.6  4763.6  4793.6  4803.6
  4833.6  4843.6  4874.6  4883.6  4903.6  4913.6 4914.91    4915  4923.6  4930.5
  4933.6  4943.6  4953.6  4974.5  4979.5  5020.5  5025.5  5028.7  5038.7  5068.7
  5069.5    5070 5072.89    5073  5118.7  5128.7  5138.7  5148.7  5168.7  5188.7
  5218.7    5247  5464.6
  232.09  230.26  229.51  229.32  229.23  229.13  228.84  228.65  228.36  228.27
  227.98  227.89  227.59   227.6  227.61  227.62  227.62  227.62  227.63  227.63
  227.64  227.64  227.65  227.67  227.67   227.7  227.71  227.71  227.72  227.74
  227.74  227.74   227.8   227.8  228.73  228.93  229.14  229.34  229.75  230.44
  231.65  232.51  235.77
  232.07  230.23  225.38  221.23  218.28  216.54  212.65  211.92   209.2  210.35
   211.2  210.65  209.94  209.74  207.92  208.24   208.2   224.8  224.81  224.81
  224.82  224.82  224.83  224.85  224.85  224.88  224.89  224.89   224.9  224.92
  224.92  224.92  224.98  211.82  215.38  215.66  219.33  221.08  226.61  230.41
  231.62  232.48  235.75
Pier Skew, UpSta & Num, DnSta & Num=,4953.7, 2 ,4953.7, 2 , 0 , 0 , 0 ,,
       2       2
  208.16  225.87
       2       2
  208.12  225.83
Pier Skew, UpSta & Num, DnSta & Num=,5000.0, 2 ,5000.0, 2 , 0 , 0 , 0 ,,
       2       2
  197.55  225.91
       2       2
  197.51  225.87
Pier Skew, UpSta & Num, DnSta & Num=,5046.4, 2 ,5046.4, 2 , 0 , 0 , 0 ,,
       2       2
  209.97  225.95
       2       2
  209.93  225.91
Abutment Skew #Up #Dn=, 2 , 2
 4914.80 4930.50
  224.84  208.19
 4914.80 4930.50
  224.80  208.15
Abutment Skew #Up #Dn=, 2 , 2
 5069.50 5073.09
  211.59  225.02
 5069.50 5073.09
  211.55  224.98
BR Coef= 1 , 1 , 0 ,1.25, 0 ,,,0.8,0,2,0,
Wspro=,,,, 1 ,,,, 0 ,,,, 0 ,,,,-1 ,-1 ,-1 , 0 , 0 , 0 , 0 , 0
BC Design=,, 0 ,, 0 ,,,,,,
BR U #Sta/Elev= 43
  4633.6  232.11  4644.6  230.27  4673.6  225.42  4693.6  221.27  4703.6  218.32
  4713.6  216.58  4743.6  212.69  4763.6  211.96  4793.6  209.24  4803.6  210.39
  4833.6  211.24  4843.6  210.69  4874.6  209.98  4883.6  209.78  4903.6  207.96
  4913.6  208.28 4914.91  208.24    4915  208.24  4923.6  207.98  4930.5  208.19
  4933.6  208.29  4943.6  209.45  4953.6  209.42  4974.5  204.55  4979.5  198.55
  5020.5  198.55  5025.5  204.55  5028.7   210.1  5038.7  210.81  5068.7  211.53
  5069.5  211.59    5070  211.63 5072.89  211.86    5073  211.86  5118.7  215.42
  5128.7   215.7  5138.7  219.37  5148.7  221.12  5168.7  226.65  5188.7  230.45
  5218.7  231.66    5247  232.52  5464.6  235.79
BR U #Mann= 3
 4633.60    0.13  4974.5   0.045  5025.5    0.13
BR U Banks=4974.50,5025.50
BR D #Sta/Elev= 43
  4633.6  232.07  4644.6  230.23  4673.6  225.38  4693.6  221.23  4703.6  218.28
  4713.6  216.54  4743.6  212.65  4763.6  211.92  4793.6   209.2  4803.6  210.35
  4833.6   211.2  4843.6  210.65  4874.6  209.94  4883.6  209.74  4903.6  207.92
  4913.6  208.24 4914.91   208.2    4915   208.2  4923.6  207.94  4930.5  208.15
  4933.6  208.25  4943.6  209.41  4953.6  209.38  4974.5  204.51  4979.5  198.51
  5020.5  198.51  5025.5  204.51  5028.7  210.06  5038.7  210.77  5068.7  211.49
  5069.5  211.55    5070  211.59 5072.89  211.82    5073  211.82  5118.7  215.38
  5128.7  215.66  5138.7  219.33  5148.7  221.08  5168.7  226.61  5188.7  230.41
  5218.7  231.62    5247  232.48  5464.6  235.75
BR D #Mann= 3
 4633.60    0.13  4974.5   0.045  5025.5    0.13
BR D Banks=4974.50,5025.50

Type RM Length L Ch R = 1 ,122739.6,519.4,519.4,519.4
BEGIN DESCRIPTION:
Downstream Section of Bridge/Culvert/Weir
END DESCRIPTION:
#Sta/Elev= 30
  4633.6  232.06  4673.6  225.37  4693.6  221.22  4703.6  218.27  4743.6  212.64
  4763.6  211.91  4793.6  209.19  4803.6  210.34  4833.6  211.19  4883.6  209.73
  4903.6  207.91  4923.6  207.93  4933.6  208.24  4943.6   209.4  4953.6  209.37
  4974.5   204.5  4979.5   198.5  5020.5   198.5  5025.5   204.5  5028.7  210.05
  5038.7  210.76  5068.7  211.48  5118.7  215.37  5128.7  215.65  5138.7  219.32
  5148.7  221.07  5168.7   226.6  5188.7   230.4    5247  232.47  5464.6  235.74
#Mann= 3 , 1 , 0
 4633.60    0.13       0  4974.5   0.045       0  5025.5    0.13       0
#XS Ineff= 2 , 0
       0    4903  227.47    5084       0  228.13
Bank Sta=4974.50,5025.50
Exp/Cntr=0.5,0.3

Type RM Length L Ch R = 1 ,122220.2,1011.8,1011.8,1011.8
BEGIN DESCRIPTION:
Sandy Creek 122.0
END DESCRIPTION:
#Sta/Elev= 30
  4137.7  239.79  4217.7  232.49  4237.7  232.07  4307.7  226.12  4337.7  225.14
  4367.7  222.77  4417.7  221.28  4487.7  221.65  4537.7  222.87  4587.7  222.17
  4627.7  218.99  4657.7  215.62  4737.7   210.2  4767.7  209.93  4867.7  211.73
  4877.7  211.25  4887.7  209.61  4917.7  211.02  4927.7  209.75  4937.7  207.14
  4964.4  203.94  4967.4  197.94  5032.6  197.94  5035.6  203.94    5042  210.75
    5052  211.53    5102  206.75    5122  208.57    5202  228.66  5237.3  235.72
#Mann= 3 , 1 , 0
 4137.70    0.13       0  4964.4   0.042       0  5035.6    0.13       0
Bank Sta=4964.40,5035.60
Exp/Cntr=0.3,0.1

Type RM Length L Ch R = 1 ,121208.4,1877.9,1877.9,1877.9
BEGIN DESCRIPTION:
Sandy Creek 121.0
END DESCRIPTION:
#Sta/Elev= 30
  4320.1  230.24  4390.1  225.81  4450.1  223.81  4480.1  224.38  4550.1  220.37
  4610.1  214.42  4660.1  214.34  4720.1  211.36  4750.1  211.69  4800.1  208.61
  4830.1  208.53  4850.1  210.01  4920.1  211.38  4930.1  210.88  4960.1  206.12
  4964.4   203.4  4967.4   197.4  5032.6   197.4  5035.6   203.4  5047.5  209.59
  5057.5  209.96  5147.5  210.94  5167.5  210.31  5197.5  212.24  5217.5  209.82
  5247.5  208.75  5257.5  211.84  5277.5  221.91  5287.5  225.84  5312.6     230
#Mann= 3 , 1 , 0
 4320.10    0.13       0  4964.4   0.042       0  5035.6    0.13       0
Bank Sta=4964.40,5035.60
Exp/Cntr=0.3,0.1

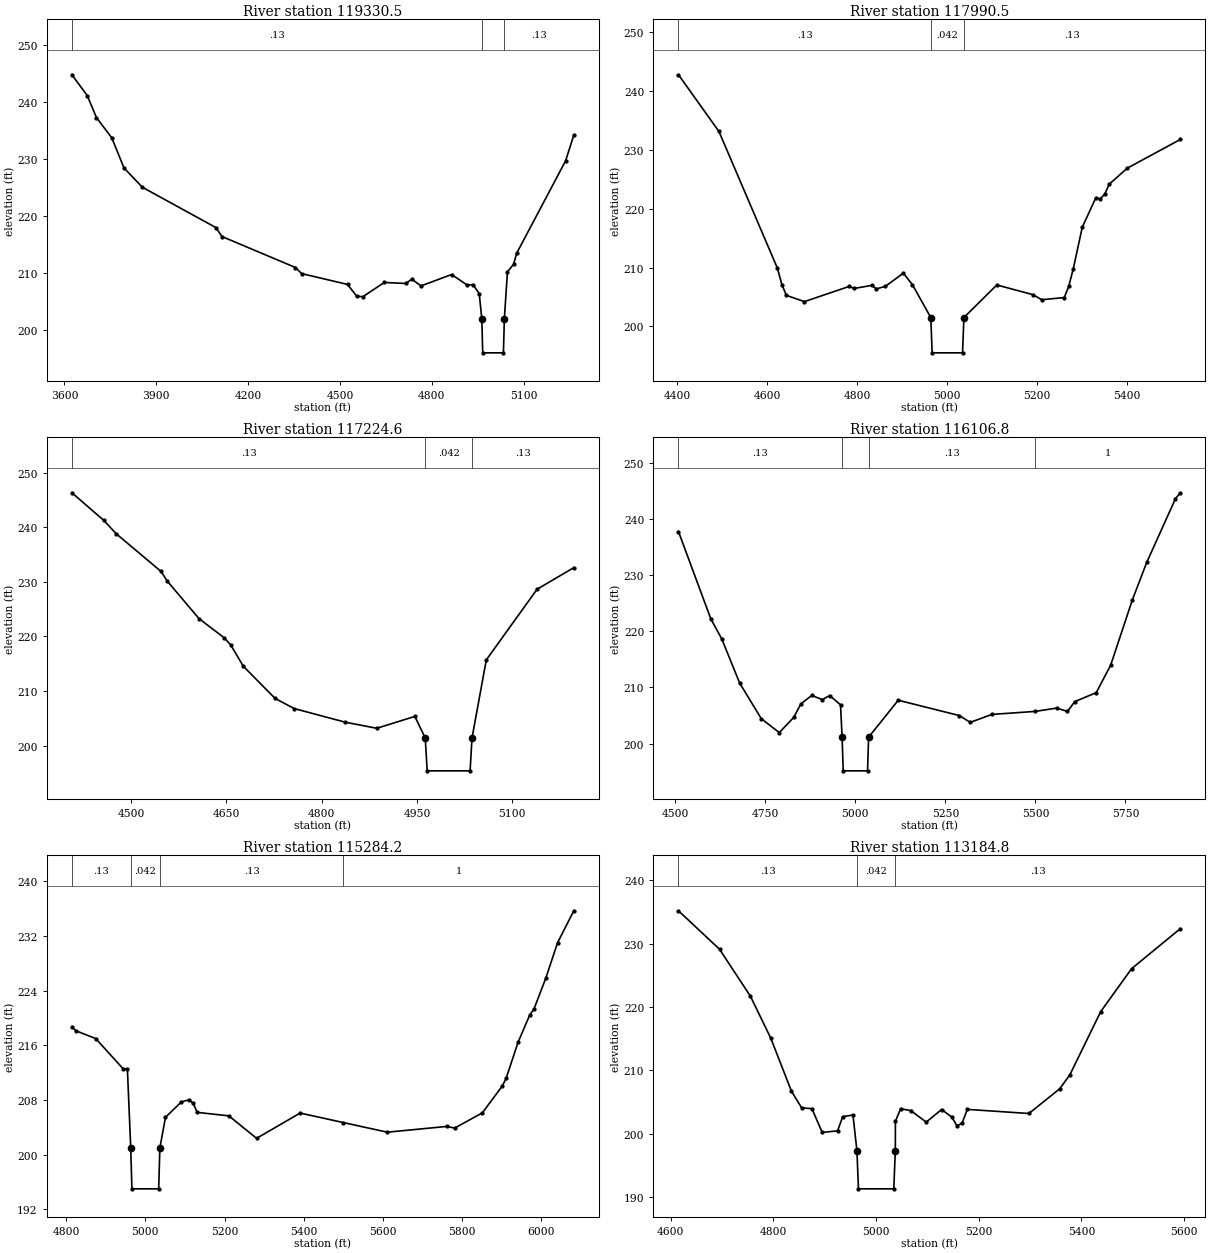
Type RM Length L Ch R = 1 ,119330.5,1340,1340,1340
BEGIN DESCRIPTION:
Sandy Creek 119.0
END DESCRIPTION:
#Sta/Elev= 30
  3624.7  244.85  3674.7  241.19  3704.7  237.33  3754.7  233.78  3794.7  228.48
  3854.7  225.09  4094.7  218.01  4114.7  216.43  4354.7  210.99  4374.7  209.92
  4524.7  208.02  4554.7  205.95  4574.7  205.86  4644.7  208.36  4714.7  208.19
  4734.7  208.94  4764.7  207.76  4864.7  209.76  4914.7  207.93  4934.7  207.96
  4954.7  206.42  4963.2     202  4966.2     196  5033.8     196  5036.8     202
    5047  210.24    5067  211.56    5077  213.49    5237  229.75  5263.6  234.25
#Mann= 3 , 1 , 0
 3624.70    0.13       0  4963.2   0.042       0  5036.8    0.13       0
Bank Sta=4963.20,5036.80
Exp/Cntr=0.3,0.1

Type RM Length L Ch R = 1 ,117990.5,765.9,765.9,765.9
BEGIN DESCRIPTION:
Sandy Creek 118.0
END DESCRIPTION:
#Sta/Elev= 30
  4402.2  242.79  4492.2  233.15  4622.2   209.9  4632.2  207.07  4642.2  205.28
  4682.2  204.22  4782.2  206.81  4792.2  206.45  4832.2  206.98  4842.2  206.39
  4862.2  206.81  4902.2  209.06  4922.2  207.12  4963.2  201.51  4966.2  195.51
  5033.8  195.51  5036.8  201.51    5110  207.05    5190  205.41    5210  204.54
    5260  204.91    5270  206.85    5280   209.8    5300  216.87    5330  221.86
    5340   221.7    5350   222.5    5360  224.19    5400  226.91    5518  231.79
#Mann= 3 , 1 , 0
 4402.20    0.13       0  4963.2   0.042       0  5036.8    0.13       0
Bank Sta=4963.20,5036.80
Exp/Cntr=0.3,0.1

Type RM Length L Ch R = 1 ,117224.6,1117.8,1117.8,1117.8
BEGIN DESCRIPTION:
Sandy Creek 117.0
END DESCRIPTION:
#Sta/Elev= 21
  4406.8  246.34  4456.8  241.29  4476.8   238.8  4546.8  231.95  4556.8  230.16
  4606.8  223.28  4646.8  219.73  4656.8  218.44  4676.8  214.52  4726.8  208.63
  4756.8  206.78  4836.8  204.29  4886.8  203.16  4946.8  205.34  4963.2  201.36
  4966.2  195.36  5033.8  195.36  5036.8  201.36  5059.3   215.7  5139.3  228.66
  5197.1  232.61
#Mann= 3 , 1 , 0
 4406.80    0.13       0  4963.2   0.042       0  5036.8    0.13       0
Bank Sta=4963.20,5036.80
Exp/Cntr=0.3,0.1

Type RM Length L Ch R = 1 ,116106.8,822.6,822.6,822.6
BEGIN DESCRIPTION:
Sandy Creek 116.0
END DESCRIPTION:
#Sta/Elev= 30
  4508.7   237.8  4598.7  222.21  4628.7   218.7  4678.7  210.78  4738.7  204.44
  4788.7  201.96  4828.7  204.66  4848.7  207.08  4878.7  208.58  4908.7  207.84
  4928.7  208.57  4958.7  206.91  4963.2  201.14  4966.2  195.14  5033.8  195.14
  5036.8  201.14  5119.1  207.73  5289.1  204.99  5319.1  203.78  5379.1   205.2
  5499.9  205.74  5559.1  206.33  5589.1  205.73  5609.1  207.47  5669.1  209.09
  5709.1  213.99  5769.1  225.59  5809.1  232.29  5889.1  243.68  5902.5  244.72
#Mann= 4 , 1 , 0
 4508.70    0.13       0  4963.2   0.042       0  5036.8    0.13       0
  5499.9       1       0
Bank Sta=4963.20,5036.80
Exp/Cntr=0.3,0.1

Type RM Length L Ch R = 1 ,115284.2,2099.4,2099.4,2099.4
BEGIN DESCRIPTION:
Sandy Creek 114.0
END DESCRIPTION:
#Sta/Elev= 30
  4814.8  218.65  4824.8  218.11  4874.8  216.97  4944.8   212.5  4954.8  212.52
  4963.2  200.98  4966.2  194.98  5033.8  194.98  5036.8  200.98    5051  205.45
    5091   207.7    5111  208.02    5121  207.49    5131  206.17    5211  205.66
    5281  202.37    5391  206.07  5499.9  204.68    5611  203.27    5761  204.11
    5781  203.87    5851   206.1    5901     210    5911  211.13    5941   216.4
    5971  220.46    5981  221.25    6011  225.77    6041  231.01  6081.9  235.67
#Mann= 4 , 1 , 0
 4814.80    0.13       0  4963.2   0.042       0  5036.8    0.13       0
  5499.9       1       0
Bank Sta=4963.20,5036.80
Exp/Cntr=0.3,0.1

Type RM Length L Ch R = 1 ,113184.8,2188.7,2188.7,2188.7
BEGIN DESCRIPTION:
Sandy Creek 113.0
END DESCRIPTION:
#Sta/Elev= 30
  4614.9  235.18  4694.9  229.11  4754.9  221.72  4794.9  215.05  4834.9  206.73
  4854.9  204.08  4874.9  203.95  4894.9  200.21  4924.9  200.45  4934.9  202.69
  4954.9  202.95  4962.6   197.3  4965.6   191.3  5034.4   191.3  5037.4   197.3
  5037.6  201.95  5047.6  203.94  5067.6  203.65  5097.6  201.83  5127.6  203.82
  5147.6  202.61  5157.6  201.24  5167.6  201.68  5177.6  203.84  5297.6  203.19
  5357.6  207.08  5377.6  209.31  5437.6  219.27  5497.6  226.03  5592.7  232.36
#Mann= 3 , 1 , 0
 4614.90    0.13       0  4962.6   0.042       0  5037.4    0.13       0
Bank Sta=4962.60,5037.40
Exp/Cntr=0.3,0.1

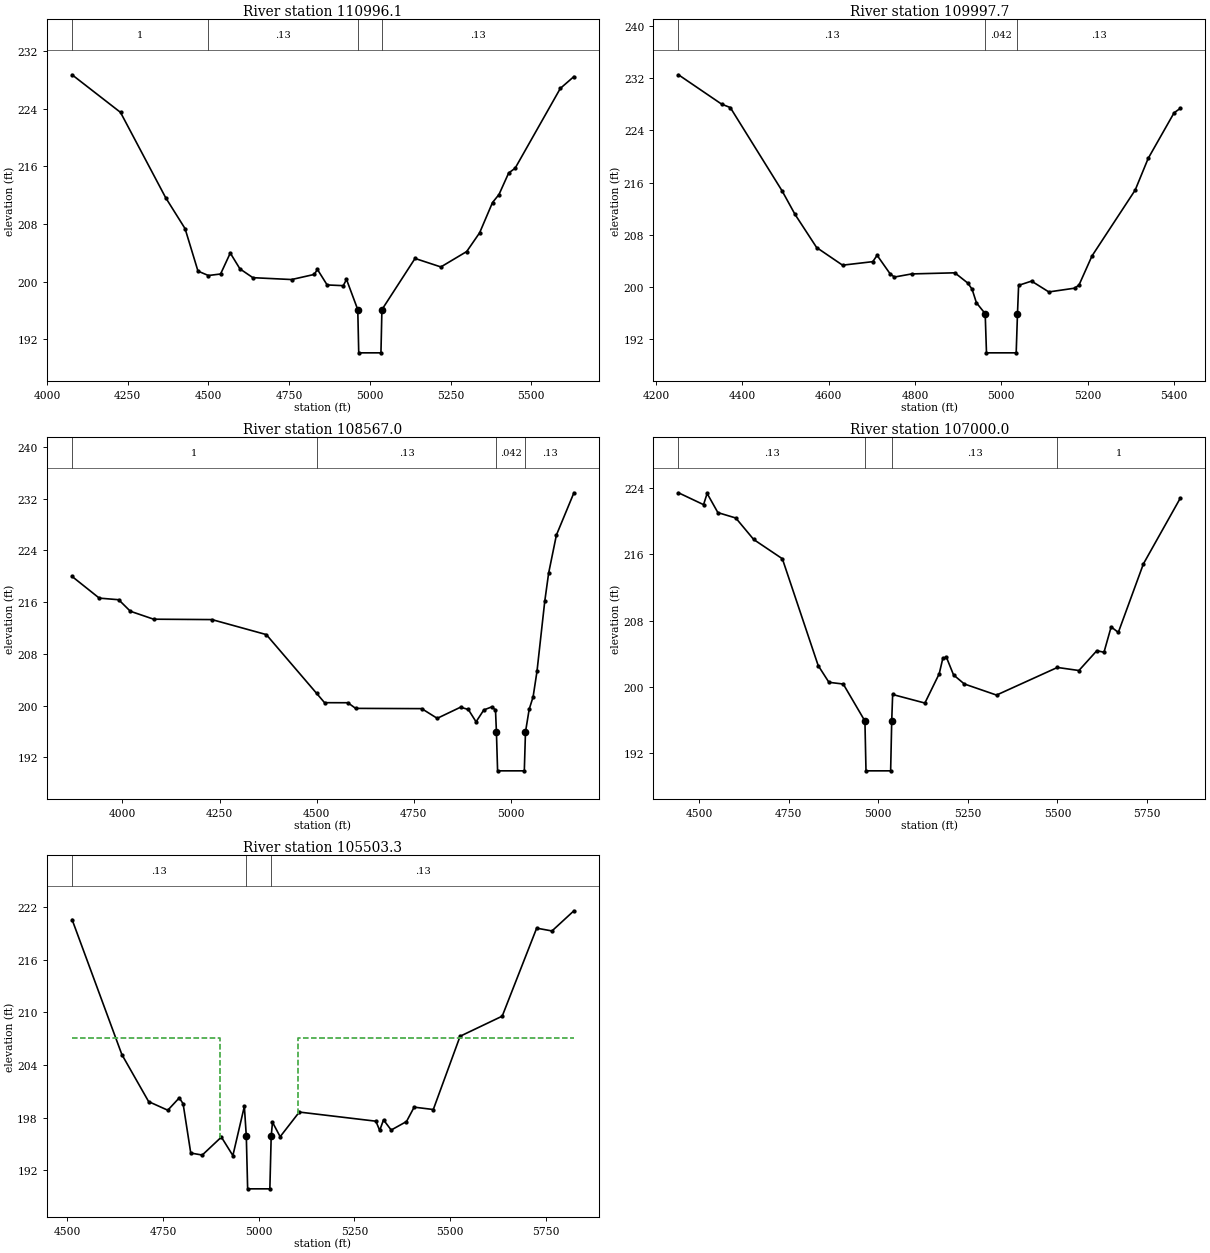
Type RM Length L Ch R = 1 ,110996.1,998.4,998.4,998.4
BEGIN DESCRIPTION:
Sandy Creek 111.0
END DESCRIPTION:
#Sta/Elev= 30
  4077.7  228.72  4227.7   223.5  4367.7  211.64  4427.7  207.35  4467.7  201.45
  4499.9  200.84  4537.7  201.05  4567.7  203.96  4597.7  201.76  4637.7  200.54
  4757.7  200.28  4827.7  200.99  4837.7  201.68  4867.7  199.53  4917.7  199.43
  4927.7   200.3  4962.6   196.1  4965.6   190.1  5034.4   190.1  5037.4   196.1
    5140  203.21    5220  202.03    5300  204.17    5340  206.77    5380  210.98
    5400  212.09    5430  215.08    5450  215.74    5590  226.83  5632.1  228.47
#Mann= 4 , 1 , 0
 4077.70       1       0  4499.9    0.13       0  4962.6   0.042       0
  5037.4    0.13       0
Bank Sta=4962.60,5037.40
Exp/Cntr=0.3,0.1

Type RM Length L Ch R = 1 ,109997.7,1430.7,1430.7,1430.7
BEGIN DESCRIPTION:
Sandy Creek 110.0
END DESCRIPTION:
#Sta/Elev= 30
  4252.3  232.52  4352.3  228.02  4372.3   227.5  4492.3  214.73  4522.3  211.12
  4572.3  206.05  4632.3  203.35  4702.3  203.89  4712.3  204.86  4742.3  202.04
  4752.3  201.53  4792.3  202.01  4892.3  202.18  4922.3  200.61  4932.3  199.66
  4942.3  197.59  4962.6  195.92  4965.6  189.92  5034.4  189.92  5037.4  195.92
    5040  200.26    5070  200.91    5110  199.25    5170  199.83    5180  200.33
    5210  204.77    5310  214.86    5340   219.7    5400  226.69  5414.5  227.38
#Mann= 3 , 1 , 0
 4252.30    0.13       0  4962.6   0.042       0  5037.4    0.13       0
Bank Sta=4962.60,5037.40
Exp/Cntr=0.3,0.1

Type RM Length L Ch R = 1 ,108567.0,1567,1567,1567
BEGIN DESCRIPTION:
Sandy Creek 109.0
END DESCRIPTION:
#Sta/Elev= 30
  3870.2  219.97  3940.2  216.62  3990.2  216.37  4020.2  214.59  4080.2  213.36
  4230.2   213.3  4370.2  210.98  4499.9  201.88  4520.2  200.45  4580.2  200.44
  4600.2  199.57  4770.2  199.53  4810.2  198.03  4870.2  199.75  4890.2   199.4
  4910.2  197.49  4930.2  199.33  4950.2  199.79  4960.2  199.35  4962.6  195.91
  4965.6  189.91  5034.4  189.91  5037.4  195.91    5047  199.45    5057  201.34
    5067  205.28    5087  216.12    5097  220.48    5117  226.37  5162.1  232.91
#Mann= 4 , 1 , 0
 3870.20       1       0  4499.9    0.13       0  4962.6   0.042       0
  5037.4    0.13       0
Bank Sta=4962.60,5037.40
Exp/Cntr=0.3,0.1

Type RM Length L Ch R = 1 ,107000.0,1496.7,1496.7,1496.7
BEGIN DESCRIPTION:
Sandy Creek 107.0
END DESCRIPTION:
#Sta/Elev= 30
  4442.1  223.41  4512.1  221.98  4522.1  223.33  4552.1  221.02  4602.1  220.37
  4652.1  217.78  4732.1  215.46  4832.1  202.59  4862.1  200.57  4902.1  200.36
  4962.6   195.9  4965.6   189.9  5034.4   189.9  5037.4   195.9    5040   199.1
    5130  198.07    5170   201.6    5180  203.44    5190   203.6    5210  201.46
    5240  200.37    5330  199.03  5499.9  202.36    5560  201.99    5610  204.38
    5630  204.19    5650  207.25    5670  206.58    5740  214.84  5843.1  222.77
#Mann= 4 , 1 , 0
 4442.10    0.13       0  4962.6   0.042       0  5037.4    0.13       0
  5499.9       1       0
Bank Sta=4962.60,5037.40
Exp/Cntr=0.3,0.1

Type RM Length L Ch R = 1 ,105503.3,41,41,41
BEGIN DESCRIPTION:
Upstream Section of Bridge/Culvert/Weir
END DESCRIPTION:
#Sta/Elev= 30
  4512.4  220.58  4642.4   205.2  4712.4  199.83  4762.4  198.85  4792.4  200.26
  4802.4  199.59  4822.4  193.97  4852.4  193.74  4902.4  195.79  4932.4  193.68
  4962.4  199.29  4967.5  195.89    4971  189.89    5029  189.89  5032.5  195.89
  5035.9  197.48  5055.9  195.83  5105.9  198.64  5305.9   197.6  5315.9  196.55
  5325.9  197.75  5345.9  196.59  5385.9  197.56  5405.9   199.2  5455.9  198.93
  5525.9  207.28  5635.9  209.57  5725.9   219.6  5765.9  219.28  5823.2  221.58
#Mann= 3 , 1 , 0
 4512.40    0.13       0  4967.5   0.045       0  5032.5    0.13       0
#XS Ineff= 2 , 0
       0 4898.79  207.12 5101.54       0  207.12
Bank Sta=4967.50,5032.50
Exp/Cntr=0.5,0.3