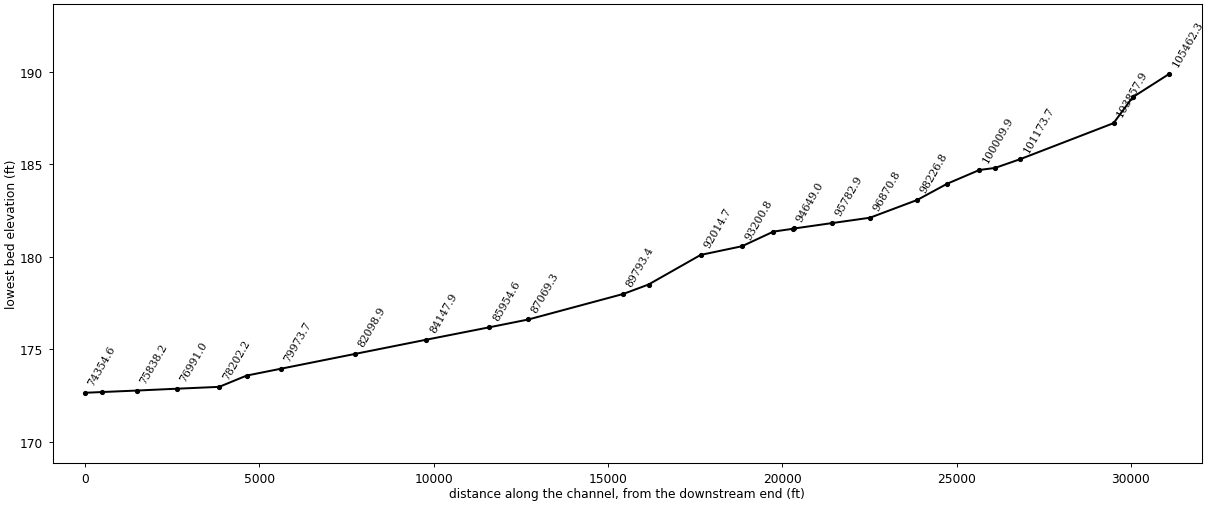
HEC-RAS study 020822_SANDY_CREEK.prj: Sandy Creek

--- 020822_SANDY_CREEK.g01 (geometry) --- (continued)

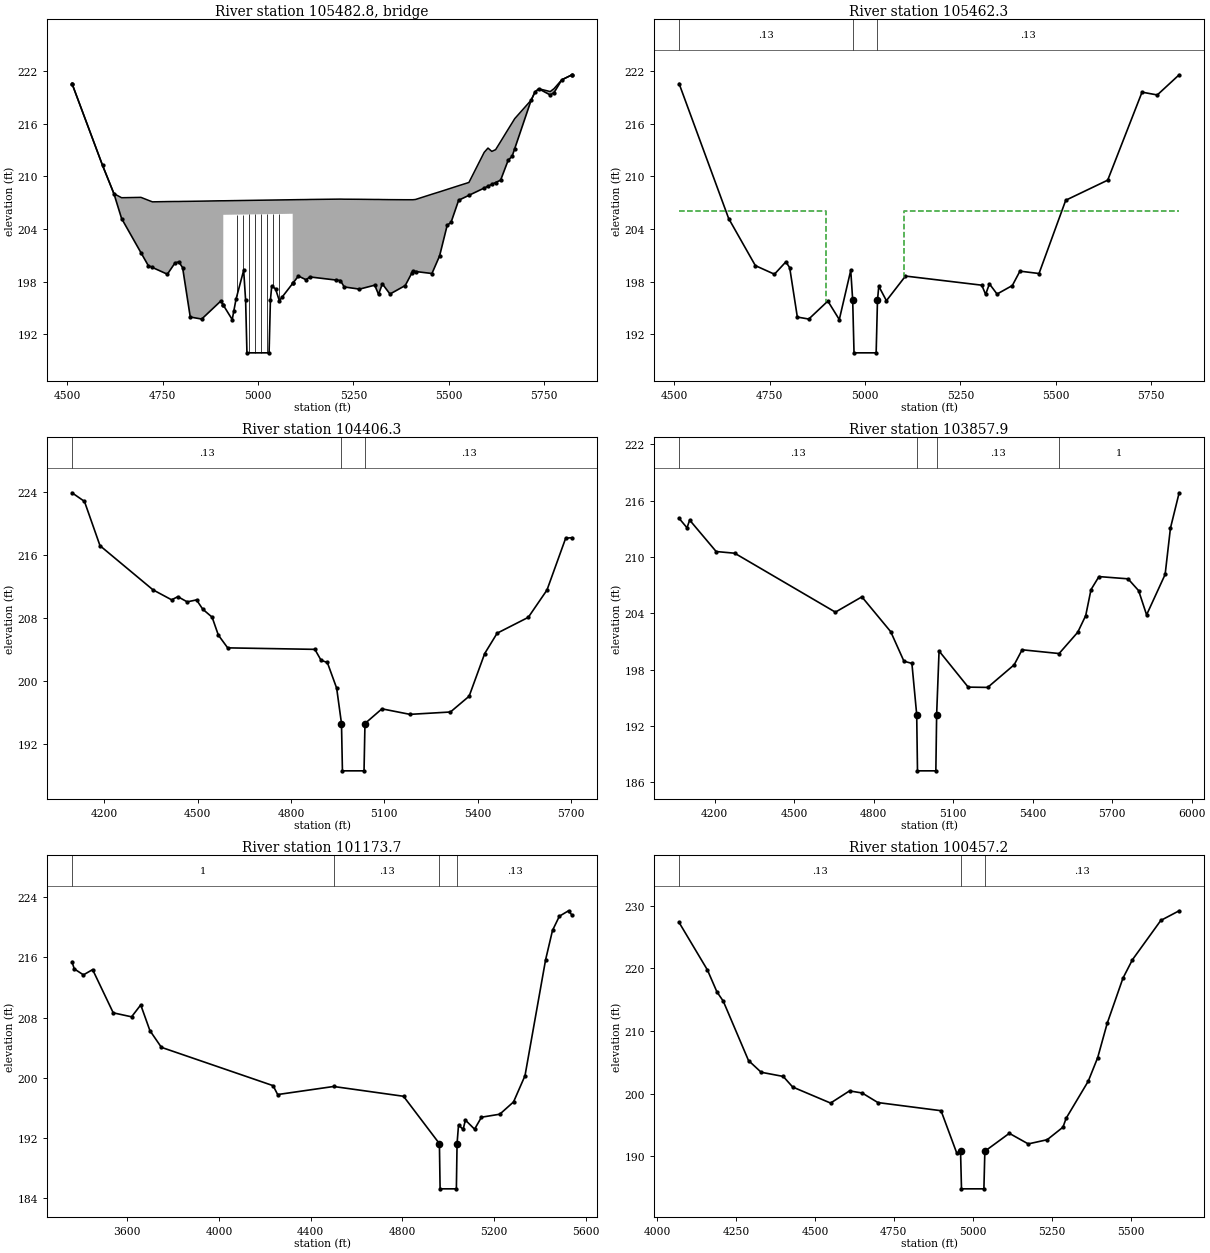
Type RM Length L Ch R = 3 ,105482.8,,,
BEGIN DESCRIPTION:
Leonard Rd-1-TOR
Structure ID: Leonard Rd_sandy-Bridge
Approximate Survey Structure
END DESCRIPTION:
Bridge Culvert--1,0,-1,-1, 0
Deck Dist Width WeirC Skew NumUp NumDn MinLoCord MaxHiCord MaxSubmerge Is_Ogee
10,21,2.6,, 52, 52,,,0.95,0,1,1,,
  4512.4  4592.4  4622.4  4642.4  4693.2  4712.4  4723.2  4762.4  4782.4  4792.4
  4802.4  4822.4  4852.4  4902.4 4908.91    4909 5090.89    5091  5105.9  5125.9
  5135.9  5215.9  5225.9  5265.9  5305.9  5315.9  5325.9  5345.9  5385.9  5405.9
  5412.8  5455.9  5475.9  5495.9  5505.9  5525.9  5552.8  5592.8  5602.8  5612.8
  5622.8  5635.9  5655.9  5665.9  5672.8  5715.9  5725.9  5735.9  5765.9  5775.9
  5796.2  5823.2
  220.58  211.27  208.03  207.57  207.61  207.28   207.1  207.13  207.14  207.14
  207.15  207.16  207.18  207.22  207.22  207.22  207.34  207.34  207.35  207.36
  207.37  207.41   207.4  207.39  207.37  207.37  207.36  207.35  207.34  207.34
  207.37  207.97  208.24  208.52  208.66  208.94  209.31  212.74  213.23  212.85
  213.05  213.97  215.39  216.09  216.58  218.69  219.61  219.99  219.67     220
  221.01  221.58
  220.58  211.26  208.02   205.2   201.3  199.83  199.62  198.85  200.13  200.26
  199.59  193.97  193.74  195.79  195.33  205.62  205.74   197.8  198.64  198.22
  198.54  198.13   197.4  197.15   197.6  196.55  197.75  196.59  197.56   199.2
  199.16  198.93  200.93  204.43  204.75  207.28  207.84  208.67  208.88  209.09
   209.3  209.57  211.86  212.27  213.15  218.68   219.6  219.98  219.28  219.54
     221  221.58
  4512.4  4592.4  4622.4  4642.4  4693.2  4712.4  4723.2  4762.4  4782.4  4792.4
  4802.4  4822.4  4852.4  4902.4 4908.91    4909 5090.89    5091  5105.9  5125.9
  5135.9  5215.9  5225.9  5265.9  5305.9  5315.9  5325.9  5345.9  5385.9  5405.9
  5412.8  5455.9  5475.9  5495.9  5505.9  5525.9  5552.8  5592.8  5602.8  5612.8
  5622.8  5635.9  5655.9  5665.9  5672.8  5715.9  5725.9  5735.9  5765.9  5775.9
  5796.2  5823.2
  220.58  211.27  208.03  207.57  207.61  207.28   207.1  207.13  207.14  207.14
  207.15  207.16  207.18  207.22  207.22  207.22  207.34  207.34  207.35  207.36
  207.37  207.41   207.4  207.39  207.37  207.37  207.36  207.35  207.34  207.34
  207.37  207.97  208.24  208.52  208.66  208.94  209.31  212.74  213.23  212.85
  213.05  213.97  215.39  216.09  216.58  218.69  219.61  219.99  219.67     220
  221.01  221.58
  220.58  211.26  208.02   205.2   201.3  199.83  199.62  198.85  200.13  200.26
  199.59  193.97  193.74  195.79  195.33  205.62  205.74   197.8  198.64  198.22
  198.54  198.13   197.4  197.15   197.6  196.55  197.75  196.59  197.56   199.2
  199.16  198.93  200.93  204.43  204.75  207.28  207.84  208.67  208.88  209.09
   209.3  209.57  211.86  212.27  213.15  218.68   219.6  219.98  219.28  219.54
     221  221.58
Pier Skew, UpSta & Num, DnSta & Num=,4944.4, 2 ,4944.4, 2 , 0 , 0 , 0 ,,
       1       1
  195.26  206.64
       1       1
  195.26  206.64
Pier Skew, UpSta & Num, DnSta & Num=,4960.3, 2 ,4960.3, 2 , 0 , 0 , 0 ,,
       1       1
  197.86  206.65
       1       1
  197.86  206.65
Pier Skew, UpSta & Num, DnSta & Num=,4976.1, 2 ,4976.1, 2 , 0 , 0 , 0 ,,
       1       1
  188.89  206.66
       1       1
  188.89  206.66
Pier Skew, UpSta & Num, DnSta & Num=,4992.0, 2 ,4992.0, 2 , 0 , 0 , 0 ,,
       1       1
  188.89  206.67
       1       1
  188.89  206.67
Pier Skew, UpSta & Num, DnSta & Num=,5007.9, 2 ,5007.9, 2 , 0 , 0 , 0 ,,
       1       1
  188.89  206.69
       1       1
  188.89  206.69
Pier Skew, UpSta & Num, DnSta & Num=,5023.8, 2 ,5023.8, 2 , 0 , 0 , 0 ,,
       1       1
  188.89   206.7
       1       1
  188.89   206.7
Pier Skew, UpSta & Num, DnSta & Num=,5039.6, 2 ,5039.6, 2 , 0 , 0 , 0 ,,
       1       1
  196.36   206.7
       1       1
  196.36   206.7
Pier Skew, UpSta & Num, DnSta & Num=,5055.5, 2 ,5055.5, 2 , 0 , 0 , 0 ,,
       1       1
  194.84  206.71
       1       1
  194.84  206.71
Abutment Skew #Up #Dn=, 2 , 2
 4908.80 4936.50
  205.62  194.64
 4908.80 4936.50
  205.62  194.64
Abutment Skew #Up #Dn=, 2 , 2
 5063.50 5091.09
  196.26  205.74
 5063.50 5091.09
  196.26  205.74
BR Coef= 1 , 1 , 0 ,1.25, 0 ,,,0.8,0,2,0,
Wspro=,,,, 1 ,,,, 0 ,,,, 0 ,,,,-1 ,-1 ,-1 , 0 , 0 , 0 , 0 , 0
BC Design=,, 0 ,, 0 ,,,,,,
BR U #Sta/Elev= 68
  4512.4  220.58  4513.2  220.49  4592.4  211.26  4622.4  208.02  4642.4   205.2
  4693.2   201.3  4712.4  199.83  4723.2  199.62  4762.4  198.85  4782.4  200.13
  4792.4  200.26  4802.4  199.59  4822.4  193.97  4852.4  193.74  4902.4  195.79
 4908.91  195.33    4909  195.33  4932.4  193.68  4936.5  194.64  4942.4  196.01
  4962.4  199.29  4967.5  195.89    4971  189.89    5029  189.89  5032.5  195.89
  5035.9  197.48  5045.9  197.19  5055.9  195.83  5063.5  196.26 5090.89   197.8
    5091   197.8  5105.9  198.64  5125.9  198.22  5135.9  198.54  5205.4  198.18
  5215.9  198.13  5225.9   197.4  5265.9  197.15  5305.9   197.6  5315.9  196.55
  5325.9  197.75  5345.9  196.59  5385.9  197.56  5402.8  198.95  5405.9   199.2
  5412.8  199.16  5455.9  198.93  5475.9  200.93  5495.9  204.43  5505.9  204.75
  5525.9  207.28  5552.8  207.84  5592.8  208.67  5602.8  208.88  5612.8  209.09
  5622.8   209.3  5635.9  209.57  5655.9  211.86  5665.9  212.27  5672.8  213.15
  5715.9  218.68  5725.9   219.6  5735.9  219.98  5765.9  219.28  5775.9  219.54
  5796.2     221  5822.8  221.57  5823.2  221.58
BR U #Mann= 3
 4512.40    0.13  4967.5   0.045  5032.5    0.13
BR U Banks=4967.50,5032.50
BR D #Sta/Elev= 68
  4512.4  220.58  4513.2  220.49  4592.4  211.26  4622.4  208.02  4642.4   205.2
  4693.2   201.3  4712.4  199.83  4723.2  199.62  4762.4  198.85  4782.4  200.13
  4792.4  200.26  4802.4  199.59  4822.4  193.97  4852.4  193.74  4902.4  195.79
 4908.91  195.33    4909  195.33  4932.4  193.68  4936.5  194.64  4942.4  196.01
  4962.4  199.29  4967.5  195.89    4971  189.89    5029  189.89  5032.5  195.89
  5035.9  197.48  5045.9  197.19  5055.9  195.83  5063.5  196.26 5090.89   197.8
    5091   197.8  5105.9  198.64  5125.9  198.22  5135.9  198.54  5205.4  198.18
  5215.9  198.13  5225.9   197.4  5265.9  197.15  5305.9   197.6  5315.9  196.55
  5325.9  197.75  5345.9  196.59  5385.9  197.56  5402.8  198.95  5405.9   199.2
  5412.8  199.16  5455.9  198.93  5475.9  200.93  5495.9  204.43  5505.9  204.75
  5525.9  207.28  5552.8  207.84  5592.8  208.67  5602.8  208.88  5612.8  209.09
  5622.8   209.3  5635.9  209.57  5655.9  211.86  5665.9  212.27  5672.8  213.15
  5715.9  218.68  5725.9   219.6  5735.9  219.98  5765.9  219.28  5775.9  219.54
  5796.2     221  5822.8  221.57  5823.2  221.58
BR D #Mann= 3
 4512.40    0.13  4967.5   0.045  5032.5    0.13
BR D Banks=4967.50,5032.50

Type RM Length L Ch R = 1 ,105462.3,1056,1056,1056
BEGIN DESCRIPTION:
Downstream Section of Bridge/Culvert/Weir
END DESCRIPTION:
#Sta/Elev= 30
  4512.4  220.58  4642.4   205.2  4712.4  199.83  4762.4  198.85  4792.4  200.26
  4802.4  199.59  4822.4  193.97  4852.4  193.74  4902.4  195.79  4932.4  193.68
  4962.4  199.29  4967.5  195.89    4971  189.89    5029  189.89  5032.5  195.89
  5035.9  197.48  5055.9  195.83  5105.9  198.64  5305.9   197.6  5315.9  196.55
  5325.9  197.75  5345.9  196.59  5385.9  197.56  5405.9   199.2  5455.9  198.93
  5525.9  207.28  5635.9  209.57  5725.9   219.6  5765.9  219.28  5823.2  221.58
#Mann= 3 , 1 , 0
 4512.40    0.13       0  4967.5   0.045       0  5032.5    0.13       0
#XS Ineff= 2 , 0
       0 4898.79     206 5101.54       0     206
Bank Sta=4967.50,5032.50
Exp/Cntr=0.5,0.3

Type RM Length L Ch R = 1 ,104406.3,548.4,548.4,548.4
BEGIN DESCRIPTION:
Sandy Creek 104.0
END DESCRIPTION:
#Sta/Elev= 30
  4096.8  223.87  4136.8  222.78  4186.8  217.16  4356.8  211.57  4416.8   210.3
  4436.8   210.7  4466.8  210.04  4496.8  210.29  4516.8  209.11  4546.8   208.1
  4566.8  205.83  4596.8  204.21  4876.8  204.02  4896.8  202.63  4916.8  202.36
  4946.8   199.1  4962.3  194.62  4965.3  188.62  5034.7  188.62  5037.7  194.62
  5092.2  196.48  5182.2  195.78  5312.2  196.08  5372.2  198.08  5422.2  203.49
  5462.2  206.07  5562.2  208.08  5622.2  211.54  5682.2  218.11  5702.8  218.18
#Mann= 3 , 1 , 0
 4096.80    0.13       0  4962.3   0.042       0  5037.7    0.13       0
Bank Sta=4962.30,5037.70
Exp/Cntr=0.3,0.1

Type RM Length L Ch R = 1 ,103857.9,2684.2,2684.2,2684.2
BEGIN DESCRIPTION:
Sandy Creek 102.7
END DESCRIPTION:
#Sta/Elev= 30
  4065.5  214.13  4095.5  213.12  4105.5  213.94  4205.5  210.59  4275.5  210.41
  4655.5  204.13  4755.5  205.76  4864.3  202.05  4914.3   198.9  4944.3  198.67
  4962.4  193.22  4965.4  187.22  5034.7  187.22  5037.7  193.22  5046.8  199.99
  5156.8  196.14  5230.3  196.11  5330.3  198.52  5360.3  200.12  5499.9  199.72
  5570.3  201.99  5600.3  203.76  5620.3  206.53  5650.3  207.92  5760.1  207.68
  5800.1  206.42  5830.1  203.84  5900.1  208.15  5920.1  213.08    5953  216.85
#Mann= 4 , 1 , 0
 4065.50    0.13       0  4962.4   0.042       0  5037.7    0.13       0
  5499.9       1       0
Bank Sta=4962.40,5037.70
Exp/Cntr=0.3,0.1

Type RM Length L Ch R = 1 ,101173.7,716.5,716.5,716.5
BEGIN DESCRIPTION:
Sandy Creek 102.5
END DESCRIPTION:
#Sta/Elev= 30
  3358.4  215.43  3368.4  214.47  3408.4  213.68  3448.4  214.38  3538.4  208.64
  3618.4  208.11  3658.4  209.69  3698.4  206.28  3748.4  204.06  4235.8  198.97
  4255.8  197.79  4499.9  198.86  4804.9  197.56  4961.5  191.27  4964.5  185.27
  5035.5  185.27  5038.5  191.27  5044.9  193.75  5064.9  193.16  5074.9   194.4
  5114.9  193.19  5144.9  194.78  5224.9  195.18  5284.9  196.81  5334.9  200.29
  5424.9   215.7  5454.9  219.58  5484.9  221.47  5524.9  222.19  5540.3  221.59
#Mann= 4 , 1 , 0
 3358.40       1       0  4499.9    0.13       0  4961.5   0.042       0
  5038.5    0.13       0
Bank Sta=4961.50,5038.50
Exp/Cntr=0.3,0.1

Type RM Length L Ch R = 1 ,100457.2,447.3,447.3,447.3
BEGIN DESCRIPTION:
Sandy Creek 102.0
END DESCRIPTION:
#Sta/Elev= 30
  4069.7  227.32  4159.7  219.72  4189.7  216.23  4209.7  214.76  4289.7  205.28
  4329.7  203.41  4399.7  202.74  4429.7  201.05  4549.7  198.49  4609.7  200.43
  4649.7   200.1  4699.7  198.57  4899.7  197.27  4949.7  190.48  4961.5   190.8
  4964.5   184.8  5035.5   184.8  5038.5   190.8    5116  193.66    5176  191.97
    5236  192.64    5286  194.64    5296  196.06    5366  201.97    5396  205.74
    5426   211.2    5476  218.42    5506  221.36    5596  227.64  5654.1  229.18
#Mann= 3 , 1 , 0
 4069.70    0.13       0  4961.5   0.042       0  5038.5    0.13       0
Bank Sta=4961.50,5038.50
Exp/Cntr=0.3,0.1

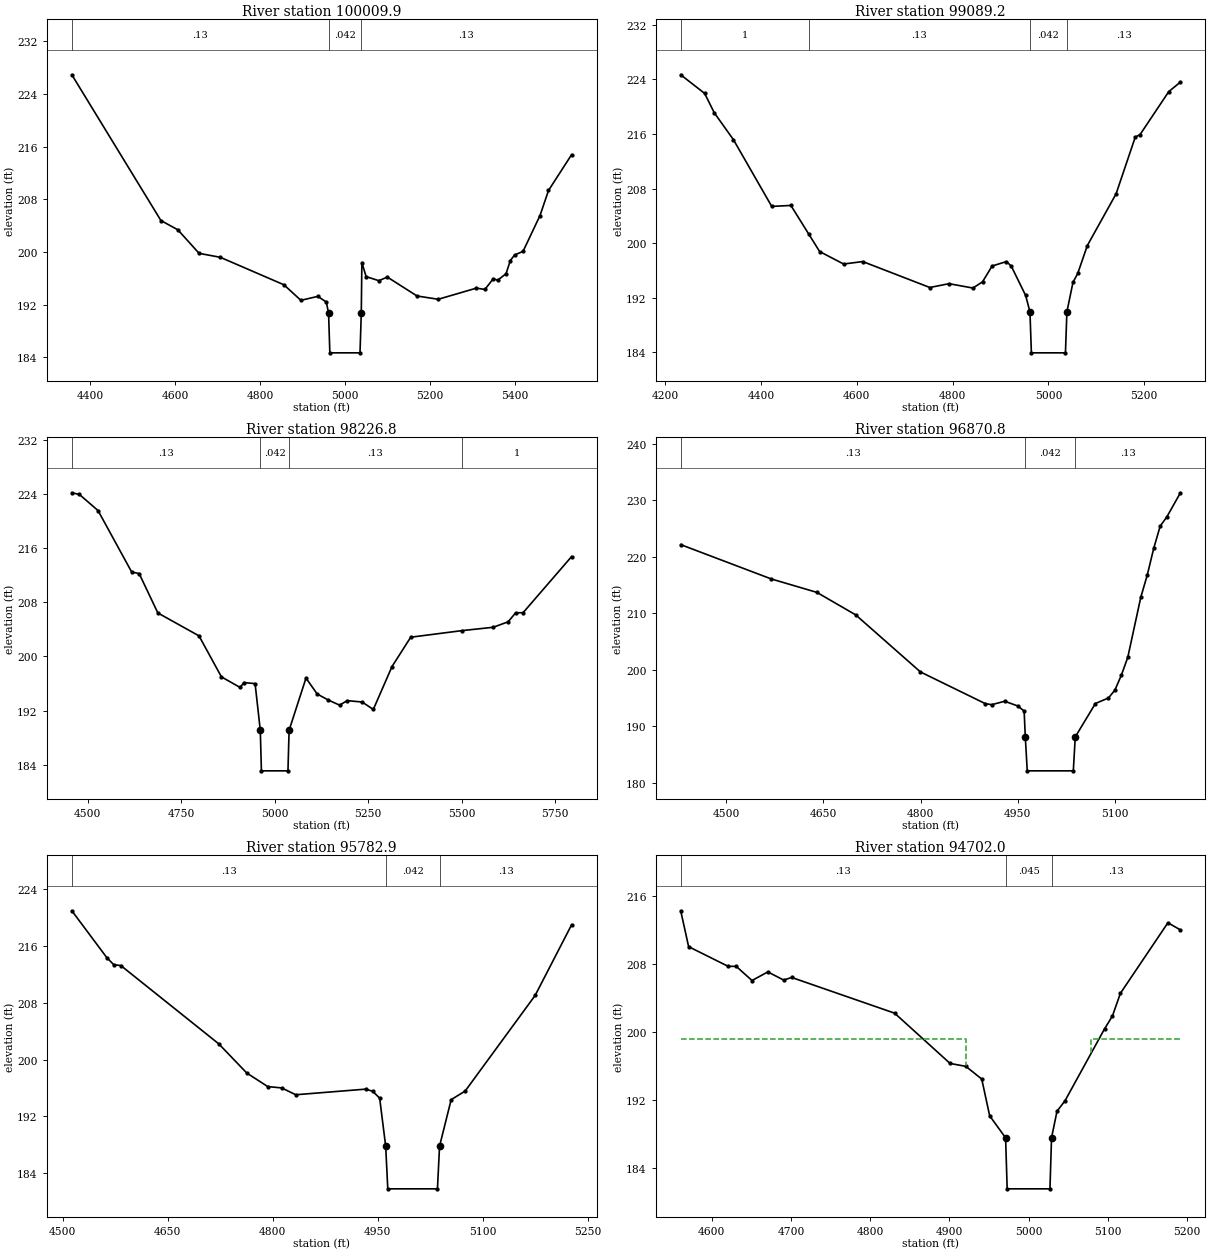
Type RM Length L Ch R = 1 ,100009.9,920.7,920.7,920.7
BEGIN DESCRIPTION:
Sandy Creek 100.0
END DESCRIPTION:
#Sta/Elev= 30
  4356.2  226.89  4566.2  204.77  4606.2  203.36  4656.2  199.79  4706.2  199.19
  4856.2  195.02  4896.2  192.66  4936.2  193.26  4956.2   192.4  4961.5  190.69
  4964.5  184.69  5035.6  184.69  5038.6  190.69    5040  198.39    5050  196.26
    5080  195.64    5100  196.19    5170  193.32    5220  192.82    5310  194.51
    5330  194.31    5350  195.95    5360   195.7    5380  196.71    5390  198.69
    5400  199.54    5420  200.09    5460  205.53    5480  209.33  5534.4  214.76
#Mann= 3 , 1 , 0
 4356.20    0.13       0  4961.5   0.042       0  5038.6    0.13       0
Bank Sta=4961.50,5038.60
Exp/Cntr=0.3,0.1

Type RM Length L Ch R = 1 ,99089.2,862.4,862.4,862.4
BEGIN DESCRIPTION:
Sandy Creek 99.0
END DESCRIPTION:
#Sta/Elev= 30
  4232.5  224.68  4282.5  221.95  4302.5  219.12  4342.5  215.18  4422.5   205.4
  4462.5  205.54  4499.9  201.33  4522.5  198.79  4572.5  196.96  4612.5  197.32
  4752.5  193.52  4792.5  194.08  4842.5  193.44  4862.5  194.35  4882.5  196.67
  4912.5  197.32  4922.5  196.65  4952.5  192.36  4961.5  189.95  4964.5  183.95
  5035.6  183.95  5038.6  189.95  5051.3  194.27  5061.3  195.59  5081.3  199.67
  5141.3  207.24  5181.3  215.55  5191.3  215.92  5251.3  222.22  5275.6  223.61
#Mann= 4 , 1 , 0
 4232.50       1       0  4499.9    0.13       0  4961.5   0.042       0
  5038.6    0.13       0
Bank Sta=4961.50,5038.60
Exp/Cntr=0.3,0.1

Type RM Length L Ch R = 1 ,98226.8,1356,1356,1356
BEGIN DESCRIPTION:
Sandy Creek 98.0
END DESCRIPTION:
#Sta/Elev= 30
  4457.6  224.23  4477.6  223.99  4527.6   221.6  4617.6   212.5  4637.6  212.27
  4687.6  206.44  4797.6  203.05  4857.6  196.98  4907.6  195.41  4917.6  196.14
  4947.6  195.98  4961.5  189.07  4964.5  183.07  5035.5  183.07  5038.5  189.07
  5083.7   196.8  5113.7  194.44  5143.7  193.54  5173.7  192.79  5193.7  193.46
  5233.7  193.26  5263.7  192.16  5313.7  198.51  5363.7  202.85  5499.9  203.82
  5584.2  204.32  5624.2  205.13  5644.2  206.46  5664.2  206.48  5793.8  214.78
#Mann= 4 , 1 , 0
 4457.60    0.13       0  4961.5   0.042       0  5038.5    0.13       0
  5499.9       1       0
Bank Sta=4961.50,5038.50
Exp/Cntr=0.3,0.1

Type RM Length L Ch R = 1 ,96870.8,1087.9,1087.9,1087.9
BEGIN DESCRIPTION:
Sandy Creek 97.0
END DESCRIPTION:
#Sta/Elev= 25
  4429.7  222.12  4569.7  216.04  4639.7  213.68  4699.7   209.7  4799.7   199.6
  4899.7     194  4909.7  193.81  4929.7  194.42  4949.7  193.59  4959.7  192.69
  4961.5  188.11  4964.5  182.11  5035.6  182.11  5038.6  188.11  5069.7  194.02
  5089.7  194.99  5099.7  196.37  5109.7  199.01  5119.7  202.21  5139.7   212.8
  5149.7  216.73  5159.7  221.47  5169.7  225.41  5179.7  226.98  5200.9  231.29
#Mann= 3 , 1 , 0
 4429.70    0.13       0  4961.5   0.042       0  5038.6    0.13       0
Bank Sta=4961.50,5038.60
Exp/Cntr=0.3,0.1

Type RM Length L Ch R = 1 ,95782.9,1080.9,1080.9,1080.9
BEGIN DESCRIPTION:
Sandy Creek 96.0
END DESCRIPTION:
#Sta/Elev= 20
  4512.9  220.92  4562.9  214.33  4572.9  213.33  4582.9  213.22  4722.9  202.21
  4762.9  198.11  4792.9   196.2  4812.9  196.01  4832.9  195.05  4932.9  195.84
  4942.9  195.54  4952.9  194.57  4961.5  187.82  4964.5  181.82  5035.5  181.82
  5038.5  187.82  5055.1  194.36  5075.1  195.57  5175.1  209.01  5227.2  218.94
#Mann= 3 , 1 , 0
 4512.90    0.13       0  4961.5   0.042       0  5038.5    0.13       0
Bank Sta=4961.50,5038.50
Exp/Cntr=0.3,0.1

Type RM Length L Ch R = 1 ,94702.0,53,53,53
BEGIN DESCRIPTION:
Upstream Section of Bridge/Culvert/Weir
END DESCRIPTION:
#Sta/Elev= 24
  4560.9  214.23  4570.9  210.01  4620.9  207.69  4630.9   207.7  4650.9  206.03
  4670.9  207.04  4690.9  206.08  4700.9  206.39  4830.9  202.19  4900.9  196.28
  4920.9  195.93  4940.9  194.44  4950.9  190.12    4971  187.53    4973  181.53
    5027  181.53    5029  187.53  5035.9  190.66  5045.9  191.87  5095.9  200.34
  5105.9  201.86  5115.9  204.52  5175.9  212.82  5191.7  211.98
#Mann= 3 , 1 , 0
 4560.90    0.13       0    4971   0.045       0    5029    0.13       0
#XS Ineff= 2 , 0
       0  4920.8   199.1 5079.09       0   199.1
Bank Sta=4971.00,5029.00
Exp/Cntr=0.5,0.3

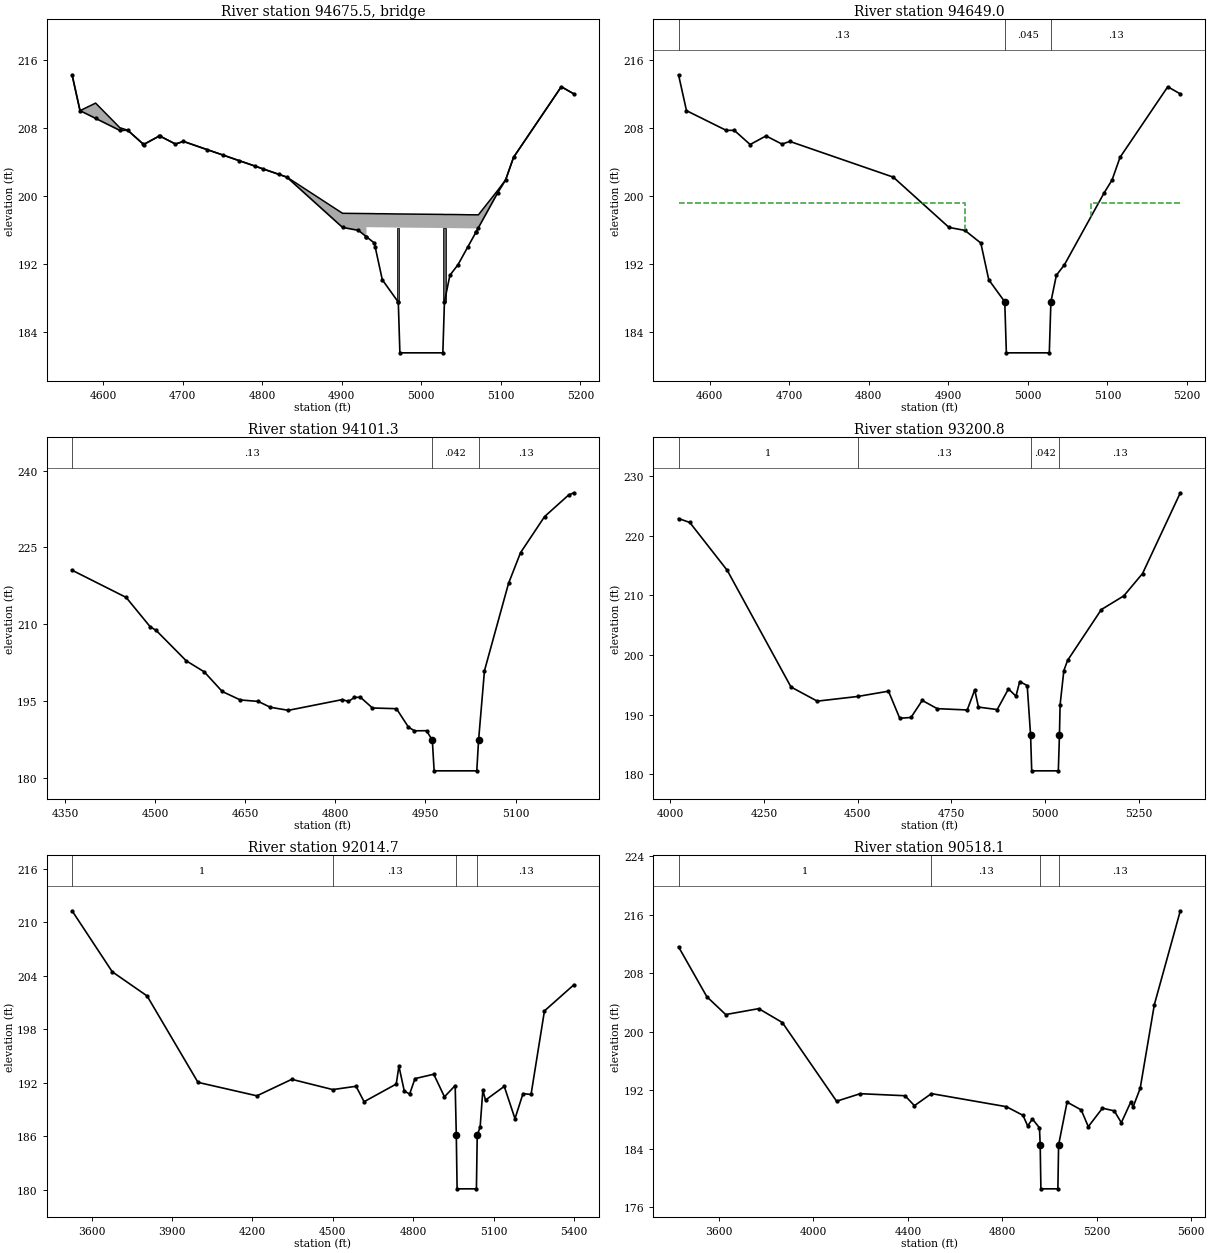
Type RM Length L Ch R = 3 ,94675.5,,,
BEGIN DESCRIPTION:
NC 58-3-TOR
Structure ID: NC 58_sandy-Bridge
Approximate Survey Structure
END DESCRIPTION:
Bridge Culvert--1,0,-1,-1, 0
Deck Dist Width WeirC Skew NumUp NumDn MinLoCord MaxHiCord MaxSubmerge Is_Ogee
10,33,2.6,,41,41,,,0.95,0,1,1,,
  4560.9  4570.9  4590.5  4620.9  4630.9  4650.5  4650.9  4670.5  4670.9  4690.9
  4700.9  4730.5  4750.5  4770.5  4790.5  4800.5  4820.5  4830.9  4900.9  4920.9
 4930.91    4931  4940.9    4942  4950.9  4970.9    4971    4973    5027    5029
  5035.9  5045.9    5058 5068.89    5069  5071.7  5095.9  5105.9  5115.9  5175.9
  5191.7
  214.22     210  210.89     208   207.7  206.06  206.03  207.02  207.04  206.08
  206.39  205.43  204.79  204.14   203.5  203.17  202.53  202.19  197.93  197.91
   197.9   197.9  197.89  197.88  197.88  197.85  197.85  197.85   197.8  197.79
  197.79  197.78  197.76  197.75  197.75  197.75  200.62  201.86  204.52  212.82
  211.97
  214.22     210  209.09  207.68  207.69  206.05  206.02  207.01  207.03  206.07
  206.38  205.42  204.78  204.13  203.49  203.16  202.52  202.18  196.27  195.92
  195.17   196.3  196.29  196.28  196.28  196.25  196.25  196.25   196.2  196.19
  196.19  196.18  196.16  196.15  195.77  196.23  200.33  201.85  204.51  212.81
  211.97
  4560.9  4570.9  4590.5  4620.9  4630.9  4650.5  4650.9  4670.5  4670.9  4690.9
  4700.9  4730.5  4750.5  4770.5  4790.5  4800.5  4820.5  4830.9  4900.9  4920.9
 4930.91    4931  4940.9    4942  4950.9  4970.9    4971    4973    5027    5029
  5035.9  5045.9    5058 5068.89    5069  5071.7  5095.9  5105.9  5115.9  5175.9
  5191.7
  214.22     210  210.89     208   207.7  206.06  206.03  207.02  207.04  206.08
  206.39  205.43  204.79  204.14   203.5  203.17  202.53  202.19  197.93  197.91
   197.9   197.9  197.89  197.88  197.88  197.85  197.85  197.85   197.8  197.79
  197.79  197.78  197.76  197.75  197.75  197.75  200.62  201.86  204.52  212.82
  211.97
  214.21  209.99  209.08  207.67  207.68  206.04  206.01     207  207.02  206.06
  206.37  205.41  204.77  204.12  203.48  203.15  202.51  202.17  196.26  195.91
  195.16  196.29  196.28  196.27  196.27  196.24  196.24  196.24  196.19  196.18
  196.18  196.17  196.15  196.14  195.76  196.22  200.32  201.84   204.5   212.8
  211.96
Pier Skew, UpSta & Num, DnSta & Num=,4971.0, 2 ,4971.0, 2 , 0 , 0 , 0 ,,
       3       3
  182.02  197.25
       3       3
  182.01  197.24
Pier Skew, UpSta & Num, DnSta & Num=,5029.0, 2 ,5029.0, 2 , 0 , 0 , 0 ,,
       3       3
  182.02   197.2
       3       3
  182.01  197.19
Abutment Skew #Up #Dn=, 2 , 2
 4930.80 4942.00
  196.30  193.95
 4930.80 4942.00
  196.29  193.94
Abutment Skew #Up #Dn=, 2 , 2
 5058.00 5069.09
  193.91  196.15
 5058.00 5069.09
  193.90  196.14
BR Coef= 1 , 1 , 0 ,1.25, 0 ,,,0.8,0,2,0,
Wspro=,,,, 1 ,,,, 0 ,,,, 0 ,,,,-1 ,-1 ,-1 , 0 , 0 , 0 , 0 , 0
BC Design=,, 0 ,, 0 ,,,,,,
BR U #Sta/Elev= 41
  4560.9  214.22  4570.9     210  4590.5  209.09  4620.9  207.68  4630.9  207.69
  4650.5  206.05  4650.9  206.02  4670.5  207.01  4670.9  207.03  4690.9  206.07
  4700.9  206.38  4730.5  205.42  4750.5  204.78  4770.5  204.13  4790.5  203.49
  4800.5  203.16  4820.5  202.52  4830.9  202.18  4900.9  196.27  4920.9  195.92
 4930.91  195.17    4931  195.17  4940.9  194.43    4942  193.95  4950.9  190.11
  4970.9   187.5    4971  187.52    4973  181.52    5027  181.52    5029  187.52
  5035.9  190.65  5045.9  191.86    5058  193.91 5068.89  195.75    5069  195.77
  5071.7  196.23  5095.9  200.33  5105.9  201.85  5115.9  204.51  5175.9  212.81
  5191.7  211.97
BR U #Mann= 3
 4560.90    0.13    4971   0.045    5029    0.13
BR U Banks=4971.00,5029.00
BR D #Sta/Elev= 41
  4560.9  214.21  4570.9  209.99  4590.5  209.08  4620.9  207.67  4630.9  207.68
  4650.5  206.04  4650.9  206.01  4670.5     207  4670.9  207.02  4690.9  206.06
  4700.9  206.37  4730.5  205.41  4750.5  204.77  4770.5  204.12  4790.5  203.48
  4800.5  203.15  4820.5  202.51  4830.9  202.17  4900.9  196.26  4920.9  195.91
 4930.91  195.16    4931  195.16  4940.9  194.42    4942  193.94  4950.9   190.1
  4970.9  187.49    4971  187.51    4973  181.51    5027  181.51    5029  187.51
  5035.9  190.64  5045.9  191.85    5058   193.9 5068.89  195.74    5069  195.76
  5071.7  196.22  5095.9  200.32  5105.9  201.84  5115.9   204.5  5175.9   212.8
  5191.7  211.96
BR D #Mann= 3
 4560.90    0.13    4971   0.045    5029    0.13
BR D Banks=4971.00,5029.00

Type RM Length L Ch R = 1 ,94649.0,547.7,547.7,547.7
BEGIN DESCRIPTION:
Downstream Section of Bridge/Culvert/Weir
END DESCRIPTION:
#Sta/Elev= 24
  4560.9  214.21  4570.9  209.99  4620.9  207.67  4630.9  207.68  4650.9  206.01
  4670.9  207.02  4690.9  206.06  4700.9  206.37  4830.9  202.17  4900.9  196.26
  4920.9  195.91  4940.9  194.42  4950.9   190.1    4971  187.51    4973  181.51
    5027  181.51    5029  187.51  5035.9  190.64  5045.9  191.85  5095.9  200.32
  5105.9  201.84  5115.9   204.5  5175.9   212.8  5191.7  211.96
#Mann= 3 , 1 , 0
 4560.90    0.13       0    4971   0.045       0    5029    0.13       0
#XS Ineff= 2 , 0
       0  4920.8   199.1 5079.09       0   199.1
Bank Sta=4971.00,5029.00
Exp/Cntr=0.5,0.3

Type RM Length L Ch R = 1 ,94101.3,900.5,900.5,900.5
BEGIN DESCRIPTION:
Sandy Creek 94.0
END DESCRIPTION:
#Sta/Elev= 30
  4361.8  220.55  4451.8  215.24  4491.8  209.51  4501.8  208.79  4551.8  202.86
  4581.8   200.7  4611.8  196.86  4641.8  195.21  4671.8  194.92  4691.8  193.78
  4721.8  193.18  4811.8  195.28  4821.8  194.91  4831.8   195.7  4841.8  195.74
  4861.8  193.64  4901.8   193.5  4921.8  189.89  4931.8  189.18  4951.8   189.2
  4961.5  187.36  4964.5  181.36  5035.5  181.36  5038.5  187.36  5048.3  200.92
  5088.3  217.96  5108.3  223.97  5148.3  231.02  5188.3  235.24  5197.1  235.68
#Mann= 3 , 1 , 0
 4361.80    0.13       0  4961.5   0.042       0  5038.5    0.13       0
Bank Sta=4961.50,5038.50
Exp/Cntr=0.3,0.1

Type RM Length L Ch R = 1 ,93200.8,1186.1,1186.1,1186.1
BEGIN DESCRIPTION:
Sandy Creek 93.0
END DESCRIPTION:
#Sta/Elev= 30
  4022.5  222.89  4052.5  222.23  4152.5  214.19  4322.5  194.63  4392.5  192.26
  4499.9  193.04  4582.5  193.93  4612.5  189.39  4642.5  189.52  4672.5  192.38
  4712.5     191  4792.5  190.78  4812.5  194.14  4822.5  191.26  4872.5  190.85
  4902.5  194.31  4922.5  193.09  4932.5  195.55  4952.5  194.87  4961.5  186.57
  4964.5  180.57  5035.5  180.57  5038.5  186.57  5040.2  191.62  5050.2  197.38
  5060.2   199.1  5150.2  207.62  5210.2  209.92  5260.2  213.67  5360.9  227.21
#Mann= 4 , 1 , 0
 4022.50       1       0  4499.9    0.13       0  4961.5   0.042       0
  5038.5    0.13       0
Bank Sta=4961.50,5038.50
Exp/Cntr=0.3,0.1

Type RM Length L Ch R = 1 ,92014.7,1496.6,1496.6,1496.6
BEGIN DESCRIPTION:
Sandy Creek 92.0
END DESCRIPTION:
#Sta/Elev= 30
  3526.8  211.28  3676.8  204.44  3806.8  201.73  3996.8  192.04  4216.8  190.53
  4346.8  192.38  4499.9  191.23  4586.8   191.6  4616.8  189.87  4736.8  191.85
  4746.8  193.85  4766.8  191.07  4786.8  190.73  4806.8  192.46  4876.8  192.95
  4916.8  190.42  4956.8  191.68    4961   186.1    4964   180.1  5036.1   180.1
  5039.1   186.1    5050  187.04    5060  191.16    5070  190.05    5140  191.59
    5180  187.97    5210  190.78    5240  190.68    5290  200.05  5399.8  202.98
#Mann= 4 , 1 , 0
 3526.80       1       0  4499.9    0.13       0    4961   0.042       0
  5039.1    0.13       0
Bank Sta=4961.00,5039.10
Exp/Cntr=0.3,0.1

Type RM Length L Ch R = 1 ,90518.1,724.7,724.7,724.7
BEGIN DESCRIPTION:
Sandy Creek 90.0
END DESCRIPTION:
#Sta/Elev= 30
    3428  211.59    3548  204.77    3628  202.33    3768  203.14    3868  201.24
    4098  190.48    4198  191.51    4388  191.23    4428  189.87  4499.9  191.52
    4818  189.73    4888  188.55    4908   187.1    4928  188.05    4958  186.84
    4961   184.5    4964   178.5    5036   178.5    5039   184.5  5074.9  190.36
  5134.9  189.29  5164.9     187  5224.9  189.53  5274.9  189.16  5304.9  187.55
  5344.9  190.36  5354.9  189.71  5384.9  192.25  5444.9  203.69    5555  216.52
#Mann= 4 , 1 , 0
 3428.00       1       0  4499.9    0.13       0    4961   0.042       0
    5039    0.13       0
Bank Sta=4961.00,5039.00
Exp/Cntr=0.3,0.1

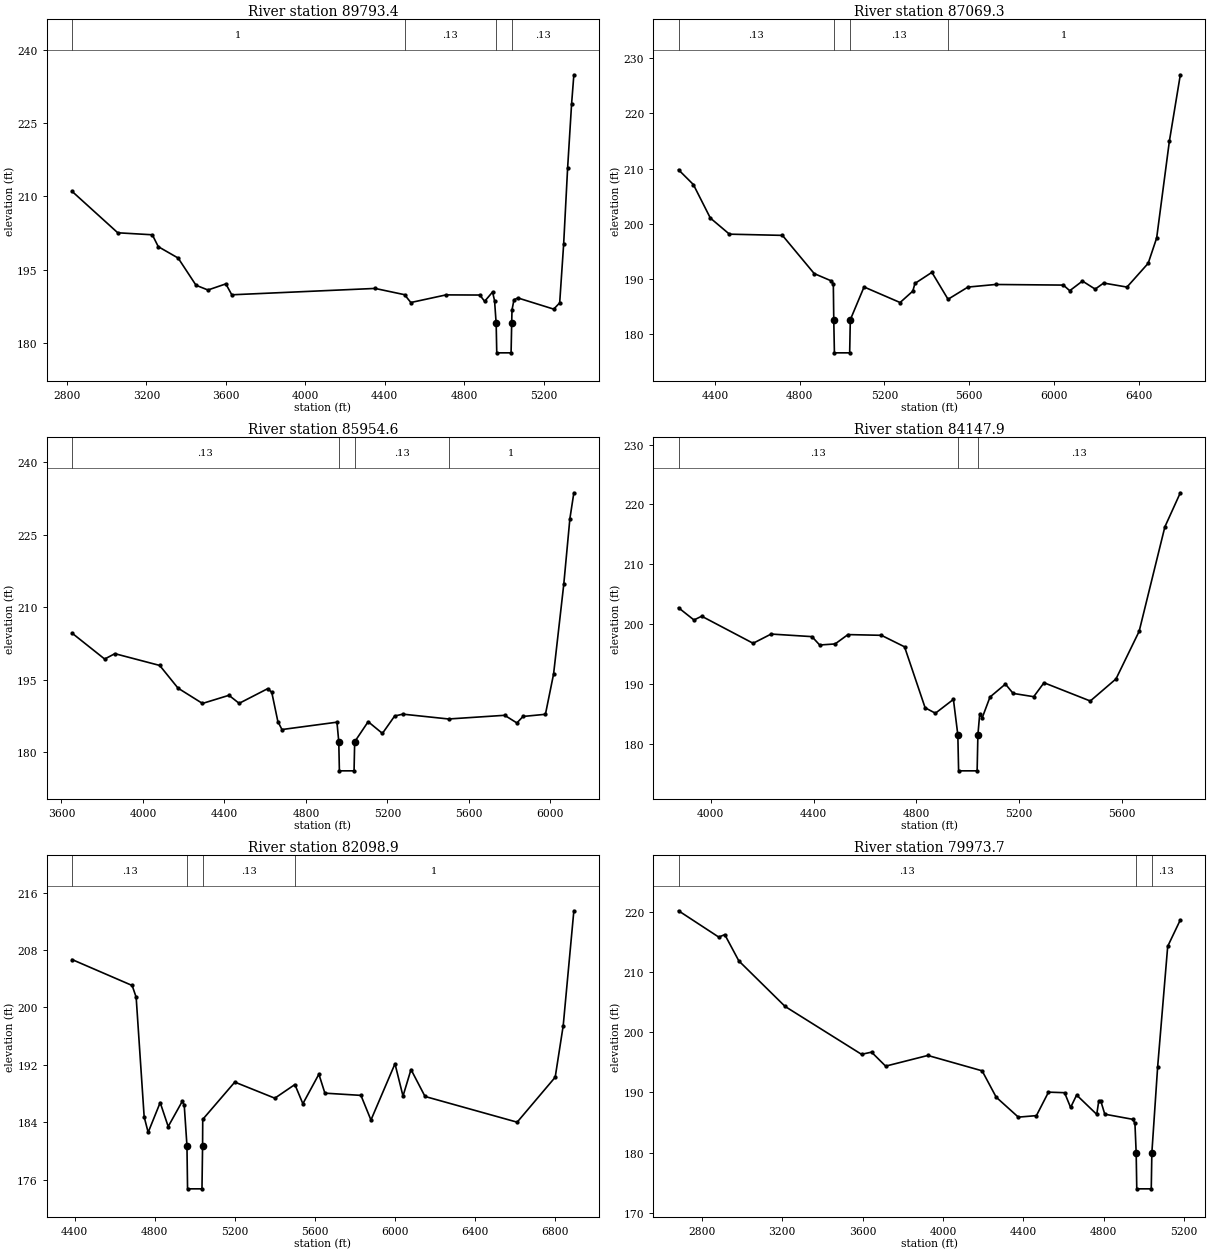
Type RM Length L Ch R = 1 ,89793.4,2724.1,2724.1,2724.1
BEGIN DESCRIPTION:
Sandy Creek 89.0
END DESCRIPTION:
#Sta/Elev= 30
  2826.2  211.01  3056.2  202.54  3230.2  202.13  3260.2   199.7  3360.2  197.37
  3450.2  191.81  3510.2  190.84  3600.2  192.09  3630.2  189.86  4351.5  191.16
  4499.9  189.88  4531.5  188.28  4708.8  189.84  4878.8  189.81  4902.9  188.52
  4942.9  190.43  4952.9  188.66    4961  183.99    4964  177.99  5036.1  177.99
  5039.1  183.99  5040.7  186.75  5050.7  188.85  5070.7  189.21  5250.7  186.93
  5280.7  188.21  5300.7  200.21  5320.7   215.8  5340.7   228.9  5352.1  234.85
#Mann= 4 , 1 , 0
 2826.20       1       0  4499.9    0.13       0    4961   0.042       0
  5039.1    0.13       0
Bank Sta=4961.00,5039.10
Exp/Cntr=0.3,0.1

Type RM Length L Ch R = 1 ,87069.3,1114.7,1114.7,1114.7
BEGIN DESCRIPTION:
Sandy Creek 87.0
END DESCRIPTION:
#Sta/Elev= 30
  4228.9  209.79  4298.9  207.11  4378.9  201.04  4468.9  198.12  4718.9   197.9
  4868.9  190.97  4948.9  189.66  4958.9   189.1    4961  182.61    4964  176.61
    5036  176.61    5039  182.61  5103.8  188.55  5273.8  185.73  5333.8   187.8
  5343.8  189.19  5423.8   191.2  5499.9  186.32  5593.8  188.53  5723.8     189
  6043.8  188.89  6073.8  187.87  6133.8  189.62  6193.8  188.16  6233.8  189.26
  6343.8  188.53  6443.8  192.84  6483.8  197.43  6543.8  214.99  6595.4  227.01
#Mann= 4 , 1 , 0
 4228.90    0.13       0    4961   0.042       0    5039    0.13       0
  5499.9       1       0
Bank Sta=4961.00,5039.00
Exp/Cntr=0.3,0.1

Type RM Length L Ch R = 1 ,85954.6,1806.7,1806.7,1806.7
BEGIN DESCRIPTION:
Sandy Creek 86.0
END DESCRIPTION:
#Sta/Elev= 30
  3652.1  204.63  3812.1  199.28  3862.1  200.39  4082.1  197.96  4172.1  193.27
  4292.1  190.11  4422.1  191.79  4472.1  190.13  4612.1  193.16  4632.1  192.42
  4662.1  186.37  4682.1  184.72  4952.1  186.24    4961  182.19    4964  176.19
    5036  176.19    5039  182.19  5105.2  186.34  5175.2  183.92  5235.2  187.51
  5275.2   187.9  5499.9   186.9  5775.2  187.66  5835.2  186.08  5865.2  187.42
  5975.2  187.87  6015.2  196.19  6065.2  214.72  6095.2  228.28  6114.7  233.62
#Mann= 4 , 1 , 0
 3652.10    0.13       0    4961   0.042       0    5039    0.13       0
  5499.9       1       0
Bank Sta=4961.00,5039.00
Exp/Cntr=0.3,0.1

Type RM Length L Ch R = 1 ,84147.9,2049,2049,2049
BEGIN DESCRIPTION:
Sandy Creek 84.0
END DESCRIPTION:
#Sta/Elev= 30
    3875  202.75    3935  200.71    3965  201.34    4165  196.82    4235  198.36
  4393.8  197.93  4423.8  196.53  4483.8  196.71  4533.8  198.27  4663.8  198.15
  4753.8  196.23  4833.8  186.05  4873.8  185.14  4943.8  187.45    4961  181.52
    4964  175.52    5036  175.52    5039  181.52    5046  184.99    5056   184.4
    5086  187.84    5146  190.01    5176  188.45    5256   187.9    5296  190.23
    5476  187.18    5576  190.87    5666  198.82    5766  216.26  5826.1  221.95
#Mann= 3 , 1 , 0
 3875.00    0.13       0    4961   0.042       0    5039    0.13       0
Bank Sta=4961.00,5039.00
Exp/Cntr=0.3,0.1

Type RM Length L Ch R = 1 ,82098.9,2125.2,2125.2,2125.2
BEGIN DESCRIPTION:
Sandy Creek 82.0
END DESCRIPTION:
#Sta/Elev= 30
  4387.3  206.67  4687.3  203.06  4707.3  201.43  4747.3  184.77  4767.3  182.61
  4827.3  186.76  4867.3  183.42  4937.3  186.92  4947.3  186.44    4961  180.75
    4964  174.75    5036  174.75    5039  180.75  5039.8  184.42  5199.8  189.61
  5399.8  187.37  5499.9  189.27  5539.8   186.6  5619.8  190.71  5649.8  188.07
  5829.8  187.76  5879.8  184.33  5999.8  192.16  6039.8  187.66  6079.8  191.36
  6149.8  187.61  6609.8  184.03  6799.8  190.29  6839.8  197.46    6893  213.46
#Mann= 4 , 1 , 0
 4387.30    0.13       0    4961   0.042       0    5039    0.13       0
  5499.9       1       0
Bank Sta=4961.00,5039.00
Exp/Cntr=0.3,0.1

Type RM Length L Ch R = 1 ,79973.7,983.5,983.5,983.5
BEGIN DESCRIPTION:
Sandy Creek 80.0
END DESCRIPTION:
#Sta/Elev= 30
    2685  220.25    2885  215.87    2915  216.28    2985   211.9    3215  204.32
    3595  196.35    3645  196.71    3715  194.38  3924.9  196.16  4194.9   193.6
  4264.9  189.21  4374.9  185.89  4464.9  186.14  4524.9  190.05  4604.9  189.96
  4634.9   187.5  4664.9  189.57  4764.9  186.35  4774.9  188.56  4784.9  188.59
  4804.9  186.38  4944.9  185.52  4954.9  184.84    4961  179.95    4964  173.95
    5036  173.95    5039  179.95  5067.8  194.26  5117.8  214.33  5180.6  218.73
#Mann= 3 , 1 , 0
 2685.00    0.13       0    4961   0.042       0    5039    0.13       0
Bank Sta=4961.00,5039.00
Exp/Cntr=0.3,0.1

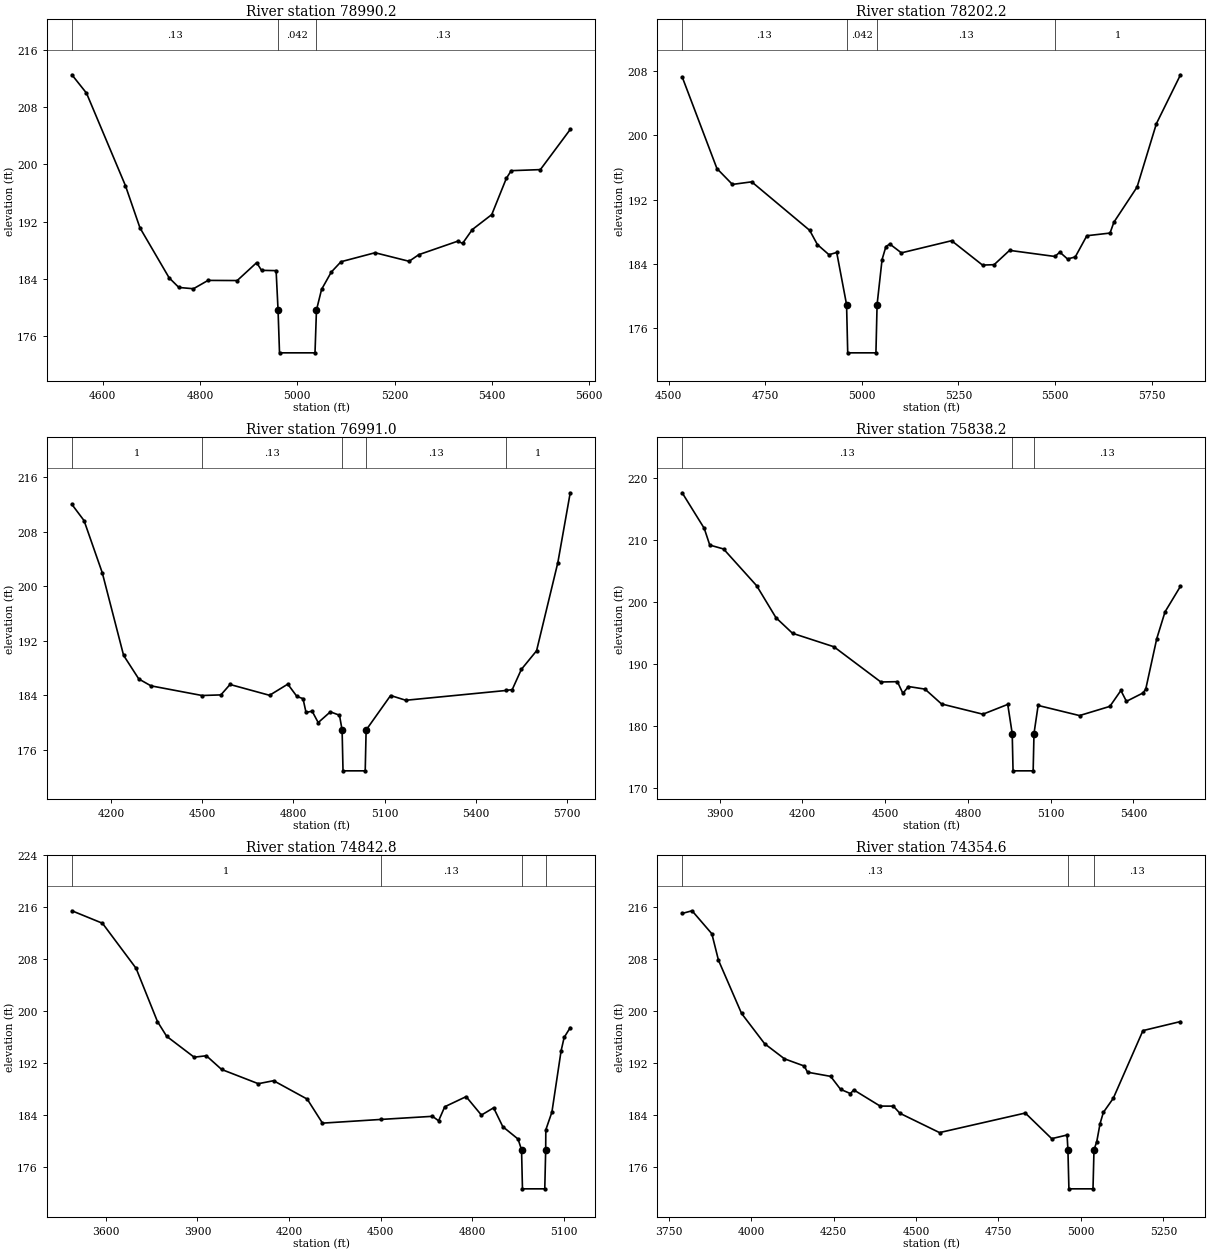
Type RM Length L Ch R = 1 ,78990.2,788,788,788
BEGIN DESCRIPTION:
Sandy Creek 79.0
END DESCRIPTION:
#Sta/Elev= 30
  4536.5  212.58  4566.5  210.01  4646.5  197.05  4676.5  191.11  4736.5   184.1
  4756.5  182.75  4786.5  182.57  4816.5  183.74  4876.5  183.72  4916.5  186.23
  4926.5  185.15  4956.5  185.11  4960.5  179.58  4963.5  173.58  5036.5  173.58
  5039.5  179.58    5050  182.48    5070  184.91    5090  186.36    5160  187.62
    5230  186.42    5250  187.35    5330  189.24    5340  188.93    5360  190.87
    5400  192.97    5430  198.05    5440  199.13    5500  199.28  5561.4  204.91
#Mann= 3 , 1 , 0
 4536.50    0.13       0  4960.5   0.042       0  5039.5    0.13       0
Bank Sta=4960.50,5039.50
Exp/Cntr=0.3,0.1

Type RM Length L Ch R = 1 ,78202.2,1211.2,1211.2,1211.2
BEGIN DESCRIPTION:
Sandy Creek 78.0
END DESCRIPTION:
#Sta/Elev= 30
    4535  207.28    4625  195.88    4665  193.91    4715  194.23    4865   188.2
    4885  186.43    4915  185.17    4935  185.45  4960.5  178.97  4963.5  172.97
  5036.5  172.97  5039.5  178.97  5052.4  184.57  5062.4  186.19  5072.4   186.5
  5102.4   185.4  5232.4  186.91  5312.4  183.88  5342.4  183.93  5382.4  185.71
  5499.9  184.95  5512.4  185.49  5532.4  184.64  5552.4  184.89  5582.4  187.53
  5642.4  187.86  5652.4  189.21  5712.4  193.58  5762.4  201.46  5824.8  207.54
#Mann= 4 , 1 , 0
 4535.00    0.13       0  4960.5   0.042       0  5039.5    0.13       0
  5499.9       1       0
Bank Sta=4960.50,5039.50
Exp/Cntr=0.3,0.1

Type RM Length L Ch R = 1 ,76991.0,1152.8,1152.8,1152.8
BEGIN DESCRIPTION:
Sandy Creek 77.0
END DESCRIPTION:
#Sta/Elev= 30
  4071.9  212.02  4111.9  209.64  4171.9  201.96  4241.9  189.84  4291.9  186.37
  4331.9  185.36  4499.9  183.94  4561.9  184.03  4591.9  185.56  4721.9  183.97
  4781.9  185.61  4811.9   183.8  4831.9  183.48  4841.9  181.45  4861.9  181.64
  4881.9  179.96  4921.9  181.54  4951.9  181.04  4960.5  178.87  4963.5  172.87
  5036.5  172.87  5039.5  178.87    5120  183.94    5170  183.24  5499.9  184.68
    5520  184.81    5550  187.78    5600  190.51    5670  203.48  5710.7  213.73
#Mann= 5 , 1 , 0
 4071.90       1       0  4499.9    0.13       0  4960.5   0.042       0
  5039.5    0.13       0  5499.9       1       0
Bank Sta=4960.50,5039.50
Exp/Cntr=0.3,0.1

Type RM Length L Ch R = 1 ,75838.2,995.4,995.4,995.4
BEGIN DESCRIPTION:
Sandy Creek 76.0
END DESCRIPTION:
#Sta/Elev= 30
  3764.4  217.55  3844.4  211.82  3864.4  209.13  3914.4   208.5  4034.4  202.58
  4104.4  197.43  4164.4  194.92  4314.4  192.75  4484.4  187.08  4544.4  187.13
  4564.4  185.25  4584.4  186.35  4644.4  185.93  4704.4  183.54  4854.4  181.89
  4944.4  183.47  4960.6  178.77  4963.6  172.77  5036.5  172.77  5039.5  178.77
  5054.5   183.3  5204.5  181.67  5314.5  183.15  5354.5  185.71  5374.5  183.96
  5434.5  185.31  5444.5  185.92  5484.5  194.07  5514.5  198.38  5570.5   202.5
#Mann= 3 , 1 , 0
 3764.40    0.13       0  4960.6   0.042       0  5039.5    0.13       0
Bank Sta=4960.60,5039.50
Exp/Cntr=0.3,0.1

Type RM Length L Ch R = 1 ,74842.8,488.2,488.2,488.2
BEGIN DESCRIPTION:
Sandy Creek 75.0
END DESCRIPTION:
#Sta/Elev= 30
  3489.1  215.48  3589.1  213.56  3699.1  206.63  3769.1  198.43  3799.1  196.17
  3889.1  192.95  3929.1  193.17  3979.1  191.06  4099.1  188.87  4149.1  189.33
  4259.1   186.5  4309.1   182.8  4499.9  183.37  4669.1  183.85  4689.1  183.16
  4709.1  185.32  4779.1  186.88  4829.1  184.04  4869.1  185.16  4899.1  182.26
  4949.1  180.35  4960.5  178.69  4963.5  172.69  5036.5  172.69  5039.5  178.69
  5039.9  181.77  5059.9  184.51  5089.9  193.92  5099.9  195.99  5119.8   197.5
#Mann= 4 , 1 , 0
 3489.10       1       0  4499.9    0.13       0  4960.5   0.042       0
  5039.5    0.13       0
Bank Sta=4960.50,5039.50
Exp/Cntr=0.3,0.1

Type RM Length L Ch R = 1 ,74354.6,1165.9,1165.9,1165.9
BEGIN DESCRIPTION:
Sandy Creek 74.0
END DESCRIPTION:
#Sta/Elev= 30
  3791.3  215.01  3821.3  215.42  3881.3  211.88  3901.3  207.82  3971.3  199.63
  4041.3  194.97  4101.3  192.65  4161.3  191.54  4171.3  190.59  4241.3  189.95
  4271.3  187.96  4301.3   187.3  4311.3  187.87  4391.3  185.38  4431.3  185.37
  4451.3  184.27  4571.3   181.3  4831.3  184.31  4911.3  180.37  4957.9  180.93
  4960.5  178.65  4963.5  172.65  5036.5  172.65  5039.5  178.65  5047.9  179.91
  5057.9  182.68  5067.9  184.41  5097.9  186.57  5187.9  196.99  5301.7  198.38
#Mann= 3 , 1 , 0
 3791.30    0.13       0  4960.5   0.042       0  5039.5    0.13       0
Bank Sta=4960.50,5039.50
Exp/Cntr=0.3,0.1