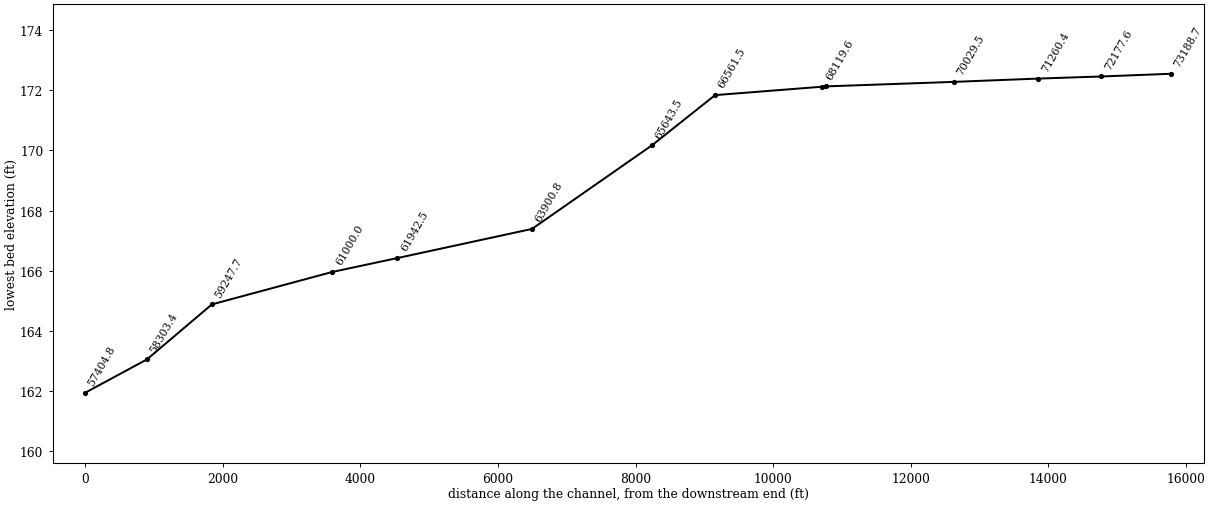
HEC-RAS study 020822_SANDY_CREEK.prj: Sandy Creek

--- 020822_SANDY_CREEK.g01 (geometry) --- (continued)

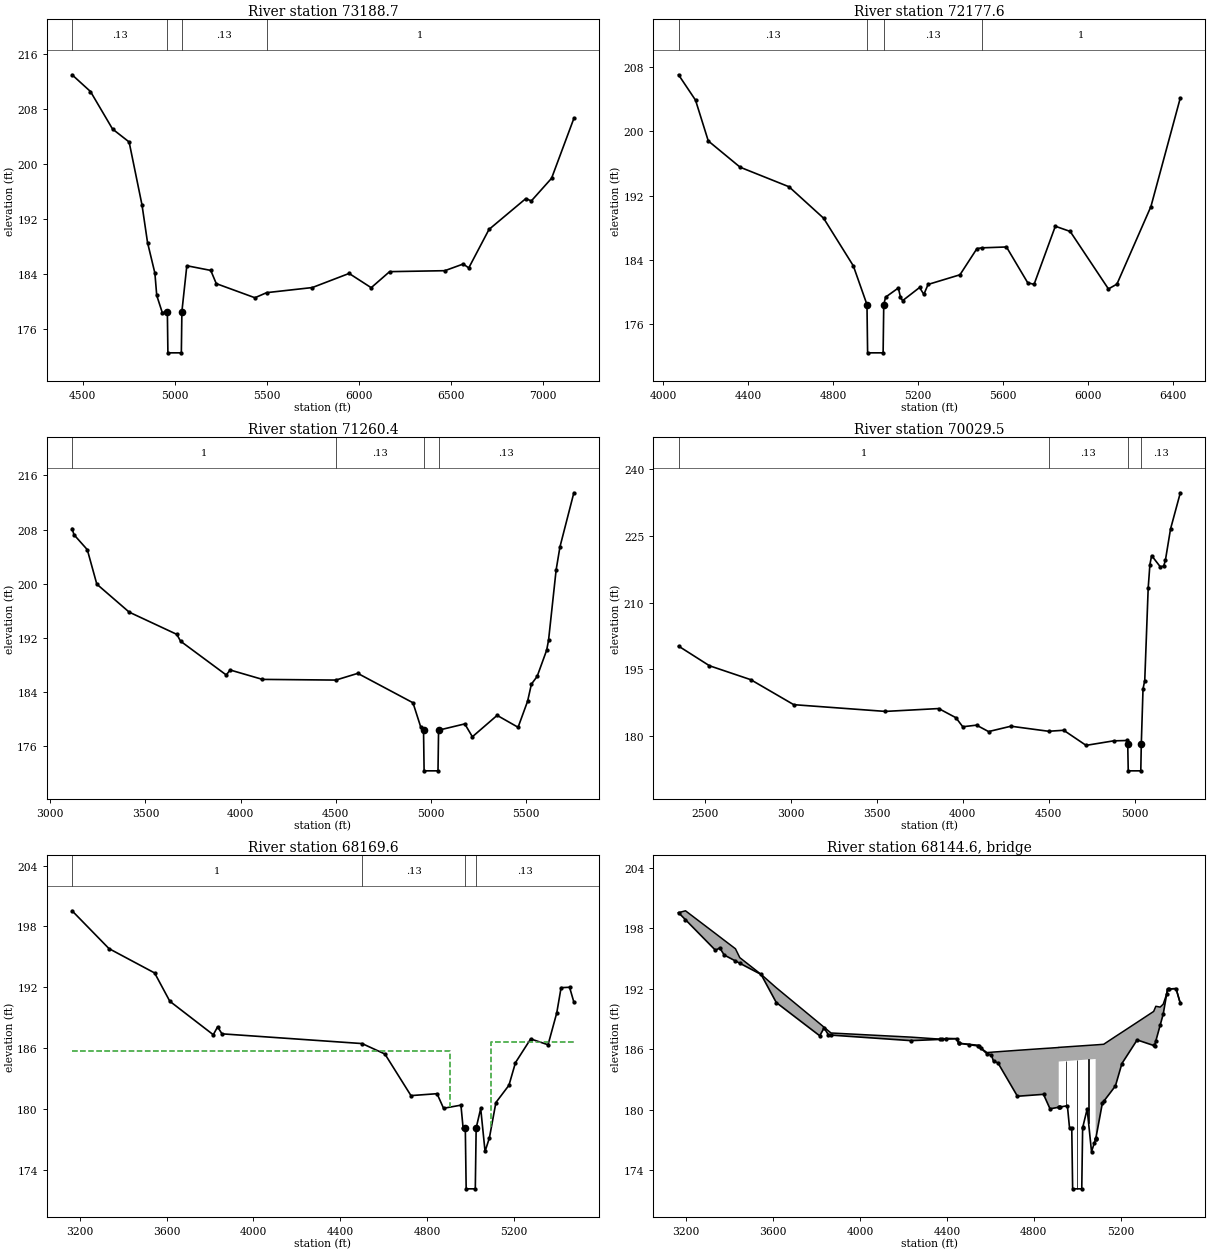
Type RM Length L Ch R = 1 ,73188.7,1011.1,1011.1,1011.1
BEGIN DESCRIPTION:
Sandy Creek 73.7
END DESCRIPTION:
#Sta/Elev= 30
  4442.8  212.93  4542.8   210.5  4662.8  205.05  4752.8  203.17  4822.8  194.02
  4852.8  188.57  4892.8  184.12  4902.8  180.89  4932.8   178.4  4960.5  178.55
  4963.5  172.55  5036.5  172.55  5039.5  178.55  5066.3   185.2  5196.3  184.52
  5226.3   182.6  5436.3  180.55  5499.9  181.29    5748  182.03    5948  184.08
    6068  182.01    6168  184.34    6468  184.48    6568  185.45    6598  184.88
    6708  190.47    6908  194.95    6938  194.61    7048   197.9  7169.1  206.59
#Mann= 4 , 1 , 0
 4442.80    0.13       0  4960.5   0.042       0  5039.5    0.13       0
  5499.9       1       0
Bank Sta=4960.50,5039.50
Exp/Cntr=0.3,0.1

Type RM Length L Ch R = 1 ,72177.6,917.2,917.2,917.2
BEGIN DESCRIPTION:
Sandy Creek  73.5
END DESCRIPTION:
#Sta/Elev= 30
  4073.5  207.05  4153.5  203.89  4213.5  198.82  4363.5  195.55  4593.5  193.12
  4756.3  189.21  4896.3  183.28  4960.5  178.46  4963.5  172.46  5036.5  172.46
  5039.5  178.46  5048.2  179.39  5108.2  180.53  5118.2  179.37  5128.2  178.95
  5208.2  180.59  5228.2  179.73  5248.2  180.97  5398.2  182.17  5478.2  185.43
  5499.9  185.52  5617.1  185.63  5717.1  181.18  5747.1  180.98  5847.1  188.21
  5917.1  187.56  6097.1  180.41  6137.1  181.01  6297.1  190.66  6435.5  204.18
#Mann= 4 , 1 , 0
 4073.50    0.13       0  4960.5   0.042       0  5039.5    0.13       0
  5499.9       1       0
Bank Sta=4960.50,5039.50
Exp/Cntr=0.3,0.1

Type RM Length L Ch R = 1 ,71260.4,1230.9,1230.9,1230.9
BEGIN DESCRIPTION:
Sandy Creek 73.0
END DESCRIPTION:
#Sta/Elev= 30
  3114.4  208.16  3124.4  207.25  3194.4  205.04  3244.4  199.95  3414.4  195.82
  3664.4  192.54  3684.4  191.53  3924.4  186.54  3944.4  187.28  4114.4  185.89
  4499.9  185.79    4615  186.78    4905  182.44    4945  178.93  4960.5  178.39
  4963.5  172.39  5036.5  172.39  5039.5  178.39  5177.1  179.32  5217.1  177.42
  5347.1  180.58  5457.1  178.82  5507.1  182.67  5527.1  185.19  5557.1  186.32
  5607.1  190.19  5617.1  191.66  5657.1  202.08  5677.1  205.46  5750.1  213.44
#Mann= 4 , 1 , 0
 3114.40       1       0  4499.9    0.13       0  4960.5   0.042       0
  5039.5    0.13       0
Bank Sta=4960.50,5039.50
Exp/Cntr=0.3,0.1

Type RM Length L Ch R = 1 ,70029.5,1859.9,1859.9,1859.9
BEGIN DESCRIPTION:
Sandy Creek 66.5
END DESCRIPTION:
#Sta/Elev= 30
  2348.2  200.24  2528.2  195.83  2768.2  192.71  3018.2  187.11  3551.2   185.6
  3861.2  186.24  3961.2  184.19  4001.2  182.16  4081.2  182.52  4151.2  181.08
  4281.2  182.28  4499.9  181.15  4588.3  181.37  4718.3  177.99  4878.3     179
  4958.3  179.08  4960.5  178.28  4963.5  172.28  5036.5  172.28  5039.4  178.28
  5049.5  190.67  5059.5  192.52  5079.5  213.24  5089.5  218.52  5099.5  220.52
  5149.5  218.03  5169.5  218.16  5179.5  219.46  5209.5  226.49  5266.4   234.6
#Mann= 4 , 1 , 0
 2348.20       1       0  4499.9    0.13       0  4960.5   0.042       0
  5039.4    0.13       0
Bank Sta=4960.50,5039.40
Exp/Cntr=0.3,0.1

Type RM Length L Ch R = 1 ,68169.6,50,50,50
BEGIN DESCRIPTION:
Upstream Section of Bridge/Culvert/Weir
END DESCRIPTION:
#Sta/Elev= 30
  3164.9  199.54  3334.9  195.81  3544.9  193.41  3614.9  190.62  3814.9  187.32
  3834.9   188.1  3854.9  187.41  4499.9  186.45  4604.9  185.42  4724.9  181.32
  4844.9  181.51  4874.9  180.07  4954.9  180.38  4964.9  178.12    4975  178.13
    4979  172.13    5021  172.13    5025  178.13  5045.9  180.05  5065.9  175.82
  5085.9  177.15  5115.9  180.64  5175.9  182.34  5205.9  184.57  5275.9  186.91
  5355.9  186.33  5395.9  189.47  5415.9  191.96    5455     192  5474.7  190.54
#Mann= 4 , 1 , 0
 3164.90       1       0  4499.9    0.13       0    4975   0.042       0
    5025    0.13       0
#XS Ineff= 2 , 0
       0 4904.71  185.67 5095.32       0  186.58
Bank Sta=4975.00,5025.00
Exp/Cntr=0.5,0.3

Type RM Length L Ch R = 3 ,68144.6,,,
BEGIN DESCRIPTION:
Collins Mill Rd-TOR
Structure ID: Collins Mill Rd-Bridge
Approximate Survey Structure
END DESCRIPTION:
Bridge Culvert--1,0,-1,-1, 0
Deck Dist Width WeirC Skew NumUp NumDn MinLoCord MaxHiCord MaxSubmerge Is_Ogee
10,30,2.6,, 45, 45,,,0.95,0,1,1,,
  3164.9  3196.9  3334.9  3354.9  3374.9  3426.9  3446.9  3544.9  3614.9  3814.9
  3834.9  3854.9  3866.9  4234.9  4376.9  4396.9  4444.9  4454.9  4544.9  4556.9
  4584.9  4604.9  4614.9  4634.9  4724.9  4844.9  4874.9 4914.91    4915 5084.89
    5085  5115.9  5121.9  5175.9  5205.9  5275.9  5351.9  5355.9  5361.9  5381.9
  5395.9  5411.9  5415.9    5455  5474.7
  199.54  199.73  197.47  197.14  196.81  195.96  195.08  193.42  192.09  188.53
  188.17  187.81   187.6  187.19  186.98  187.07  187.04  186.59  186.38  186.09
  185.66  185.69  185.71  185.74  185.88  186.06   186.1  186.16  186.17  186.42
  186.42  186.47  186.48  187.25  187.67  188.66  189.74  189.94  190.25  190.17
  190.46  191.47  191.97  192.01  190.54
  199.54  198.84  195.81  196.04  195.34  194.75  194.52  193.41  190.62  187.32
   188.1  187.41  187.39  186.84  186.97  186.99  187.03  186.58  186.31  186.08
  185.53  185.42  184.78  184.64  181.32  181.51  180.07  180.23  184.77  185.02
  177.09  180.64  180.81  182.34  184.57  186.91  186.36  186.33   186.8  188.37
  189.47  191.46  191.96     192  190.54
  3164.9  3196.9  3334.9  3354.9  3374.9  3426.9  3446.9  3544.9  3614.9  3814.9
  3834.9  3854.9  3866.9  4234.9  4376.9  4396.9  4444.9  4454.9  4544.9  4556.9
  4584.9  4604.9  4614.9  4634.9  4724.9  4844.9  4874.9 4914.91    4915 5084.89
    5085  5115.9  5121.9  5175.9  5205.9  5275.9  5351.9  5355.9  5361.9  5381.9
  5395.9  5411.9  5415.9    5455  5474.7
  199.54  199.73  197.47  197.14  196.81  195.96  195.08  193.42  192.09  188.53
  188.17  187.81   187.6  187.19  186.98  187.07  187.04  186.59  186.38  186.09
  185.66  185.69  185.71  185.74  185.88  186.06   186.1  186.16  186.17  186.42
  186.42  186.47  186.48  187.25  187.67  188.66  189.74  189.94  190.25  190.17
  190.46  191.47  191.97  192.01  190.54
  199.53  198.83   195.8  196.03  195.33  194.74  194.51   193.4  190.61  187.31
  188.09   187.4  187.38  186.83  186.96  186.98  187.02  186.57   186.3  186.07
  185.52  185.41  184.77  184.63  181.31   181.5  180.06  180.22  184.76  185.01
  177.08  180.63   180.8  182.33  184.56   186.9  186.35  186.32  186.79  188.36
  189.46  191.45  191.95  191.99  190.53
Pier Skew, UpSta & Num, DnSta & Num=,4947.3, 2 ,4947.3, 2 , 0 , 0 , 0 ,,
     1.5     1.5
  179.35  185.82
     1.5     1.5
  179.34  185.81
Pier Skew, UpSta & Num, DnSta & Num=,5000.0, 2 ,5000.0, 2 , 0 , 0 , 0 ,,
     1.5     1.5
  171.13   185.9
     1.5     1.5
  171.12  185.89
Pier Skew, UpSta & Num, DnSta & Num=,5052.6, 2 ,5052.6, 2 , 0 , 0 , 0 ,,
     1.5     1.5
  177.47  185.97
     1.5     1.5
  177.46  185.96
Abutment Skew #Up #Dn=, 2 , 2
 4914.80 4921.00
  184.77  180.25
 4914.80 4921.00
  184.76  180.24
Abutment Skew #Up #Dn=, 2 , 2
 5079.00 5085.09
  176.69  185.02
 5079.00 5085.09
  176.68  185.01
BR Coef= 1 , 1 , 0 ,1.25, 0 ,,,0.8,0,2,0,
Wspro=,,,, 1 ,,,, 0 ,,,, 0 ,,,,-1 ,-1 ,-1 , 0 , 0 , 0 , 0 , 0
BC Design=,, 0 ,, 0 ,,,,,,
BR U #Sta/Elev= 62
  3164.9  199.54  3196.9  198.84  3334.9  195.81  3354.9  196.04  3374.9  195.34
  3426.9  194.75  3446.9  194.52  3544.9  193.41  3614.9  190.62  3814.9  187.32
  3834.9   188.1  3854.9  187.41  3866.9  187.39  4234.9  186.84  4366.9  186.96
  4376.9  186.97  4396.9  186.99  4444.9  187.03  4454.9  186.58  4456.9  186.57
  4499.9  186.45  4544.9  186.31  4546.9  186.27  4556.9  186.08  4584.9  185.53
  4604.9  185.42  4614.9  184.78  4634.9  184.64  4724.9  181.32  4844.9  181.51
  4874.9  180.07 4914.91  180.23    4915  180.23    4921  180.25  4954.9  180.38
  4964.9  178.12    4975  178.13    4979  172.13    5021  172.13    5025  178.13
  5025.9  178.27  5045.9  180.05  5065.9  175.82    5079  176.69 5084.89  177.08
    5085  177.09  5085.9  177.15  5115.9  180.64  5121.9  180.81  5175.9  182.34
  5205.9  184.57  5275.9  186.91  5351.9  186.36  5355.9  186.33  5361.9   186.8
  5381.9  188.37  5395.9  189.47  5411.9  191.46  5415.9  191.96  5421.9  191.97
    5455     192  5474.7  190.54
BR U #Mann= 4
 3164.90       1  4499.9    0.13    4975   0.042    5025    0.13
BR U Banks=4975.00,5025.00
BR D #Sta/Elev= 62
  3164.9  199.53  3196.9  198.83  3334.9   195.8  3354.9  196.03  3374.9  195.33
  3426.9  194.74  3446.9  194.51  3544.9   193.4  3614.9  190.61  3814.9  187.31
  3834.9  188.09  3854.9   187.4  3866.9  187.38  4234.9  186.83  4366.9  186.95
  4376.9  186.96  4396.9  186.98  4444.9  187.02  4454.9  186.57  4456.9  186.56
  4499.9  186.44  4544.9   186.3  4546.9  186.26  4556.9  186.07  4584.9  185.52
  4604.9  185.41  4614.9  184.77  4634.9  184.63  4724.9  181.31  4844.9   181.5
  4874.9  180.06 4914.91  180.22    4915  180.22    4921  180.24  4954.9  180.37
  4964.9  178.11    4975  178.12    4979  172.12    5021  172.12    5025  178.12
  5025.9  178.26  5045.9  180.04  5065.9  175.81    5079  176.68 5084.89  177.07
    5085  177.08  5085.9  177.14  5115.9  180.63  5121.9   180.8  5175.9  182.33
  5205.9  184.56  5275.9   186.9  5351.9  186.35  5355.9  186.32  5361.9  186.79
  5381.9  188.36  5395.9  189.46  5411.9  191.45  5415.9  191.95  5421.9  191.96
    5455  191.99  5474.7  190.53
BR D #Mann= 4
 3164.90       1  4499.9    0.13    4975   0.042    5025    0.13
BR D Banks=4975.00,5025.00

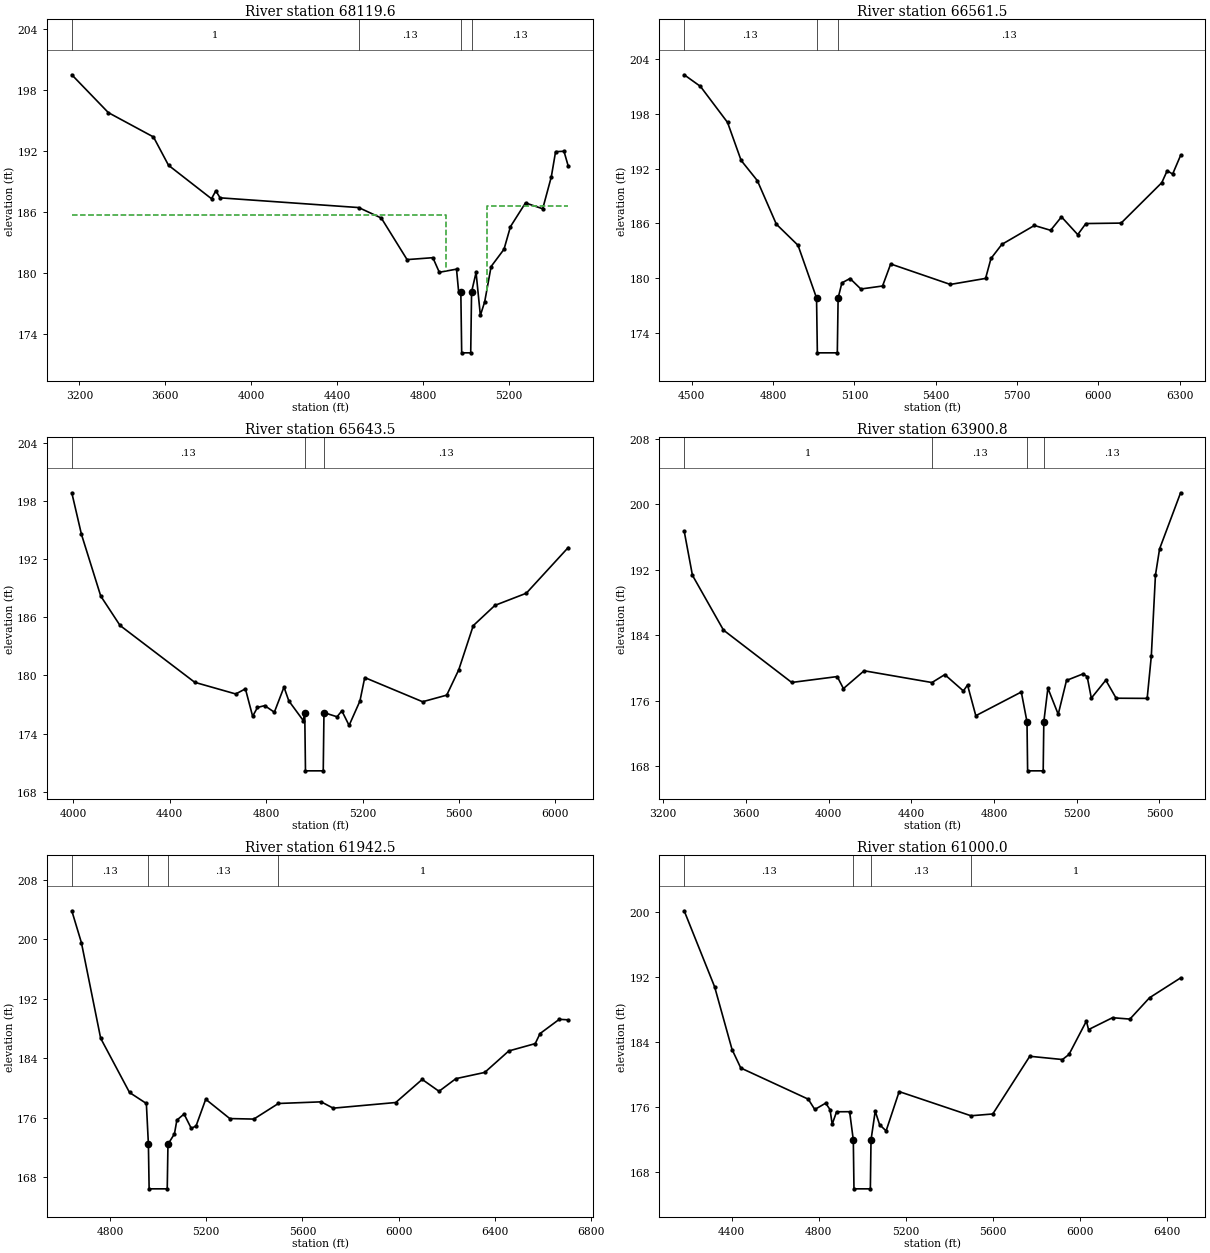
Type RM Length L Ch R = 1 ,68119.6,1558.1,1558.1,1558.1
BEGIN DESCRIPTION:
Downstream Section of Bridge/Culvert/Weir
END DESCRIPTION:
#Sta/Elev= 30
  3164.9  199.53  3334.9   195.8  3544.9   193.4  3614.9  190.61  3814.9  187.31
  3834.9  188.09  3854.9   187.4  4499.9  186.44  4604.9  185.41  4724.9  181.31
  4844.9   181.5  4874.9  180.06  4954.9  180.37  4964.9  178.11    4975  178.12
    4979  172.12    5021  172.12    5025  178.12  5045.9  180.04  5065.9  175.81
  5085.9  177.14  5115.9  180.63  5175.9  182.33  5205.9  184.56  5275.9   186.9
  5355.9  186.32  5395.9  189.46  5415.9  191.95    5455  191.99  5474.7  190.53
#Mann= 4 , 1 , 0
 3164.90       1       0  4499.9    0.13       0    4975   0.042       0
    5025    0.13       0
#XS Ineff= 2 , 0
       0 4904.71  185.67 5095.32       0  186.58
Bank Sta=4975.00,5025.00
Exp/Cntr=0.5,0.3

Type RM Length L Ch R = 1 ,66561.5,918,918,918
BEGIN DESCRIPTION:
Sandy Creek 66.0
END DESCRIPTION:
#Sta/Elev= 30
  4471.9  202.25  4531.9  200.98  4631.9  197.04  4681.9  192.89  4741.9  190.67
  4811.9  185.91  4891.9   183.6  4960.2  177.84  4963.2  171.84  5036.8  171.84
  5039.8  177.84  5053.7  179.49  5083.7  179.97  5123.7  178.82  5203.7  179.15
  5233.7  181.56  5453.7  179.32  5583.7  179.98  5603.7  182.16  5643.7   183.7
  5763.7  185.77  5823.7  185.24  5863.7  186.71  5923.7  184.77  5953.7  185.98
  6083.7  186.03  6233.7  190.45  6253.7  191.76  6273.7  191.39  6303.1  193.43
#Mann= 3 , 1 , 0
 4471.90    0.13       0  4960.2   0.042       0  5039.8    0.13       0
Bank Sta=4960.20,5039.80
Exp/Cntr=0.3,0.1

Type RM Length L Ch R = 1 ,65643.5,1742.7,1742.7,1742.7
BEGIN DESCRIPTION:
Sandy Creek 65.0
END DESCRIPTION:
#Sta/Elev= 30
  3994.1  198.82  4034.1  194.54  4114.1  188.18  4194.1  185.15  4504.1  179.29
  4674.1  178.09  4714.1  178.62  4744.1  175.79  4764.1   176.7  4794.1  176.89
  4834.1  176.21  4874.1   178.8  4894.1  177.38  4954.1  175.35  4960.2  176.17
  4963.2  170.17  5036.9  170.17  5039.9  176.17  5094.1  175.74  5114.1  176.35
  5144.1  174.85    5189  177.36    5209  179.78    5449  177.29    5549  177.97
    5599  180.59    5659  185.13    5749  187.22    5879  188.47  6052.9  193.18
#Mann= 3 , 1 , 0
 3994.10    0.13       0  4960.2   0.042       0  5039.9    0.13       0
Bank Sta=4960.20,5039.90
Exp/Cntr=0.3,0.1

Type RM Length L Ch R = 1 ,63900.8,1958.3,1958.3,1958.3
BEGIN DESCRIPTION:
Sandy Creek 64.0
END DESCRIPTION:
#Sta/Elev= 30
  3301.9  196.75  3341.9  191.33  3491.9  184.62  3821.9  178.21  4041.9  178.93
  4071.9  177.46  4171.9  179.64  4499.9   178.2  4561.9  179.17  4651.9  177.17
  4671.9   177.9  4711.9  174.14  4931.9  177.04  4959.4  173.39  4962.4  167.39
  5037.7  167.39  5040.7  173.39  5060.4  177.51  5110.4  174.31  5150.4  178.46
  5230.4  179.26  5250.4  178.92  5270.4  176.29  5340.4  178.49  5390.4  176.28
  5540.4  176.26  5560.4  181.43  5580.4  191.34  5600.4  194.56    5702  201.43
#Mann= 4 , 1 , 0
 3301.90       1       0  4499.9    0.13       0  4959.4   0.042       0
  5040.7    0.13       0
Bank Sta=4959.40,5040.70
Exp/Cntr=0.3,0.1

Type RM Length L Ch R = 1 ,61942.5,942.5,942.5,942.5
BEGIN DESCRIPTION:
Sandy Creek 62.0
END DESCRIPTION:
#Sta/Elev= 30
  4640.9  203.85  4680.9  199.55  4760.9  186.69  4880.9  179.39  4950.9  177.91
  4959.4  172.42  4962.4  166.42  5037.7  166.42  5040.7  172.42  5067.7  173.82
  5077.7  175.67  5107.7  176.49  5137.7  174.55  5157.7   174.9  5197.7  178.48
  5297.7  175.88  5397.7  175.81  5499.9  177.91  5677.7  178.13  5727.7  177.28
  5987.7  178.04  6097.7  181.15  6167.7  179.55  6237.7  181.25  6357.7  182.09
  6457.7  184.98  6567.7  185.97  6587.7  187.32  6667.7  189.24  6704.9  189.17
#Mann= 4 , 1 , 0
 4640.90    0.13       0  4959.4   0.042       0  5040.7    0.13       0
  5499.9       1       0
Bank Sta=4959.40,5040.70
Exp/Cntr=0.3,0.1

Type RM Length L Ch R = 1 ,61000.0,1752.3,1752.3,1752.3
BEGIN DESCRIPTION:
Sandy Creek 61.0
END DESCRIPTION:
#Sta/Elev= 30
  4182.4  200.13  4322.4  190.78  4402.4  183.08  4442.4  180.81  4752.4  176.98
  4782.4  175.71  4832.4  176.49  4852.4   175.7  4862.4   173.9  4882.4  175.43
  4942.4  175.44  4959.4  171.96  4962.4  165.96  5037.7  165.96  5040.7  171.96
    5060  175.51    5080  173.85    5110  173.08    5170  177.91  5499.9  174.94
    5600  175.16    5770  182.25    5920  181.85    5950  182.47    6030  186.57
    6040  185.53    6150  186.99    6230  186.82    6320  189.44  6462.8  191.88
#Mann= 4 , 1 , 0
 4182.40    0.13       0  4959.4   0.042       0  5040.7    0.13       0
  5499.9       1       0
Bank Sta=4959.40,5040.70
Exp/Cntr=0.3,0.1

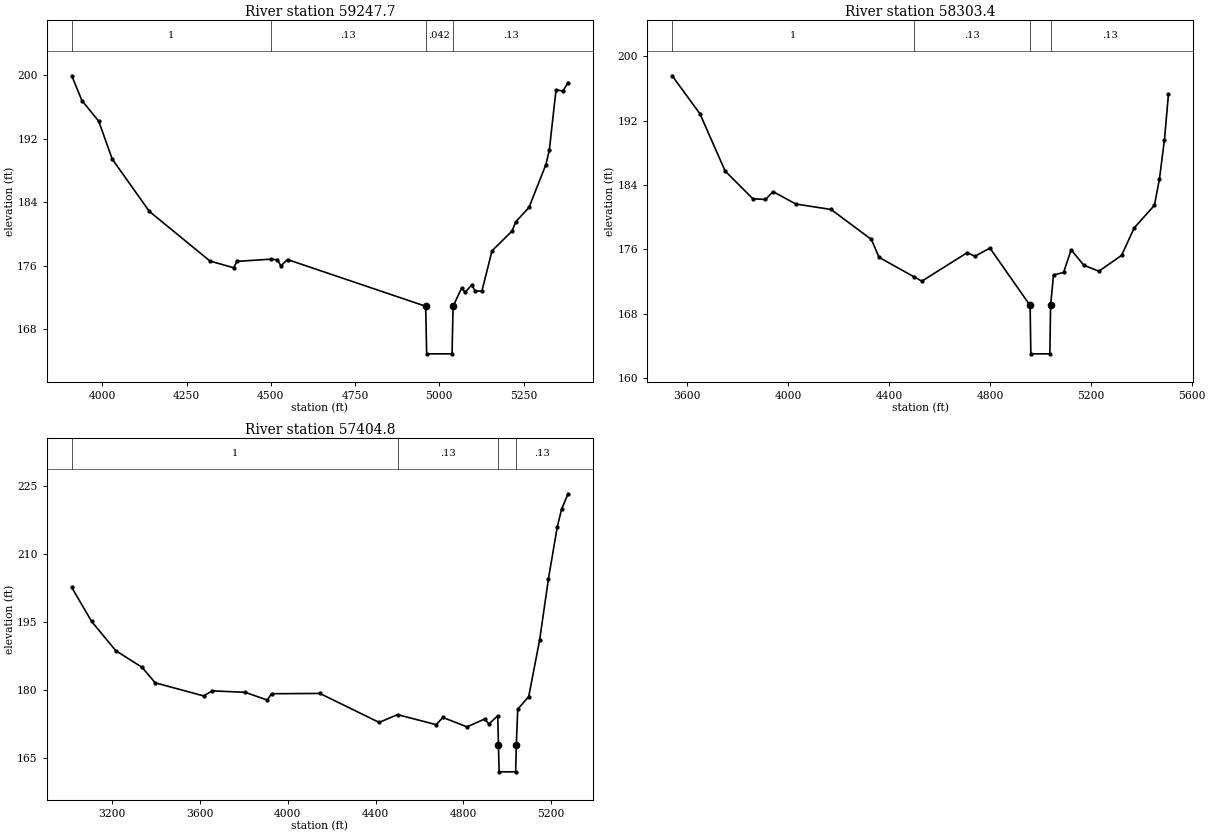
Type RM Length L Ch R = 1 ,59247.7,944.3,944.3,944.3
BEGIN DESCRIPTION:
Sandy Creek 59.0
END DESCRIPTION:
#Sta/Elev= 30
  3909.7  199.95  3939.7  196.83  3989.7  194.21  4029.7  189.44  4139.7  182.85
  4319.7  176.58  4389.7  175.74  4399.7  176.54  4499.9  176.82  4519.7  176.74
  4529.7  175.98  4549.7  176.77  4959.4  170.88  4962.4  164.88  5037.7  164.88
  5040.7  170.88  5066.2  173.18  5076.2  172.63  5096.2  173.57  5106.2  172.79
  5126.2   172.8  5156.2  177.87  5216.2  180.39  5226.2   181.5  5266.2  183.37
  5316.2  188.76  5326.2  190.57  5346.2  198.21  5366.2     198  5381.8  199.09
#Mann= 4 , 1 , 0
 3909.70       1       0  4499.9    0.13       0  4959.4   0.042       0
  5040.7    0.13       0
Bank Sta=4959.40,5040.70
Exp/Cntr=0.3,0.1

Type RM Length L Ch R = 1 ,58303.4,898.6,898.6,898.6
BEGIN DESCRIPTION:
Sandy Creek 58.0
END DESCRIPTION:
#Sta/Elev= 30
  3540.3  197.55  3650.3  192.84  3750.3  185.73  3860.3  182.29  3910.3   182.2
  3940.3  183.18  4030.3  181.64  4170.3  180.96  4330.3  177.24  4360.3  175.03
  4499.9  172.59  4530.3  172.07  4710.3  175.61  4740.3  175.15  4800.3  176.17
  4959.4  169.05  4962.4  163.05  5037.7  163.05  5040.7  169.05  5052.2  172.83
  5092.2  173.15  5122.2  175.96  5172.2  174.05  5232.2   173.3  5322.2  175.27
  5372.2  178.68  5452.2  181.47  5472.2  184.73  5492.2  189.63  5507.9  195.24
#Mann= 4 , 1 , 0
 3540.30       1       0  4499.9    0.13       0  4959.4   0.042       0
  5040.7    0.13       0
Bank Sta=4959.40,5040.70
Exp/Cntr=0.3,0.1

Type RM Length L Ch R = 1 ,57404.8,1941.1,1941.1,1941.1
BEGIN DESCRIPTION:
Sandy Creek 57.0
END DESCRIPTION:
#Sta/Elev= 30
    3016   202.6    3106  195.13    3216  188.68    3336  184.99    3396  181.58
    3616  178.69    3656   179.8    3806  179.48    3906  177.78    3926  179.17
    4146  179.23    4416  172.84  4499.9  174.56    4676  172.34    4706  173.94
    4816  171.86    4896  173.58    4916  172.48    4956  174.31  4959.4  167.94
  4962.4  161.94  5037.7  161.94  5040.7  167.94  5047.2  175.76  5097.2  178.54
  5147.2  191.09  5187.2  204.55  5227.2  215.95  5247.2  219.91  5276.4  223.27
#Mann= 4 , 1 , 0
 3016.00       1       0  4499.9    0.13       0  4959.4   0.042       0
  5040.7    0.13       0
Bank Sta=4959.40,5040.70
Exp/Cntr=0.3,0.1