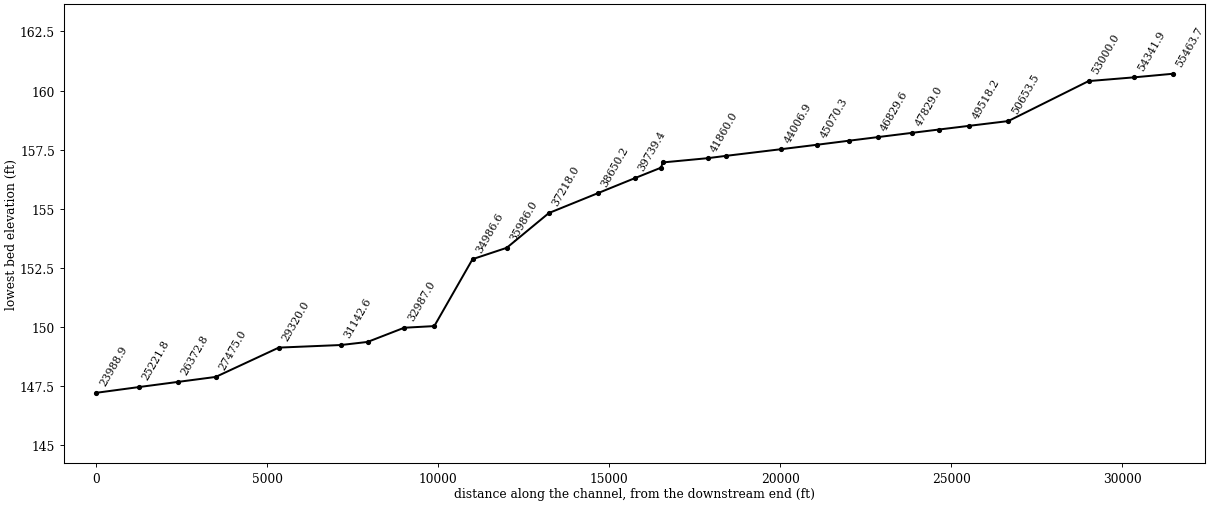
HEC-RAS study 020822_SANDY_CREEK.prj: Sandy Creek

--- 020822_SANDY_CREEK.g01 (geometry) --- (continued)

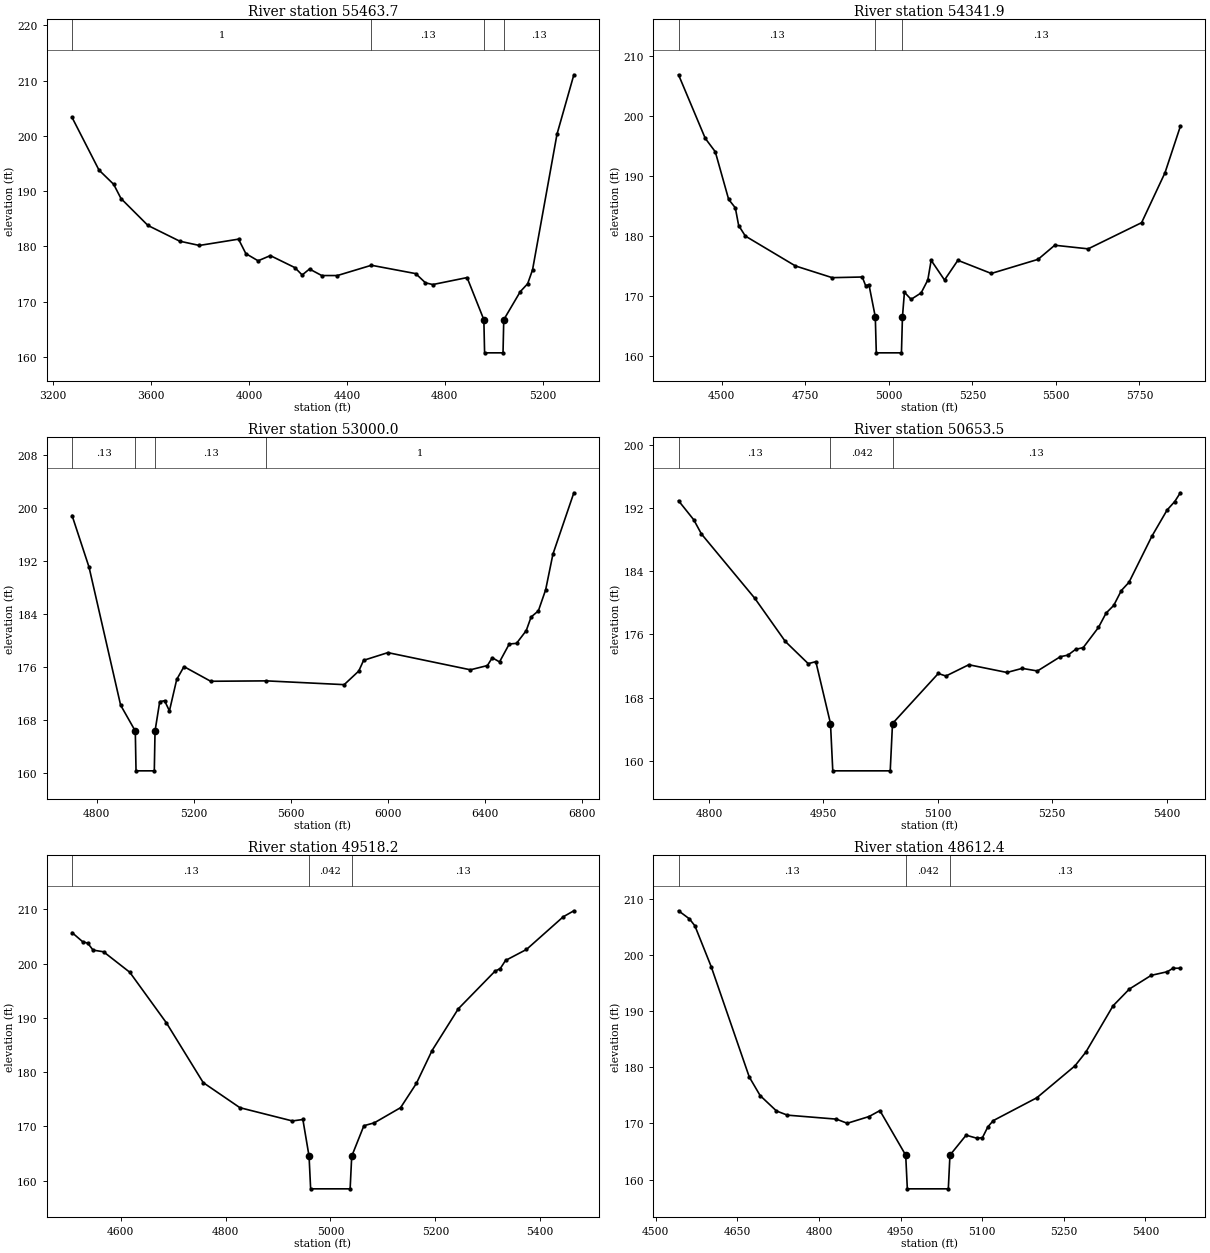
Type RM Length L Ch R = 1 ,55463.7,1121.8,1121.8,1121.8
BEGIN DESCRIPTION:
Sandy Creek 56.0
END DESCRIPTION:
#Sta/Elev= 30
    3277  203.34    3387  193.81    3447  191.23    3477  188.65    3587  183.78
    3717  180.93    3797  180.16    3957   181.3    3987  178.68    4037  177.38
    4087  178.32    4187  176.15    4217  174.81    4247  175.89    4297  174.71
  4360.8  174.71  4499.9  176.57  4680.8  175.06  4720.8  173.39  4750.8  173.08
  4890.8  174.34  4959.3  166.71  4962.3  160.71  5037.6  160.71  5040.6  166.71
  5108.2   171.8  5138.2  173.22  5158.2  175.74  5258.2  200.33    5327  211.07
#Mann= 4 , 1 , 0
 3277.00       1       0  4499.9    0.13       0  4959.3   0.042       0
  5040.6    0.13       0
Bank Sta=4959.30,5040.60
Exp/Cntr=0.3,0.1

Type RM Length L Ch R = 1 ,54341.9,1341.9,1341.9,1341.9
BEGIN DESCRIPTION:
Sandy Creek 54.0
END DESCRIPTION:
#Sta/Elev= 30
  4370.4  206.87  4450.4  196.28  4480.4  194.05  4520.4  186.12  4540.4  184.71
  4550.4  181.76  4570.4  180.01  4720.4  175.03  4830.4  173.08  4920.4  173.19
  4930.4  171.76  4940.4  171.92  4959.4  166.56  4962.4  160.56  5037.7  160.56
  5040.7  166.56  5046.6  170.65  5066.6  169.47  5096.6  170.54  5116.6  172.69
  5126.6  175.97  5166.6  172.69  5206.6  175.97  5306.6  173.78  5446.6  176.13
  5496.6  178.48  5596.6  177.88  5756.6  182.24  5826.6  190.55  5872.5  198.27
#Mann= 3 , 1 , 0
 4370.40    0.13       0  4959.4   0.042       0  5040.7    0.13       0
Bank Sta=4959.40,5040.70
Exp/Cntr=0.3,0.1

Type RM Length L Ch R = 1 ,53000.0,2346.5,2346.5,2346.5
BEGIN DESCRIPTION:
Sandy Creek 53.0
END DESCRIPTION:
#Sta/Elev= 30
  4698.9  198.91  4768.9  191.11  4898.9  170.31  4959.4   166.4  4962.4   160.4
  5037.7   160.4  5040.7   166.4    5060  170.83    5080  170.98    5100  169.44
    5130  174.18    5160  176.12    5270  173.91  5499.9  173.97    5820   173.4
    5880  175.45    5900  177.07    6000  178.23    6340  175.64    6410  176.28
    6430  177.46    6460  176.83    6500  179.53    6530  179.63    6570  181.55
    6590   183.6    6620  184.53    6650  187.71    6680  193.09  6766.2  202.34
#Mann= 4 , 1 , 0
 4698.90    0.13       0  4959.4   0.042       0  5040.7    0.13       0
  5499.9       1       0
Bank Sta=4959.40,5040.70
Exp/Cntr=0.3,0.1

Type RM Length L Ch R = 1 ,50653.5,1135.3,1135.3,1135.3
BEGIN DESCRIPTION:
Sandy Creek 51.0
END DESCRIPTION:
#Sta/Elev= 30
  4760.2  192.95  4780.2  190.53  4790.2  188.74  4860.2  180.58  4900.2  175.11
  4930.2   172.3  4940.2  172.55  4959.4  164.71  4962.4  158.71  5037.7  158.71
  5040.7  164.71  5100.7  171.05  5110.7  170.73  5140.7  172.16  5190.7  171.18
  5210.7   171.7  5230.7  171.37  5260.7  173.18  5270.7  173.38  5280.7  174.11
  5290.7  174.33  5310.7  176.89  5320.7  178.71  5330.7  179.68  5340.7  181.57
  5350.7  182.61  5380.7  188.45  5400.7  191.78  5410.7  192.85    5418  193.96
#Mann= 3 , 1 , 0
 4760.20    0.13       0  4959.4   0.042       0  5040.7    0.13       0
Bank Sta=4959.40,5040.70
Exp/Cntr=0.3,0.1

Type RM Length L Ch R = 1 ,49518.2,905.8,905.8,905.8
BEGIN DESCRIPTION:
Sandy Creek 50.0
END DESCRIPTION:
#Sta/Elev= 27
  4507.5  205.69  4527.5  204.03  4537.5  203.73  4547.5  202.47  4567.5  202.16
  4617.5  198.39  4687.5  189.05  4757.5  178.07  4827.5  173.45  4927.5  171.01
  4947.5  171.28  4959.3  164.51  4962.3  158.51  5037.6  158.51  5040.6  164.51
  5063.8  170.13  5083.8  170.67  5133.8  173.46  5163.8  177.91  5193.8  183.98
  5243.8  191.66  5313.8  198.59  5323.8  199.07  5333.8  200.56  5373.8  202.59
  5443.8   208.6  5464.1  209.71
#Mann= 3 , 1 , 0
 4507.50    0.13       0  4959.3   0.042       0  5040.6    0.13       0
Bank Sta=4959.30,5040.60
Exp/Cntr=0.3,0.1

Type RM Length L Ch R = 1 ,48612.4,783.4,783.4,783.4
BEGIN DESCRIPTION:
Sandy Creek 49.0
END DESCRIPTION:
#Sta/Elev= 30
    4542  207.89    4562  206.45    4572  205.22    4602  197.94    4672  178.27
    4692  174.96    4722  172.22    4742  171.48    4832  170.77    4852  170.03
    4892  171.23    4912  172.29  4959.4  164.35  4962.4  158.35  5037.7  158.35
  5040.7  164.35  5070.4  167.91  5090.4  167.36  5100.4  167.47  5110.4   169.4
  5120.4  170.51  5200.4  174.58  5270.4  180.26  5290.4  182.71  5340.4  190.96
  5370.4  193.95  5410.4  196.38  5440.4  197.04  5450.4  197.65    5464  197.66
#Mann= 3 , 1 , 0
 4542.00    0.13       0  4959.4   0.042       0  5040.7    0.13       0
Bank Sta=4959.40,5040.70
Exp/Cntr=0.3,0.1

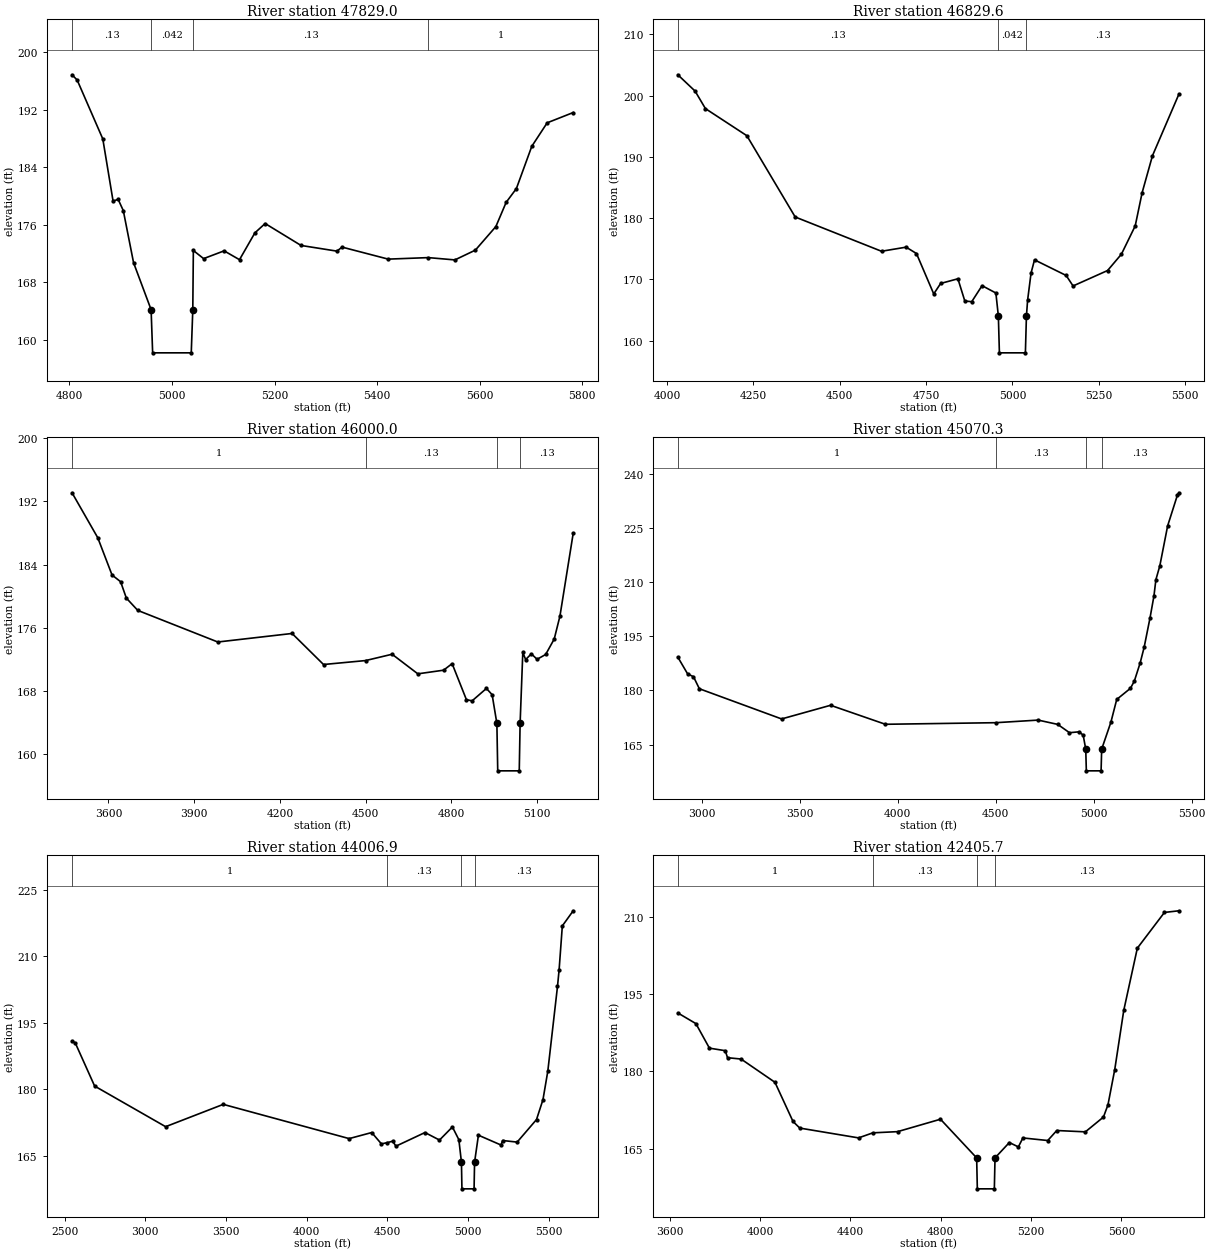
Type RM Length L Ch R = 1 ,47829.0,999.4,999.4,999.4
BEGIN DESCRIPTION:
Sandy Creek 48.0
END DESCRIPTION:
#Sta/Elev= 30
  4805.1  196.87  4815.1  196.14  4865.1  187.95  4885.1  179.32  4895.1  179.54
  4905.1  177.98  4925.1  170.74  4959.3  164.21  4962.3  158.21  5037.6  158.21
  5040.6  164.21  5041.7  172.44  5061.7  171.31  5101.7  172.39  5131.7  171.16
  5161.7  174.89  5181.7  176.19  5251.7  173.14  5321.7  172.35  5331.7  172.91
  5421.7  171.24  5499.9  171.45  5551.7  171.13  5591.7  172.49  5631.7  175.77
  5651.7  179.13  5671.7  181.05  5701.7  186.92  5731.7  190.19  5782.5  191.62
#Mann= 4 , 1 , 0
 4805.10    0.13       0  4959.3   0.042       0  5040.6    0.13       0
  5499.9       1       0
Bank Sta=4959.30,5040.60
Exp/Cntr=0.3,0.1

Type RM Length L Ch R = 1 ,46829.6,829.6,829.6,829.6
BEGIN DESCRIPTION:
Sandy Creek 46.5
END DESCRIPTION:
#Sta/Elev= 30
  4030.8  203.39  4080.8  200.73  4110.8  197.87  4230.8  193.45  4370.8  180.19
  4620.8   174.6  4692.1  175.27  4722.1  174.23  4772.1  167.64  4792.1  169.35
  4842.1  170.11  4862.1  166.49  4882.1  166.37  4912.1  168.99  4952.1  167.79
  4959.3  164.03  4962.3  158.03  5037.6  158.03  5040.6  164.03    5044  166.61
    5054  171.05    5064   173.2  5155.7  170.65  5175.7  168.94  5275.7  171.46
  5315.7  174.12  5355.7  178.74  5375.7  184.15  5405.7  190.19  5482.5  200.26
#Mann= 3 , 1 , 0
 4030.80    0.13       0  4959.3   0.042       0  5040.6    0.13       0
Bank Sta=4959.30,5040.60
Exp/Cntr=0.3,0.1

Type RM Length L Ch R = 1 ,46000.0,929.7,929.7,929.7
BEGIN DESCRIPTION:
Sandy Creek 46.0
END DESCRIPTION:
#Sta/Elev= 30
  3472.7  193.08  3562.7  187.39  3612.7  182.67  3642.7  181.82  3662.7  179.75
  3702.7  178.19  3982.7  174.19  4242.7  175.27  4352.7  171.34  4499.9  171.84
  4592.7  172.64  4682.7  170.16  4772.7  170.62  4802.7  171.45  4852.7  166.89
  4872.7  166.74  4922.7  168.31  4942.7  167.52  4959.3  163.88  4962.3  157.88
  5037.6  157.88  5040.6  163.88    5050  172.87    5060  171.97    5080  172.69
    5100     172    5130  172.61    5160  174.57    5180  177.47  5226.4  187.95
#Mann= 4 , 1 , 0
 3472.70       1       0  4499.9    0.13       0  4959.3   0.042       0
  5040.6    0.13       0
Bank Sta=4959.30,5040.60
Exp/Cntr=0.3,0.1

Type RM Length L Ch R = 1 ,45070.3,1063.4,1063.4,1063.4
BEGIN DESCRIPTION:
Sandy Creek 44.0
END DESCRIPTION:
#Sta/Elev= 30
  2876.4  189.19  2926.4  184.56  2956.4  183.77  2986.4  180.44  3406.4  172.08
  3656.4  175.86  3936.4   170.6  4499.9  171.04  4716.4  171.76  4816.4  170.57
  4876.4  168.27  4926.4  168.52  4946.4  167.56  4959.4  163.71  4962.4  157.71
  5037.7  157.71  5040.7  163.71  5087.6  171.14  5117.6  177.48  5187.6  180.56
  5207.6  182.58  5237.6  187.66  5257.6  191.92  5287.6  200.07  5307.6  206.12
  5317.6  210.65  5337.6  214.47  5377.6  225.55  5427.6  234.08  5435.5   234.7
#Mann= 4 , 1 , 0
 2876.40       1       0  4499.9    0.13       0  4959.4   0.042       0
  5040.7    0.13       0
Bank Sta=4959.40,5040.70
Exp/Cntr=0.3,0.1

Type RM Length L Ch R = 1 ,44006.9,1601.2,1601.2,1601.2
BEGIN DESCRIPTION:
Sandy Creek 43.0
END DESCRIPTION:
#Sta/Elev= 30
  2546.1  190.86  2566.1  190.46  2686.1  180.72  3126.1  171.55  3483.3  176.59
  4263.3  168.86  4403.3  170.23  4463.3  167.67  4499.9  167.95  4533.3  168.28
  4553.3  167.15  4733.3  170.23  4823.3  168.53  4903.3  171.49  4943.3  168.61
  4959.3  163.52  4962.3  157.52  5037.6  157.52  5040.6  163.52  5064.5  169.63
  5204.5  167.41  5214.5  168.43  5304.5  168.07  5424.5  173.16  5464.5  177.65
  5494.5  184.08  5554.5   203.2  5564.5  206.94  5584.5  216.88  5651.9  220.29
#Mann= 4 , 1 , 0
 2546.10       1       0  4499.9    0.13       0  4959.3   0.042       0
  5040.6    0.13       0
Bank Sta=4959.30,5040.60
Exp/Cntr=0.3,0.1

Type RM Length L Ch R = 1 ,42405.7,545.7,545.7,545.7
BEGIN DESCRIPTION:
Sandy Creek 42.5
END DESCRIPTION:
#Sta/Elev= 30
  3636.4  191.35  3716.4  189.28  3776.4  184.52  3846.4  184.03  3856.4  182.67
  3916.4  182.41  4066.4   177.9  4146.4   170.3  4176.4  169.02  4436.4  167.12
  4499.9   168.1  4609.2  168.33  4799.2  170.74  4959.3  163.24  4962.3  157.24
  5037.6  157.24  5040.6  163.24    5104  166.22    5144  165.37    5164  167.11
    5274  166.61    5314  168.55  5440.6  168.29  5520.6  171.16  5540.6  173.53
  5570.6  180.37  5610.6  191.87  5670.6  203.91  5790.6  210.84    5855  211.16
#Mann= 4 , 1 , 0
 3636.40       1       0  4499.9    0.13       0  4959.3   0.042       0
  5040.6    0.13       0
Bank Sta=4959.30,5040.60
Exp/Cntr=0.3,0.1

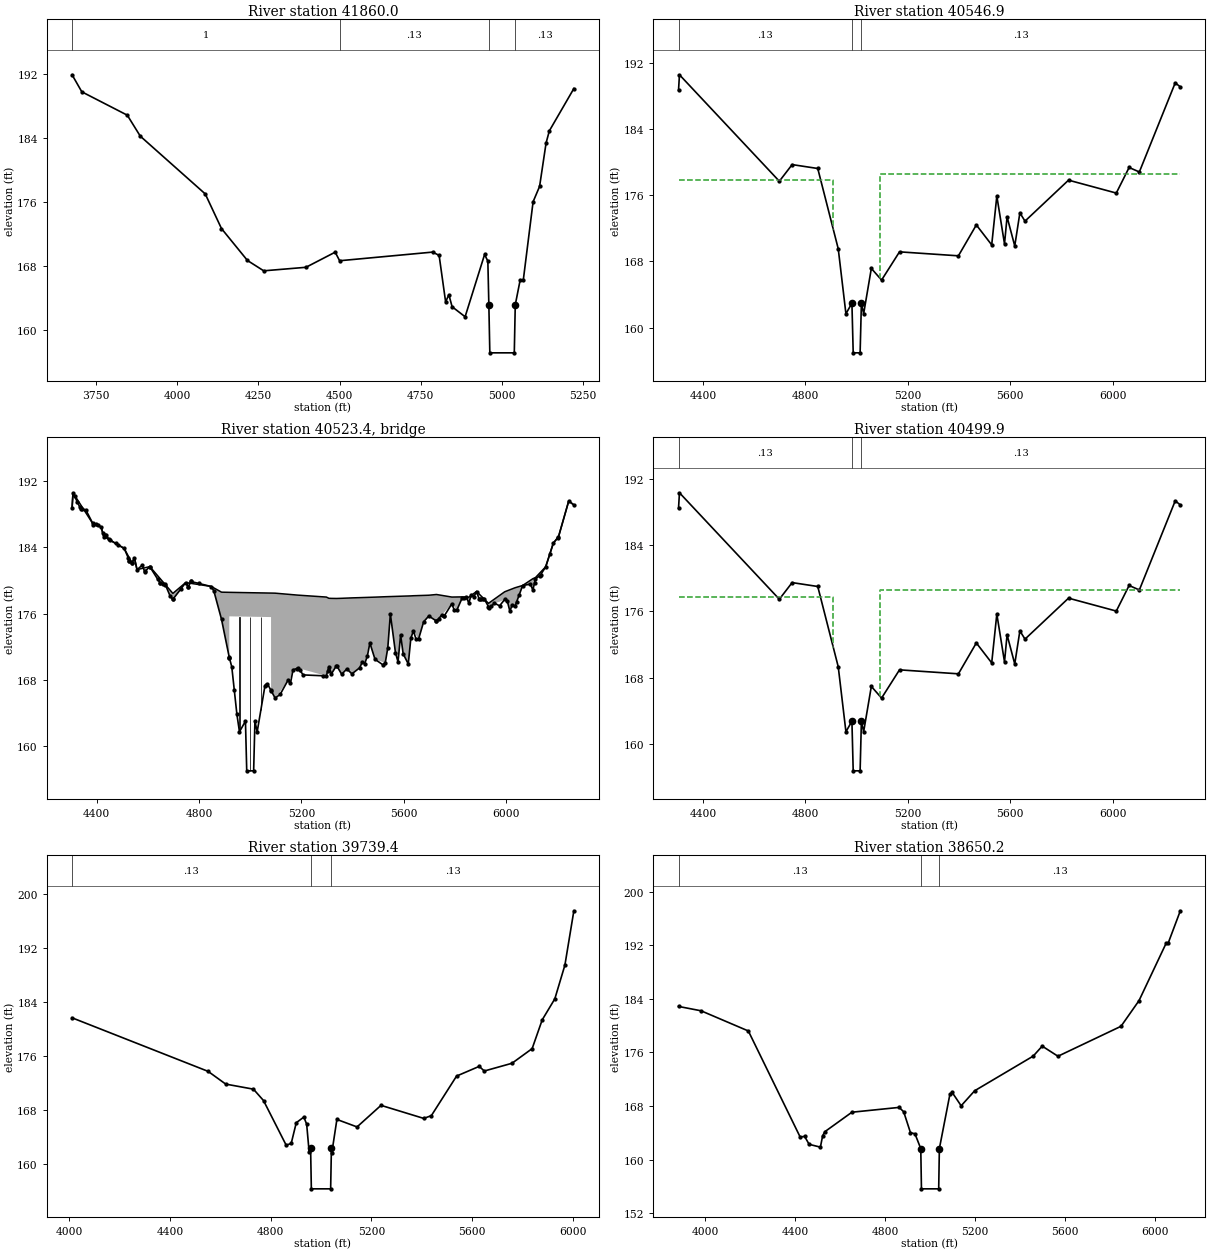
Type RM Length L Ch R = 1 ,41860.0,1313.1,1313.1,1313.1
BEGIN DESCRIPTION:
Sandy Creek 42.0
END DESCRIPTION:
#Sta/Elev= 30
  3676.2  191.89  3706.2  189.76  3846.2  186.84  3886.2  184.22  4086.2     177
  4136.2  172.67  4216.2  168.68  4266.2  167.39  4396.2  167.83  4486.2  169.72
  4499.9  168.65  4786.2  169.73  4806.2  169.32  4826.2  163.51  4836.2   164.4
  4846.2   162.9  4886.2  161.65  4946.2  169.43  4956.2   168.6  4959.3  163.14
  4962.3  157.14  5037.6  157.14  5040.6  163.14  5055.5   166.2  5065.5  166.29
  5095.5  176.02  5115.5  177.94  5135.5  183.37  5145.5  184.88    5221  190.17
#Mann= 4 , 1 , 0
 3676.20       1       0  4499.9    0.13       0  4959.3   0.042       0
  5040.6    0.13       0
Bank Sta=4959.30,5040.60
Exp/Cntr=0.3,0.1

Type RM Length L Ch R = 1 ,40546.9,47,47,47
BEGIN DESCRIPTION:
Upstream Section of Bridge/Culvert/Weir
END DESCRIPTION:
#Sta/Elev= 30
  4304.5  188.69  4308.1  190.55  4698.1  177.69  4748.1   179.7  4848.1  179.23
  4928.1  169.53  4958.1  161.68  4981.5  162.96  4986.5  156.96  5013.5  156.96
  5018.5  162.96  5027.3  161.68  5057.3  167.16  5097.3  165.75  5167.3  169.16
  5397.3  168.68  5467.3  172.41  5527.3     170  5547.3   175.9  5577.3  170.12
  5587.3  173.39  5617.3  169.87  5637.3  173.87  5657.3  172.87  5827.3  177.82
  6013.8  176.26  6063.8  179.35  6103.8  178.81  6243.8  189.57  6263.8  189.09
#Mann= 3 , 1 , 0
 4304.50    0.13       0  4981.5   0.042       0  5018.5    0.13       0
#XS Ineff= 2 , 0
       0    4909  177.78    5092       0  178.53
Bank Sta=4981.50,5018.50
Exp/Cntr=0.5,0.3

Type RM Length L Ch R = 3 ,40523.4,,,
BEGIN DESCRIPTION:
Pullen Pasture Rd-TOR
Structure ID: Pullen Pasture Rd-Bridge
Approximate Survey Structure
END DESCRIPTION:
Bridge Culvert--1,0,-1,-1, 0
Deck Dist Width WeirC Skew NumUp NumDn MinLoCord MaxHiCord MaxSubmerge Is_Ogee
10,27,2.6,, 60, 60,,,0.95,0,1,1,,
  4304.5  4308.1  4388.1  4418.1  4428.1  4508.1  4538.1  4548.1  4558.1  4608.1
  4698.1  4748.1  4848.1  4888.1 4918.41  4918.5 5081.39  5081.5  5097.3  5187.3
  5297.3  5307.3  5317.3  5337.3  5357.3  5397.3  5447.3  5467.3  5487.3  5527.3
  5537.3  5547.3  5567.3  5577.3  5587.3  5597.3  5617.3  5627.3  5637.3  5657.3
  5677.3  5697.3  5727.3  5787.3  5807.3  5827.3  5853.8  5883.8  5930.4  5993.8
  6013.8  6033.8  6063.8  6103.8  6113.8  6153.8  6183.8  6203.8  6243.8  6263.8
  188.73   190.6  186.74  186.47  185.32  183.88  182.14  182.72  181.31  181.68
  178.44  179.75  179.28  178.59  178.57  178.57  178.48  178.48  178.47  178.23
     178  177.85  177.84  177.83  177.85   177.9  177.95  177.97  177.99  178.04
  178.05  178.06  178.08  178.09   178.1  178.11  178.13  178.14  178.16  178.18
   178.2  178.22  178.31     178  178.01  178.02  177.98  178.68  177.24  178.64
  178.88  179.12   179.4  180.22  180.35  181.66  184.53  185.28  189.61  189.13
  188.73  190.59  186.73  186.46  185.31  183.87  182.13  182.71   181.3  181.67
  177.73  179.74  179.27   175.3  170.69  175.67  175.58   166.7  165.79  169.41
  168.47   169.6  168.73  169.72  168.67  168.72  169.97  172.45  170.48  170.04
  171.85  175.94  171.26  170.16  173.43  171.14  169.91  173.03  173.91  172.91
  175.01  175.71   175.1  177.18  176.45  177.86  177.29  178.67  176.85  177.71
   176.3  176.86  179.39  178.85  180.18  181.65  184.52  185.28  189.61  189.13
  4304.5  4308.1  4388.1  4418.1  4428.1  4508.1  4538.1  4548.1  4558.1  4608.1
  4698.1  4748.1  4848.1  4888.1 4918.41  4918.5 5081.39  5081.5  5097.3  5187.3
  5297.3  5307.3  5317.3  5337.3  5357.3  5397.3  5447.3  5467.3  5487.3  5527.3
  5537.3  5547.3  5567.3  5577.3  5587.3  5597.3  5617.3  5627.3  5637.3  5657.3
  5677.3  5697.3  5727.3  5787.3  5807.3  5827.3  5853.8  5883.8  5930.4  5993.8
  6013.8  6033.8  6063.8  6103.8  6113.8  6153.8  6183.8  6203.8  6243.8  6263.8
  188.73   190.6  186.74  186.47  185.32  183.88  182.14  182.72  181.31  181.68
  178.44  179.75  179.28  178.59  178.57  178.57  178.48  178.48  178.47  178.23
     178  177.85  177.84  177.83  177.85   177.9  177.95  177.97  177.99  178.04
  178.05  178.06  178.08  178.09   178.1  178.11  178.13  178.14  178.16  178.18
   178.2  178.22  178.31     178  178.01  178.02  177.98  178.68  177.24  178.64
  178.88  179.12   179.4  180.22  180.35  181.66  184.53  185.28  189.61  189.13
  188.48  190.34  186.48  186.21  185.06  183.62  181.88  182.46  181.05  181.42
  177.48  179.49  179.02  175.05  170.44  175.42  175.33  166.45  165.54  169.16
  168.22  169.35  168.48  169.47  168.42  168.47  169.72   172.2  170.23  169.79
   171.6  175.69  171.01  169.91  173.18  170.89  169.66  172.78  173.66  172.66
  174.76  175.46  174.85  176.93   176.2  177.61  177.04  178.42   176.6  177.46
  176.05  176.61  179.14   178.6  179.93   181.4  184.27  185.03  189.36  188.88
Pier Skew, UpSta & Num, DnSta & Num=,4958.7, 2 ,4958.7, 2 , 0 , 0 , 0 ,,
       2       2
   160.8  176.65
       2       2
  160.55   176.4
Pier Skew, UpSta & Num, DnSta & Num=,5000.0, 2 ,5000.0, 2 , 0 , 0 , 0 ,,
       2       2
     156  176.63
       2       2
  155.75  176.38
Pier Skew, UpSta & Num, DnSta & Num=,5041.4, 2 ,5041.4, 2 , 0 , 0 , 0 ,,
       2       2
  163.11   176.6
       2       2
  162.86  176.35
Abutment Skew #Up #Dn=, 2 , 2
 4918.30 4938.00
  175.67  166.73
 4918.30 4938.00
  175.42  166.48
Abutment Skew #Up #Dn=, 2 , 2
 5062.00 5081.59
  167.35  175.58
 5062.00 5081.59
  167.10  175.33
BR Coef= 1 , 1 , 0 ,1.25, 0 ,,,0.8,0,2,0,
Wspro=,,,, 1 ,,,, 0 ,,,, 0 ,,,,-1 ,-1 ,-1 , 0 , 0 , 0 , 0 , 0
BC Design=,, 0 ,, 0 ,,,,,,
BR U #Sta/Elev= 157
  4304.5  188.73  4308.1  190.59  4314.5  190.17  4324.5  189.52  4334.5  188.87
  4338.1  188.64  4344.5  188.61  4358.1  188.54  4384.5  186.95  4388.1  186.73
  4398.1  186.87  4404.5  186.74  4418.1  186.46  4424.5  185.72  4428.1  185.31
  4434.5  185.45  4438.1  185.53  4448.1  184.97  4454.5  184.85  4474.5  184.49
  4484.5   184.3  4508.1  183.87  4524.5  182.67  4528.1  182.41  4528.7  182.39
  4538.1  182.13  4538.7  182.16  4548.1  182.71  4558.1   181.3  4578.1  181.84
  4588.1  181.08  4588.7   181.1  4608.1  181.67  4608.7  181.64  4638.7  180.16
  4648.1   179.7  4648.7  179.69  4658.7  179.61  4668.1  179.53  4668.7  179.49
  4688.1  178.07  4698.1  177.73  4698.7  177.75  4728.7  178.96  4748.1  179.74
  4758.1  179.18  4758.7  179.22  4768.1  179.88  4768.7  179.88  4798.7  179.65
  4848.1  179.27  4858.1  178.74  4888.1   175.3  4918.1  170.73 4918.41  170.69
  4918.5  170.68  4928.1  169.57    4938  166.73  4948.1  163.83  4958.1  161.72
  4981.5     163  4986.5     157  5013.5     157  5018.5     163  5027.3  161.72
  5057.3   167.2    5062  167.35  5067.3  167.52 5081.39  166.71  5081.5   166.7
  5097.3  165.79  5117.3  166.25  5147.3  167.93  5157.3  167.59  5167.3   169.2
  5182.9  169.36  5187.3  169.41  5192.9  169.18  5207.3  168.59  5282.9  168.49
  5297.3  168.47  5302.9   169.1  5307.3   169.6  5317.3  168.73  5335.4  169.63
  5337.3  169.72  5357.3  168.67  5377.3  169.31  5397.3  168.72  5427.3  169.45
  5437.3   170.1  5447.3  169.97  5457.3  170.84  5467.3  172.45  5487.3  170.48
  5517.3  169.83  5527.3  170.04  5537.3  171.85  5547.3  175.94  5567.3  171.26
  5577.3  170.16  5587.3  173.43  5597.3  171.14  5617.3  169.91  5627.3  173.03
  5637.3  173.91  5647.3  172.94  5657.3  172.91  5677.3  175.01  5697.3  175.71
  5725.4  175.14  5727.3   175.1  5735.4  175.38  5747.3  175.79  5755.4  175.72
  5757.3   175.7  5787.3  177.18  5797.3   176.4  5807.3  176.45  5827.3  177.86
  5835.4   177.9  5843.8  177.95  5853.8  177.29  5863.8   178.3  5873.8  178.06
  5883.8  178.67  5893.8  177.79  5895.4  177.79  5900.4  177.78  5910.4  177.77
  5913.8  177.77  5930.4  176.85  5933.8  176.66  5940.4  176.86  5953.8  177.26
  5973.8  176.94  5993.8  177.71  6003.8  177.54  6013.8   176.3  6023.8  177.08
  6033.8  176.86  6040.4  177.42  6050.4  178.26  6063.8  179.39  6093.8  179.56
  6103.8  178.85  6110.4  179.73  6113.8  180.18  6130.4   180.6  6133.8  180.69
  6153.8  181.65  6170.4  183.24  6183.8  184.52  6200.4  185.15  6203.8  185.28
  6243.8  189.61  6263.8  189.13
BR U #Mann= 3
 4304.50    0.13  4981.5   0.042  5018.5    0.13
BR U Banks=4981.50,5018.50
BR D #Sta/Elev= 157
  4304.5  188.48  4308.1  190.34  4314.5  189.92  4324.5  189.27  4334.5  188.62
  4338.1  188.39  4344.5  188.36  4358.1  188.29  4384.5   186.7  4388.1  186.48
  4398.1  186.62  4404.5  186.49  4418.1  186.21  4424.5  185.47  4428.1  185.06
  4434.5   185.2  4438.1  185.28  4448.1  184.72  4454.5   184.6  4474.5  184.24
  4484.5  184.05  4508.1  183.62  4524.5  182.42  4528.1  182.16  4528.7  182.14
  4538.1  181.88  4538.7  181.91  4548.1  182.46  4558.1  181.05  4578.1  181.59
  4588.1  180.83  4588.7  180.85  4608.1  181.42  4608.7  181.39  4638.7  179.91
  4648.1  179.45  4648.7  179.44  4658.7  179.36  4668.1  179.28  4668.7  179.24
  4688.1  177.82  4698.1  177.48  4698.7   177.5  4728.7  178.71  4748.1  179.49
  4758.1  178.93  4758.7  178.97  4768.1  179.63  4768.7  179.63  4798.7   179.4
  4848.1  179.02  4858.1  178.49  4888.1  175.05  4918.1  170.48 4918.41  170.44
  4918.5  170.43  4928.1  169.32    4938  166.48  4948.1  163.58  4958.1  161.47
  4981.5  162.75  4986.5  156.75  5013.5  156.75  5018.5  162.75  5027.3  161.47
  5057.3  166.95    5062   167.1  5067.3  167.27 5081.39  166.46  5081.5  166.45
  5097.3  165.54  5117.3     166  5147.3  167.68  5157.3  167.34  5167.3  168.95
  5182.9  169.11  5187.3  169.16  5192.9  168.93  5207.3  168.34  5282.9  168.24
  5297.3  168.22  5302.9  168.85  5307.3  169.35  5317.3  168.48  5335.4  169.38
  5337.3  169.47  5357.3  168.42  5377.3  169.06  5397.3  168.47  5427.3   169.2
  5437.3  169.85  5447.3  169.72  5457.3  170.59  5467.3   172.2  5487.3  170.23
  5517.3  169.58  5527.3  169.79  5537.3   171.6  5547.3  175.69  5567.3  171.01
  5577.3  169.91  5587.3  173.18  5597.3  170.89  5617.3  169.66  5627.3  172.78
  5637.3  173.66  5647.3  172.69  5657.3  172.66  5677.3  174.76  5697.3  175.46
  5725.4  174.89  5727.3  174.85  5735.4  175.13  5747.3  175.54  5755.4  175.47
  5757.3  175.45  5787.3  176.93  5797.3  176.15  5807.3   176.2  5827.3  177.61
  5835.4  177.65  5843.8   177.7  5853.8  177.04  5863.8  178.05  5873.8  177.81
  5883.8  178.42  5893.8  177.54  5895.4  177.54  5900.4  177.53  5910.4  177.52
  5913.8  177.52  5930.4   176.6  5933.8  176.41  5940.4  176.61  5953.8  177.01
  5973.8  176.69  5993.8  177.46  6003.8  177.29  6013.8  176.05  6023.8  176.83
  6033.8  176.61  6040.4  177.17  6050.4  178.01  6063.8  179.14  6093.8  179.31
  6103.8   178.6  6110.4  179.48  6113.8  179.93  6130.4  180.35  6133.8  180.44
  6153.8   181.4  6170.4  182.99  6183.8  184.27  6200.4   184.9  6203.8  185.03
  6243.8  189.36  6263.8  188.88
BR D #Mann= 3
 4304.50    0.13  4981.5   0.042  5018.5    0.13
BR D Banks=4981.50,5018.50

Type RM Length L Ch R = 1 ,40499.9,760.5,760.5,760.5
BEGIN DESCRIPTION:
Downstream Section of Bridge/Culvert/Weir
END DESCRIPTION:
#Sta/Elev= 30
  4304.5  188.47  4308.1  190.33  4698.1  177.47  4748.1  179.48  4848.1  179.01
  4928.1  169.31  4958.1  161.46  4981.5  162.74  4986.5  156.74  5013.5  156.74
  5018.5  162.74  5027.3  161.46  5057.3  166.94  5097.3  165.53  5167.3  168.94
  5397.3  168.46  5467.3  172.19  5527.3  169.78  5547.3  175.68  5577.3   169.9
  5587.3  173.17  5617.3  169.65  5637.3  173.65  5657.3  172.65  5827.3   177.6
  6013.8  176.04  6063.8  179.13  6103.8  178.59  6243.8  189.35  6263.8  188.87
#Mann= 3 , 1 , 0
 4304.50    0.13       0  4981.5   0.042       0  5018.5    0.13       0
#XS Ineff= 2 , 0
       0    4909  177.78    5092       0  178.53
Bank Sta=4981.50,5018.50
Exp/Cntr=0.5,0.3

Type RM Length L Ch R = 1 ,39739.4,1089.2,1089.2,1089.2
BEGIN DESCRIPTION:
Sandy Creek 40.0
END DESCRIPTION:
#Sta/Elev= 30
  4011.8  181.66  4551.8  173.72  4621.8  171.83  4731.8  171.08  4771.8  169.39
  4861.8  162.77  4881.8  163.04  4901.8   166.1  4931.8  166.94  4943.1  165.89
  4953.1  161.69  4958.7   162.3  4961.7   156.3  5038.3   156.3  5041.3   162.3
  5043.1  161.68  5063.1  166.59  5143.1  165.48  5238.2  168.68  5408.2  166.74
  5438.2  167.16  5538.2  173.02  5628.2  174.46  5648.2  173.77  5758.2  174.92
  5838.2  177.09  5878.2  181.36  5928.2  184.47  5968.2  189.47  6003.8  197.53
#Mann= 3 , 1 , 0
 4011.80    0.13       0  4958.7   0.042       0  5041.3    0.13       0
Bank Sta=4958.70,5041.30
Exp/Cntr=0.3,0.1

Type RM Length L Ch R = 1 ,38650.2,1432.2,1432.2,1432.2
BEGIN DESCRIPTION:
Sandy Creek 39.0
END DESCRIPTION:
#Sta/Elev= 30
  3882.9  182.87  3982.9  182.22  4192.9  179.21  4422.9   163.4  4442.9  163.48
  4462.9   162.3  4512.9  161.88  4522.9  163.57  4532.9  164.19  4652.9  167.09
  4862.9  167.81  4882.9  167.15  4912.9  164.04  4932.9  163.87  4958.7  161.66
  4961.7  155.66  5038.3  155.66  5041.3  161.66    5088  169.75    5098  170.05
    5138  168.05    5198  170.29    5458  175.46    5498  176.95    5568  175.44
    5848  179.91    5928  183.74    6048  192.27    6058  192.36  6111.4  197.14
#Mann= 3 , 1 , 0
 3882.90    0.13       0  4958.7   0.042       0  5041.3    0.13       0
Bank Sta=4958.70,5041.30
Exp/Cntr=0.3,0.1

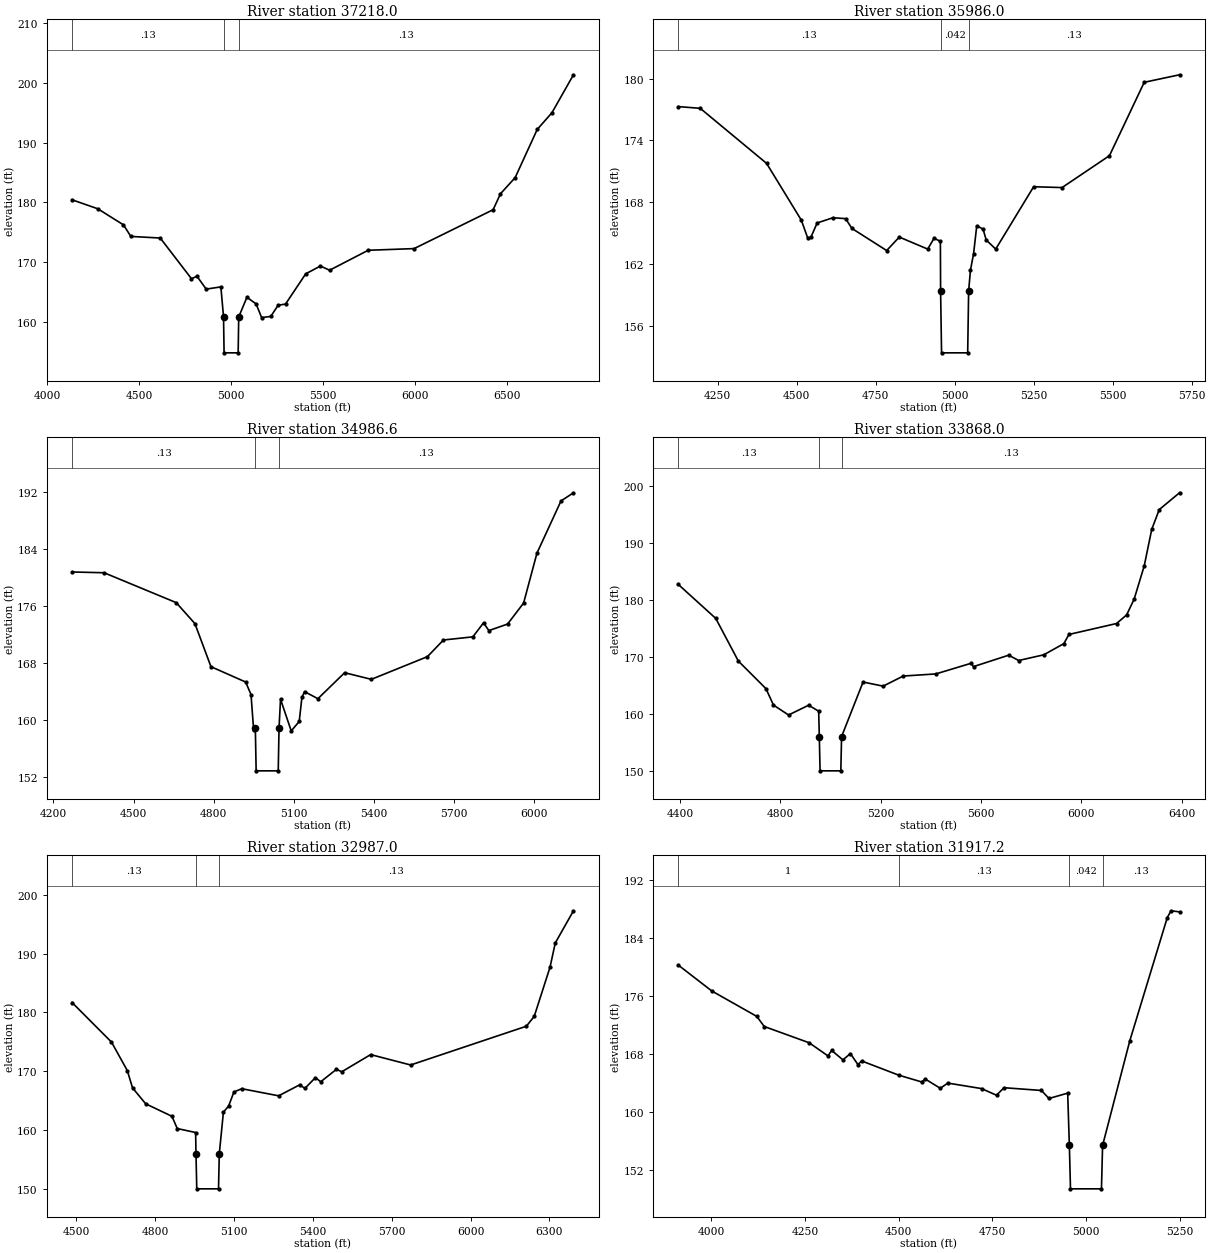
Type RM Length L Ch R = 1 ,37218.0,1232,1232,1232
BEGIN DESCRIPTION:
Sandy Creek 37.0
END DESCRIPTION:
#Sta/Elev= 30
  4134.2  180.44  4274.2  178.94  4414.2  176.24  4454.2  174.31  4614.2  174.04
  4784.2  167.23  4814.2  167.64  4864.2  165.49  4944.2  165.86  4958.7  160.82
  4961.7  154.82  5038.3  154.82  5041.3  160.82    5086  164.12    5136  163.01
    5166  160.72    5216  160.92    5256   162.8    5296  162.98    5406  168.05
    5486  169.35    5536  168.65    5746  171.99    5996  172.27    6426  178.78
    6466  181.45    6546  184.16    6666  192.22    6746  195.01  6863.3  201.37
#Mann= 3 , 1 , 0
 4134.20    0.13       0  4958.7   0.042       0  5041.3    0.13       0
Bank Sta=4958.70,5041.30
Exp/Cntr=0.3,0.1

Type RM Length L Ch R = 1 ,35986.0,999.4,999.4,999.4
BEGIN DESCRIPTION:
Sandy Creek 36.0
END DESCRIPTION:
#Sta/Elev= 30
  4124.9  177.28  4194.9  177.11  4404.9  171.76  4514.9  166.24  4534.9  164.52
  4544.9  164.57  4564.9  165.97  4614.9  166.48  4654.9  166.39  4674.9  165.44
  4784.9  163.29  4824.9   164.6  4914.9  163.43  4934.9  164.49  4954.9  164.18
  4955.6  159.35  4958.6  153.35  5041.3  153.35  5044.3  159.35    5050  161.37
    5060  162.99    5070   165.7    5090  165.37    5100  164.31    5130  163.43
    5250  169.49    5340  169.41    5490  172.51    5600  179.64  5711.7  180.37
#Mann= 3 , 1 , 0
 4124.90    0.13       0  4955.6   0.042       0  5044.3    0.13       0
Bank Sta=4955.60,5044.30
Exp/Cntr=0.3,0.1

Type RM Length L Ch R = 1 ,34986.6,1118.6,1118.6,1118.6
BEGIN DESCRIPTION:
Sandy Creek 35.0
END DESCRIPTION:
#Sta/Elev= 30
  4269.5  180.82  4389.5  180.71  4659.5  176.51  4729.5  173.56  4789.5  167.51
  4919.5  165.35  4939.5  163.59  4949.5  158.54  4955.7  158.87  4958.7  152.87
  5041.4  152.87  5044.4  158.87    5050  162.94    5090  158.48    5120  159.81
    5130  163.19    5140     164    5190  163.01    5290  166.66    5390  165.73
    5600  168.92    5660  171.26    5770   171.7    5810  173.67    5830  172.58
    5900   173.5    5960  176.45    6010  183.47    6100   190.8  6146.7  191.95
#Mann= 3 , 1 , 0
 4269.50    0.13       0  4955.7   0.042       0  5044.4    0.13       0
Bank Sta=4955.70,5044.40
Exp/Cntr=0.3,0.1

Type RM Length L Ch R = 1 ,33868.0,881,881,881
BEGIN DESCRIPTION:
Sandy Creek 34.0
END DESCRIPTION:
#Sta/Elev= 30
  4393.1  182.71  4543.1  176.73  4633.1  169.26  4743.1  164.43  4773.1  161.55
  4833.1  159.82  4913.1  161.53  4953.1  160.48  4955.6  156.04  4958.6  150.04
  5041.3  150.04  5044.3  156.04  5129.9  165.59  5209.9  164.87  5289.9  166.64
  5419.9  167.01  5559.9  168.87  5569.9  168.29  5709.9  170.29  5749.9  169.36
  5849.9  170.36  5929.9  172.32  5949.9  173.92  6139.9  175.84  6179.9  177.35
  6209.9  180.12  6249.9  185.92  6279.9  192.33  6309.9  195.79  6390.6  198.73
#Mann= 3 , 1 , 0
 4393.10    0.13       0  4955.6   0.042       0  5044.3    0.13       0
Bank Sta=4955.60,5044.30
Exp/Cntr=0.3,0.1

Type RM Length L Ch R = 1 ,32987.0,1069.8,1069.8,1069.8
BEGIN DESCRIPTION:
Sandy Creek 33.0
END DESCRIPTION:
#Sta/Elev= 30
  4484.4   181.7  4634.4  174.96  4694.4  170.12  4714.4  167.17  4764.4  164.45
  4864.4  162.32  4884.4  160.24  4954.4  159.56  4955.7  155.97  4958.7  149.97
  5041.4  149.97  5044.4  155.97    5060  163.02    5080  164.09    5100  166.47
    5130  167.02    5270  165.81    5350  167.68    5370  167.08    5410  168.91
    5430   168.2    5490  170.33    5510   169.9    5620  172.83  5772.1  171.06
  6212.1  177.66  6242.1  179.34  6302.1  187.71  6322.1  191.84  6391.3  197.32
#Mann= 3 , 1 , 0
 4484.40    0.13       0  4955.7   0.042       0  5044.4    0.13       0
Bank Sta=4955.70,5044.40
Exp/Cntr=0.3,0.1

Type RM Length L Ch R = 1 ,31917.2,774.6,774.6,774.6
BEGIN DESCRIPTION:
Sandy Creek 32.0
END DESCRIPTION:
#Sta/Elev= 30
  3911.2  180.32  4001.2  176.72  4121.2  173.21  4141.2  171.81  4261.2  169.56
  4311.2  167.75  4321.2   168.5  4351.2   167.2  4371.2  168.07  4391.2  166.55
  4401.2  167.05  4499.9  165.09  4561.2  164.15  4571.2  164.54  4611.2  163.27
  4631.2  163.99  4721.2  163.23  4761.2  162.31  4781.2  163.35  4881.2  162.97
  4901.2  161.86  4951.2   162.6  4955.7  155.37  4958.7  149.37  5041.4  149.37
  5044.4  155.37  5117.1  169.85  5217.1  186.87  5227.1  187.81  5249.8  187.66
#Mann= 4 , 1 , 0
 3911.20       1       0  4499.9    0.13       0  4955.7   0.042       0
  5044.4    0.13       0
Bank Sta=4955.70,5044.40
Exp/Cntr=0.3,0.1

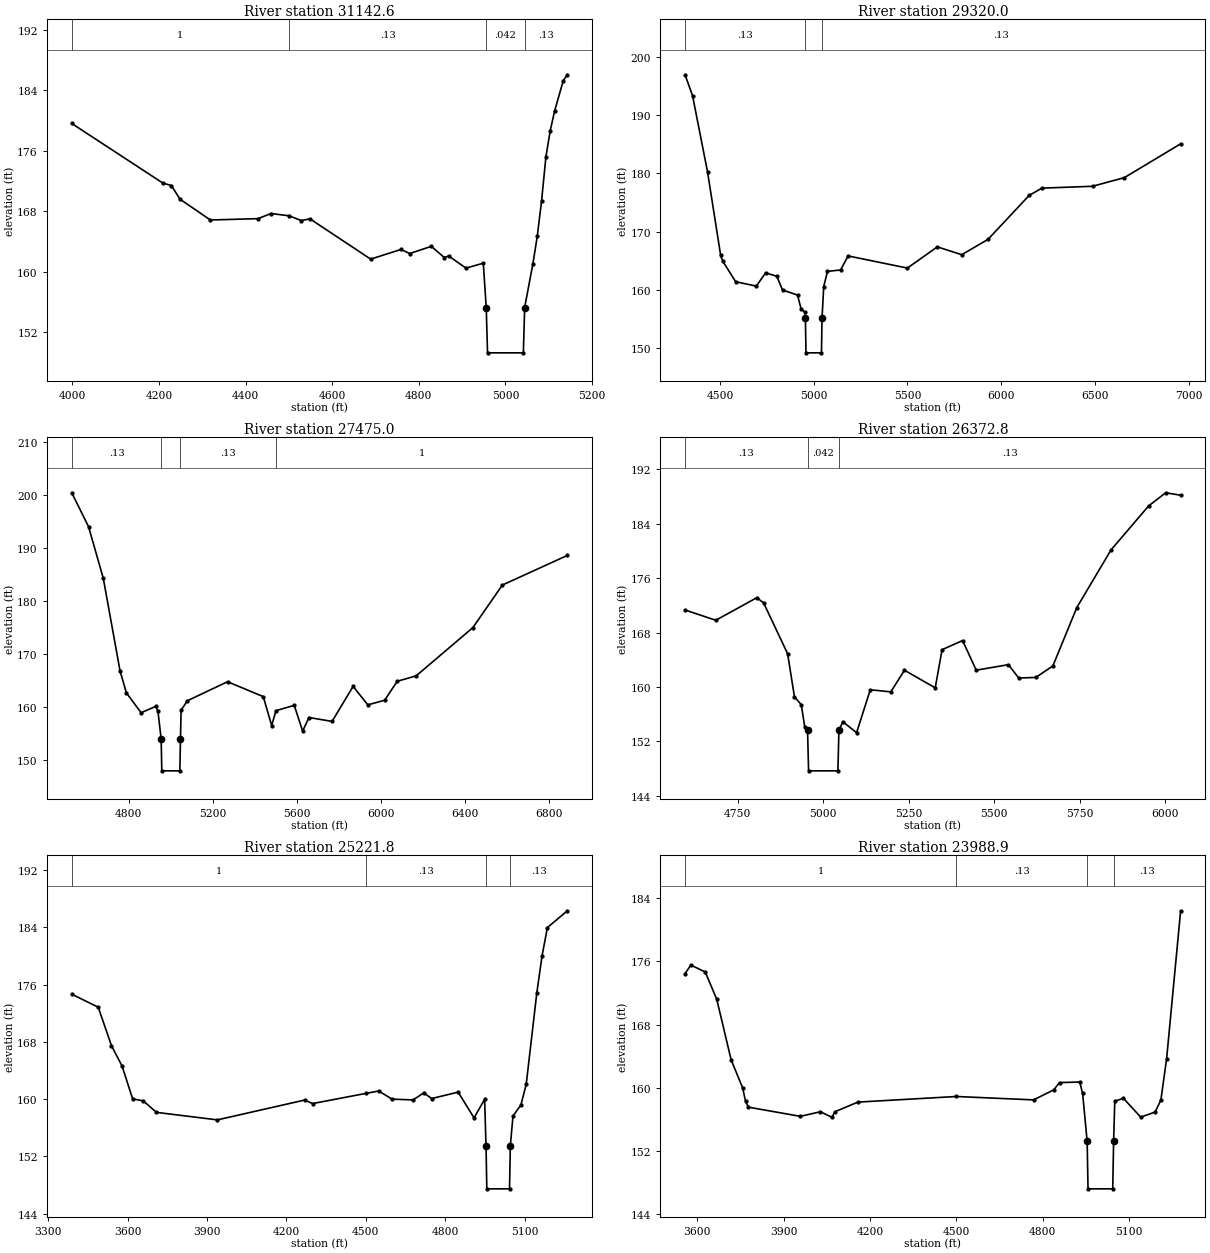
Type RM Length L Ch R = 1 ,31142.6,1822.6,1822.6,1822.6
BEGIN DESCRIPTION:
Sandy Creek 31.0
END DESCRIPTION:
#Sta/Elev= 30
  3998.8  179.61  4208.8  171.73  4228.8  171.39  4248.8  169.58  4318.8  166.83
  4428.8  167.01  4458.8  167.69  4499.9  167.39  4528.8  166.76  4548.8  166.98
  4688.8  161.65  4758.8  162.93  4778.8  162.39  4828.8  163.34  4858.8  161.86
  4868.8  162.07  4908.8  160.46  4948.8  161.11  4955.6  155.24  4958.6  149.24
  5041.3  149.24  5044.3  155.24  5063.4  161.06  5073.4  164.67  5083.4  169.39
  5093.4  175.21  5103.4  178.68  5113.4  181.25  5133.4  185.28  5142.8  186.06
#Mann= 4 , 1 , 0
 3998.80       1       0  4499.9    0.13       0  4955.6   0.042       0
  5044.3    0.13       0
Bank Sta=4955.60,5044.30
Exp/Cntr=0.3,0.1

Type RM Length L Ch R = 1 ,29320.0,1845,1845,1845
BEGIN DESCRIPTION:
Sandy Creek 30.0
END DESCRIPTION:
#Sta/Elev= 30
  4313.4  196.96  4353.4  193.35  4433.4  180.24  4503.4  165.88  4513.4  164.96
  4583.4  161.36  4693.4  160.61  4743.4  162.89  4803.4   162.3  4833.4  159.94
  4913.4  159.07  4933.4  156.59  4953.4  156.15  4955.6  155.13  4958.6  149.13
  5041.3  149.13  5044.3  155.13  5053.4  160.53  5073.4  163.14  5143.4  163.39
  5183.4   165.8  5499.7  163.71  5659.7  167.36  5789.7  166.01  5929.7  168.64
  6149.7  176.21  6217.8  177.46  6487.8  177.78  6657.8  179.27    6958  185.08
#Mann= 3 , 1 , 0
 4313.40    0.13       0  4955.6   0.042       0  5044.3    0.13       0
Bank Sta=4955.60,5044.30
Exp/Cntr=0.3,0.1

Type RM Length L Ch R = 1 ,27475.0,1102.2,1102.2,1102.2
BEGIN DESCRIPTION:
Sandy Creek 27.0
END DESCRIPTION:
#Sta/Elev= 30
  4528.8  200.44  4608.8  194.02  4678.8  184.27  4758.8  166.71  4788.8  162.62
  4858.8  158.87  4928.8  160.08  4938.8  159.15  4954.1  153.89  4957.1  147.89
  5042.9  147.89  5045.9  153.89  5048.8  159.35  5078.8  161.14  5269.7  164.73
  5439.7  161.92  5479.7  156.45  5499.9  159.26    5587  160.27    5627   155.4
    5657  157.97    5767  157.23    5867  163.85    5937  160.36    6017  161.23
    6077  164.82    6167  165.84  6436.9  174.97  6576.9     183  6885.9   188.6
#Mann= 4 , 1 , 0
 4528.80    0.13       0  4954.1   0.042       0  5045.9    0.13       0
  5499.9       1       0
Bank Sta=4954.10,5045.90
Exp/Cntr=0.3,0.1

Type RM Length L Ch R = 1 ,26372.8,1151,1151,1151
BEGIN DESCRIPTION:
Sandy Creek 26.0
END DESCRIPTION:
#Sta/Elev= 30
  4595.8  171.31  4685.8   169.8  4805.8  173.12  4825.8  172.33  4895.8  164.88
  4915.8  158.55  4935.8   157.4  4945.8  154.15  4954.1  153.68  4957.1  147.68
  5042.9  147.68  5045.9  153.68  5057.6  154.88  5097.6  153.29  5137.6  159.59
  5197.6  159.28  5237.6  162.46  5327.6  159.87  5347.6  165.48  5407.6  166.82
  5447.6  162.47  5541.8  163.28  5571.8  161.32  5621.8   161.4  5671.8   163.1
  5741.8  171.67  5841.8  180.13  5951.8   186.6  6001.8  188.53  6045.5  188.17
#Mann= 3 , 1 , 0
 4595.80    0.13       0  4954.1   0.042       0  5045.9    0.13       0
Bank Sta=4954.10,5045.90
Exp/Cntr=0.3,0.1

Type RM Length L Ch R = 1 ,25221.8,1232.9,1232.9,1232.9
BEGIN DESCRIPTION:
Sandy Creek 25.0
END DESCRIPTION:
#Sta/Elev= 30
  3388.8  174.67  3488.8  172.85  3538.8  167.48  3578.8  164.63  3618.8  160.04
  3658.8  159.76  3708.8  158.15  3938.8   157.1  4268.8  159.87  4298.8  159.38
  4499.9   160.8  4548.8  161.14  4598.8     160  4678.8  159.89  4718.8  160.88
  4748.8  160.08  4848.8  160.98  4908.8  157.38  4948.8  159.97  4954.1  153.46
  4957.1  147.46  5042.9  147.46  5045.9  153.46    5056  157.64    5086  159.19
    5106  162.08    5146  174.86    5166  180.06    5186  183.98  5261.3  186.33
#Mann= 4 , 1 , 0
 3388.80       1       0  4499.9    0.13       0  4954.1   0.042       0
  5045.9    0.13       0
Bank Sta=4954.10,5045.90
Exp/Cntr=0.3,0.1

Type RM Length L Ch R = 1 ,23988.9,1443.2,1443.2,1443.2
BEGIN DESCRIPTION:
Sandy Creek 24.0
END DESCRIPTION:
#Sta/Elev= 30
  3558.3  174.44  3578.3  175.52  3628.3  174.65  3668.3  171.19  3718.3  163.53
  3758.3  159.98  3768.3  158.28  3778.3  157.55  3958.3  156.39  4028.3  156.97
  4068.3  156.26  4078.3  156.97  4158.3  158.19  4499.9   158.9  4768.3  158.47
  4838.3  159.75  4858.3  160.66  4928.3  160.73  4938.3  159.29  4954.1  153.22
  4957.1  147.22  5042.9  147.22  5045.9  153.22    5050  158.31    5080  158.67
    5140  156.29    5190  156.93    5210  158.45    5230   163.7  5278.6  182.39
#Mann= 4 , 1 , 0
 3558.30       1       0  4499.9    0.13       0  4954.1   0.042       0
  5045.9    0.13       0
Bank Sta=4954.10,5045.90
Exp/Cntr=0.3,0.1