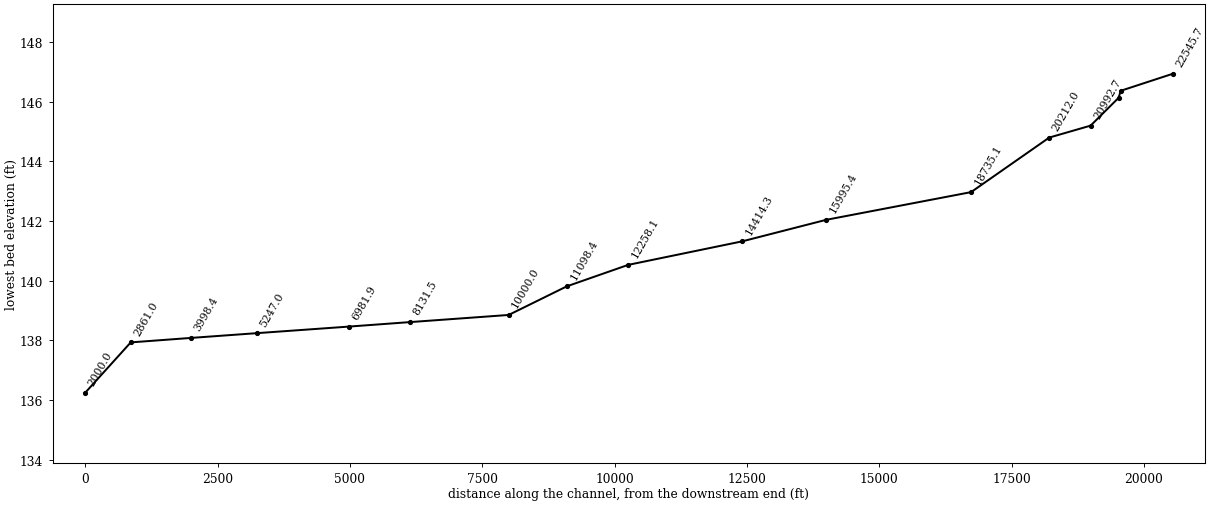
HEC-RAS study 020822_SANDY_CREEK.prj: Sandy Creek

--- 020822_SANDY_CREEK.g01 (geometry) --- (continued)

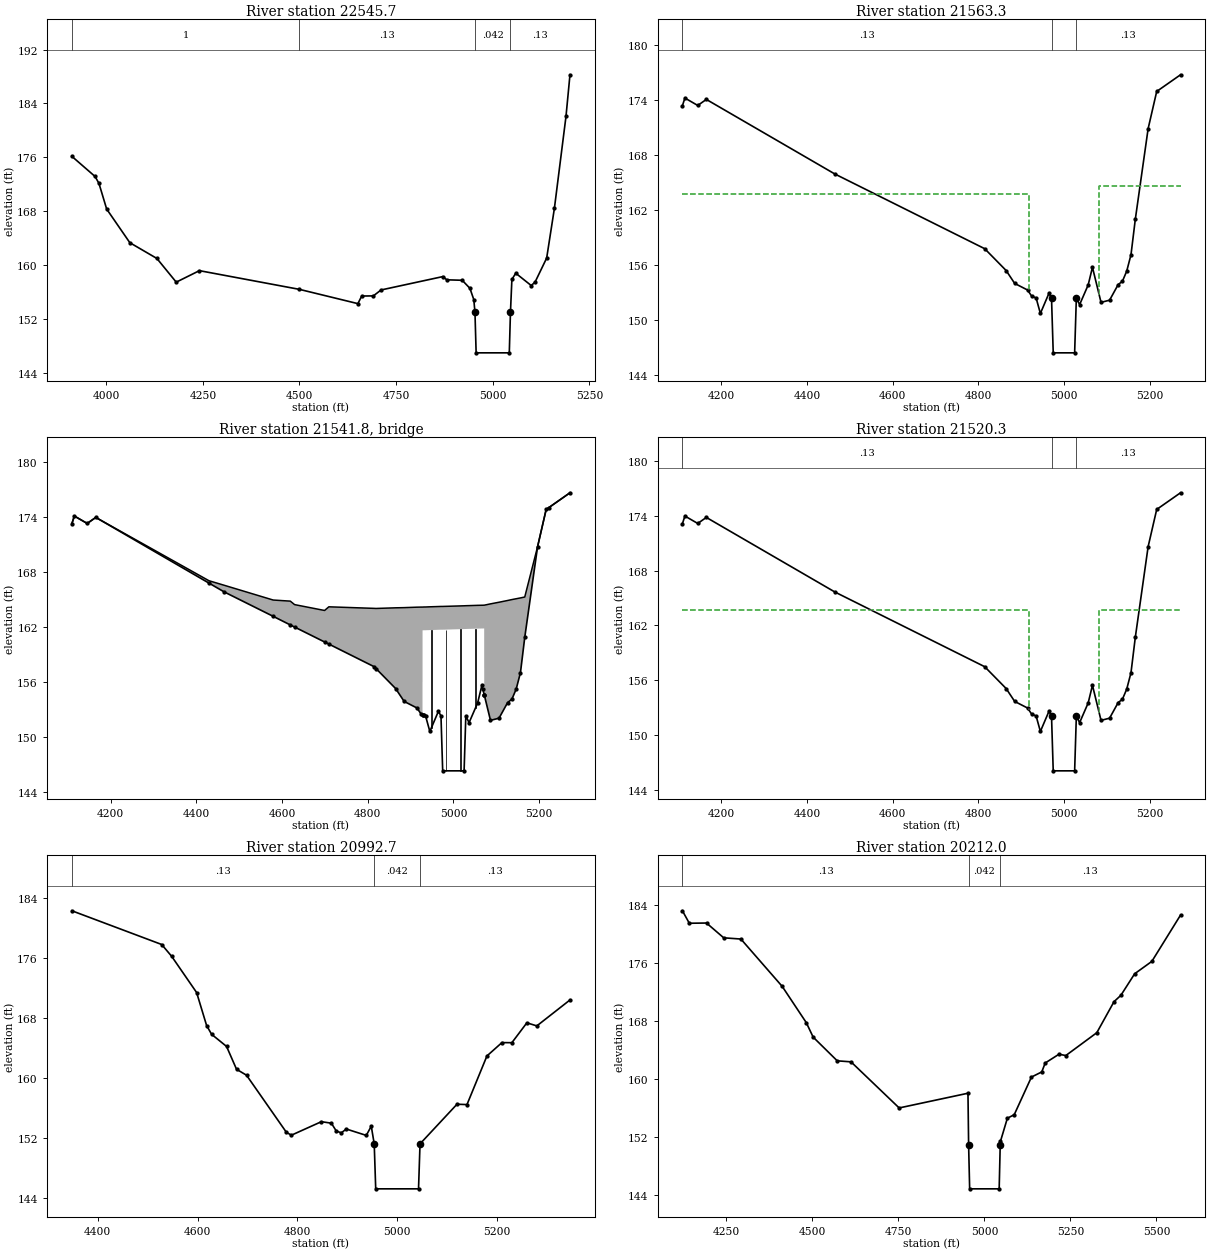
Type RM Length L Ch R = 1 ,22545.7,982.4,982.4,982.4
BEGIN DESCRIPTION:
Sandy Creek 23.0
END DESCRIPTION:
#Sta/Elev= 30
  3911.1  176.13  3971.1  173.14  3981.1  172.12  4001.1   168.3  4061.1   163.3
  4131.1  160.96  4181.1  157.44  4241.1  159.15  4499.9  156.37  4651.1  154.25
  4661.1  155.38  4691.1   155.4  4711.1  156.28  4871.1  158.27  4881.1  157.79
  4921.1  157.72  4941.1  156.52  4951.1  154.84  4954.1  152.94  4957.1  146.94
  5042.9  146.94  5045.9  152.94  5049.6  157.84  5059.6  158.77  5099.6  156.94
  5109.6  157.45  5139.6  161.02  5159.6   168.4  5189.6  182.06  5199.9  188.25
#Mann= 4 , 1 , 0
 3911.10       1       0  4499.9    0.13       0  4954.1   0.042       0
  5045.9    0.13       0
Bank Sta=4954.10,5045.90
Exp/Cntr=0.3,0.1

Type RM Length L Ch R = 1 ,21563.3,43,43,43
BEGIN DESCRIPTION:
Upstream Section of Bridge/Culvert/Weir
END DESCRIPTION:
#Sta/Elev= 30
  4109.2  173.36    4115  174.19    4145  173.38    4165  174.04    4465   165.9
    4815  157.74    4865  155.36    4885  153.95    4915  153.23    4925  152.54
    4935  152.37    4945  150.67    4965  152.87    4971  152.37    4975  146.37
    5025  146.37    5029  152.37  5036.6  151.63  5056.6  153.78  5066.6  155.71
  5086.6  151.88  5106.6  152.12  5126.6  153.82  5136.6  154.19  5146.6  155.29
  5156.6  157.09  5166.6  160.93  5196.6  170.85  5216.6  174.91  5272.2  176.73
#Mann= 3 , 1 , 0
 4109.20    0.13       0    4971   0.045       0    5029    0.13       0
#XS Ineff= 2 , 0
       0  4917.8  163.72 5082.17       0  164.56
Bank Sta=4971.00,5029.00
Exp/Cntr=0.5,0.3

Type RM Length L Ch R = 3 ,21541.8,,,
BEGIN DESCRIPTION:
Taylors Store Rd-TOR
Structure ID: Taylors Store Rd-Bridge
Approximate Survey Structure
END DESCRIPTION:
Bridge Culvert--1,0,-1,-1, 0
Deck Dist Width WeirC Skew NumUp NumDn MinLoCord MaxHiCord MaxSubmerge Is_Ogee
10,23,2.6,,45,45,,,0.95,0,1,1,,
  4109.2    4115    4145    4165  4429.2    4465  4579.2  4619.2  4629.2  4699.2
  4709.2    4815  4819.2    4865    4885    4915    4925 4927.91    4928  4931.5
    4935    4945    4965    4971    4975    5025    5029  5036.6  5056.6  5066.6
  5068.5 5071.89    5072  5072.2  5086.6  5106.6  5126.6  5136.6  5146.6  5156.6
  5166.6  5196.6  5216.6  5222.2  5272.2
   173.3  174.13  173.32  173.98  167.07  166.57  164.96  164.84  164.46  163.82
  164.22  164.05  164.04  164.11  164.13  164.18  164.19  164.19  164.19   164.2
   164.2  164.22  164.25  164.26  164.26  164.33  164.34  164.35  164.38  164.39
  164.39   164.4   164.4   164.4  164.54  164.72  164.91  165.01   165.1  165.19
  165.29  170.79  174.85  175.03  176.67
   173.3  174.13  173.32  173.98  166.81  165.84  163.18  162.24  162.01  160.38
  160.15  157.68  157.48   155.3  153.89  153.17  152.48  152.43  161.65  161.66
  161.66  161.68  161.71  161.72  161.72  161.79   161.8  161.81  161.84  161.85
  161.85  161.86  154.62  154.58  151.82  152.06  153.76  154.13  155.23  157.03
  160.87  170.79  174.85  175.03  176.67
  4109.2    4115    4145    4165  4429.2    4465  4579.2  4619.2  4629.2  4699.2
  4709.2    4815  4819.2    4865    4885    4915    4925 4927.91    4928  4931.5
    4935    4945    4965    4971    4975    5025    5029  5036.6  5056.6  5066.6
  5068.5 5071.89    5072  5072.2  5086.6  5106.6  5126.6  5136.6  5146.6  5156.6
  5166.6  5196.6  5216.6  5222.2  5272.2
  173.24  174.08  173.27  173.93  167.07  166.57  164.96  164.84  164.46  163.82
  164.22  164.05  164.04  164.11  164.13  164.18  164.19  164.19  164.19   164.2
   164.2  164.22  164.25  164.26  164.26  164.33  164.34  164.35  164.38  164.39
  164.39   164.4   164.4   164.4  164.54  164.72  164.91  165.01   165.1  165.19
  165.29  170.74   174.8  174.98  176.61
  173.17     174  173.19  173.85  166.68  165.71  163.05  162.11  161.88  160.25
  160.02  157.55  157.35  155.17  153.76  153.04  152.35   152.3  161.52  161.53
  161.53  161.55  161.58  161.59  161.59  161.66  161.67  161.68  161.71  161.72
  161.72  161.73  154.49  154.45  151.69  151.93  153.63     154   155.1   156.9
  160.74  170.66  174.72   174.9  176.54
Pier Skew, UpSta & Num, DnSta & Num=,4948.6, 2 ,4948.6, 2 , 0 , 0 , 0 ,,
       2       2
   149.9  162.69
       2       2
  149.77  162.56
Pier Skew, UpSta & Num, DnSta & Num=,4982.9, 2 ,4982.9, 2 , 0 , 0 , 0 ,,
       2       2
  145.31  162.73
       2       2
  145.18   162.6
Pier Skew, UpSta & Num, DnSta & Num=,5017.1, 2 ,5017.1, 2 , 0 , 0 , 0 ,,
       2       2
  145.31  162.78
       2       2
  145.18  162.65
Pier Skew, UpSta & Num, DnSta & Num=,5051.4, 2 ,5051.4, 2 , 0 , 0 , 0 ,,
       2       2
  152.05  162.83
       2       2
  151.92   162.7
Abutment Skew #Up #Dn=, 2 , 2
 4927.80 4931.50
  161.65  152.37
 4927.80 4931.50
  161.52  152.24
Abutment Skew #Up #Dn=, 2 , 2
 5068.50 5072.09
  155.29  161.86
 5068.50 5072.09
  155.16  161.73
BR Coef= 1 , 1 , 0 ,1.25, 0 ,,,0.8,0,2,0,
Wspro=,,,, 1 ,,,, 0 ,,,, 0 ,,,,-1 ,-1 ,-1 , 0 , 0 , 0 , 0 , 0
BC Design=,, 0 ,, 0 ,,,,,,
BR U #Sta/Elev= 45
  4109.2   173.3    4115  174.13    4145  173.32    4165  173.98  4429.2  166.81
    4465  165.84  4579.2  163.18  4619.2  162.24  4629.2  162.01  4699.2  160.38
  4709.2  160.15    4815  157.68  4819.2  157.48    4865   155.3    4885  153.89
    4915  153.17    4925  152.48 4927.91  152.43    4928  152.43  4931.5  152.37
    4935  152.31    4945  150.61    4965  152.81    4971  152.31    4975  146.31
    5025  146.31    5029  152.31  5036.6  151.57  5056.6  153.72  5066.6  155.65
  5068.5  155.29 5071.89  154.64    5072  154.62  5072.2  154.58  5086.6  151.82
  5106.6  152.06  5126.6  153.76  5136.6  154.13  5146.6  155.23  5156.6  157.03
  5166.6  160.87  5196.6  170.79  5216.6  174.85  5222.2  175.03  5272.2  176.67
BR U #Mann= 3
 4109.20    0.13    4971   0.045    5029    0.13
BR U Banks=4971.00,5029.00
BR D #Sta/Elev= 45
  4109.2  173.17    4115     174    4145  173.19    4165  173.85  4429.2  166.68
    4465  165.71  4579.2  163.05  4619.2  162.11  4629.2  161.88  4699.2  160.25
  4709.2  160.02    4815  157.55  4819.2  157.35    4865  155.17    4885  153.76
    4915  153.04    4925  152.35 4927.91   152.3    4928   152.3  4931.5  152.24
    4935  152.18    4945  150.48    4965  152.68    4971  152.18    4975  146.18
    5025  146.18    5029  152.18  5036.6  151.44  5056.6  153.59  5066.6  155.52
  5068.5  155.16 5071.89  154.51    5072  154.49  5072.2  154.45  5086.6  151.69
  5106.6  151.93  5126.6  153.63  5136.6     154  5146.6   155.1  5156.6   156.9
  5166.6  160.74  5196.6  170.66  5216.6  174.72  5222.2   174.9  5272.2  176.54
BR D #Mann= 3
 4109.20    0.13    4971   0.045    5029    0.13
BR D Banks=4971.00,5029.00

Type RM Length L Ch R = 1 ,21520.3,527.6,527.6,527.6
BEGIN DESCRIPTION:
Downstream Section of Bridge/Culvert/Weir
END DESCRIPTION:
#Sta/Elev= 30
  4109.2  173.12    4115  173.95    4145  173.14    4165   173.8    4465  165.66
    4815   157.5    4865  155.12    4885  153.71    4915  152.99    4925   152.3
    4935  152.13    4945  150.43    4965  152.63    4971  152.13    4975  146.13
    5025  146.13    5029  152.13  5036.6  151.39  5056.6  153.54  5066.6  155.47
  5086.6  151.64  5106.6  151.88  5126.6  153.58  5136.6  153.95  5146.6  155.05
  5156.6  156.85  5166.6  160.69  5196.6  170.61  5216.6  174.67  5272.2  176.49
#Mann= 3 , 1 , 0
 4109.20    0.13       0    4971   0.045       0    5029    0.13       0
#XS Ineff= 2 , 0
       0  4917.8   163.7 5082.17       0   163.7
Bank Sta=4971.00,5029.00
Exp/Cntr=0.5,0.3

Type RM Length L Ch R = 1 ,20992.7,780.7,780.7,780.7
BEGIN DESCRIPTION:
Sandy Creek 21.0
END DESCRIPTION:
#Sta/Elev= 30
  4348.2   182.3  4528.2   177.8  4548.2  176.22  4598.2  171.39  4618.2  166.99
  4628.2  165.82  4658.2   164.2  4678.2  161.15  4698.2  160.36  4778.2  152.73
  4788.2  152.36  4848.2  154.16  4868.2  153.96  4878.2   152.9  4888.2  152.68
  4898.2  153.18  4938.2  152.33  4948.2  153.56  4954.1   151.2  4957.1   145.2
  5042.9   145.2  5045.9   151.2    5120  156.49    5140  156.44    5180  162.93
    5210  164.71    5230   164.7    5260  167.35    5280  166.94  5346.4   170.4
#Mann= 3 , 1 , 0
 4348.20    0.13       0  4954.1   0.042       0  5045.9    0.13       0
Bank Sta=4954.10,5045.90
Exp/Cntr=0.3,0.1

Type RM Length L Ch R = 1 ,20212.0,1476.9,1476.9,1476.9
BEGIN DESCRIPTION:
Sandy Creek 20.0
END DESCRIPTION:
#Sta/Elev= 30
  4122.2  183.16  4142.2  181.44  4192.2  181.47  4242.2  179.43  4292.2  179.26
  4412.2  172.73  4482.2  167.73  4502.2  165.73  4572.2  162.46  4612.2  162.32
  4752.2  155.96  4952.2  157.99  4954.1   150.8  4957.1   144.8  5042.9   144.8
  5045.9   150.8  5046.7  151.36  5066.7  154.54  5086.7  155.03  5136.7  160.22
  5166.7  160.93  5176.7  162.16  5216.7  163.37  5236.7  163.19  5326.7  166.34
  5376.7  170.62  5396.7   171.5  5436.7  174.47  5486.7  176.18    5570  182.56
#Mann= 3 , 1 , 0
 4122.20    0.13       0  4954.1   0.042       0  5045.9    0.13       0
Bank Sta=4954.10,5045.90
Exp/Cntr=0.3,0.1

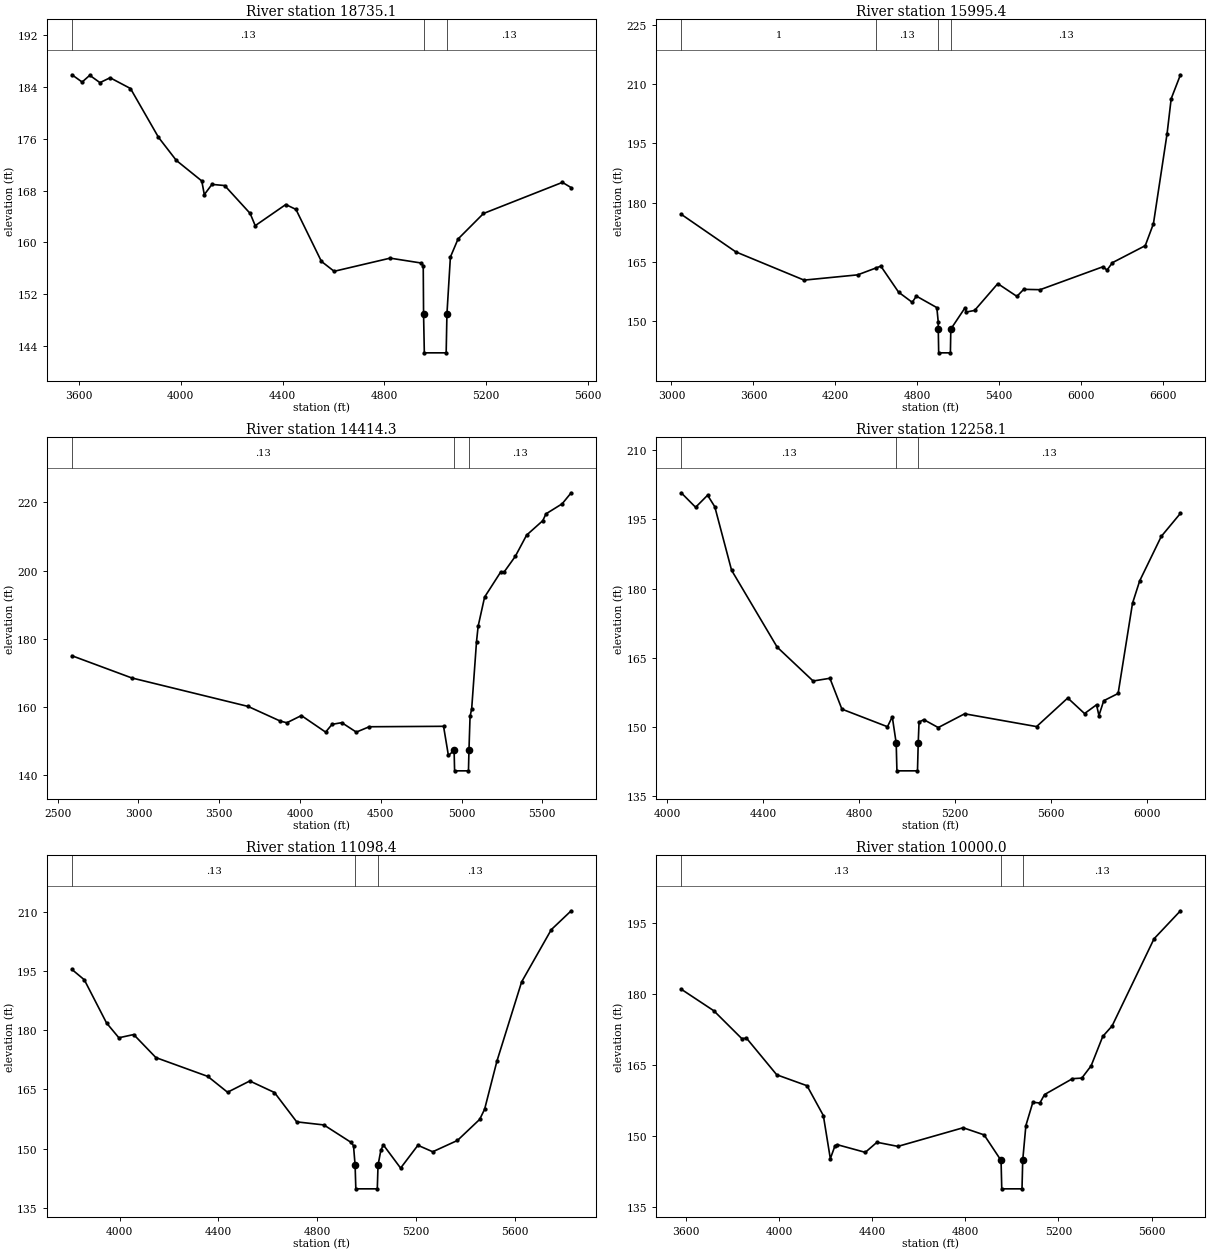
Type RM Length L Ch R = 1 ,18735.1,2739.7,2739.7,2739.7
BEGIN DESCRIPTION:
Sandy Creek 17.0
END DESCRIPTION:
#Sta/Elev= 30
  3572.8  185.87  3612.8  184.75  3642.8  185.79  3682.8  184.66  3722.8  185.41
  3802.8  183.75  3912.8  176.22  3982.8  172.66  4082.8  169.49  4092.8  167.38
  4122.8  168.96  4172.8  168.78  4272.8  164.48  4292.8  162.59  4412.8  165.85
  4452.8   165.1  4552.8  157.08  4602.8  155.55  4822.8  157.58  4942.8  156.84
  4952.8  156.44  4954.1  148.97  4957.1  142.97  5042.9  142.97  5045.9  148.97
  5059.5  157.75  5089.5  160.53  5189.5  164.47  5499.5  169.27    5534  168.46
#Mann= 3 , 1 , 0
 3572.80    0.13       0  4954.1   0.042       0  5045.9    0.13       0
Bank Sta=4954.10,5045.90
Exp/Cntr=0.3,0.1

Type RM Length L Ch R = 1 ,15995.4,1581.1,1581.1,1581.1
BEGIN DESCRIPTION:
Sandy Creek 16.0
END DESCRIPTION:
#Sta/Elev= 30
  3071.2  177.08  3471.2  167.57  3971.2  160.43  4363.5  161.76  4499.9  163.53
  4533.5  163.96  4663.5  157.38  4763.5  154.81  4793.5  156.39  4943.5  153.48
  4953.5  149.94  4954.1  148.04  4957.1  142.04  5042.9  142.04  5045.9  148.04
    5150  153.43    5160  152.37    5220  152.76    5390  159.54    5530  156.32
    5580   158.1    5700  158.01    6160  163.81    6190  162.97    6230  164.85
    6470  169.14    6530   174.7    6630  197.48    6660  206.31  6727.9  212.36
#Mann= 4 , 1 , 0
 3071.20       1       0  4499.9    0.13       0  4954.1   0.042       0
  5045.9    0.13       0
Bank Sta=4954.10,5045.90
Exp/Cntr=0.3,0.1

Type RM Length L Ch R = 1 ,14414.3,2156.2,2156.2,2156.2
BEGIN DESCRIPTION:
Sandy Creek 15.0
END DESCRIPTION:
#Sta/Elev= 30
  2588.8  175.05  2958.8  168.55  3678.8   160.2  3878.8  155.89  3918.8  155.41
  4008.8  157.52  4158.8  152.67  4198.8  154.95  4258.8  155.44  4348.8  152.67
  4428.8  154.24  4888.8  154.37  4918.8  145.82  4954.1  147.32  4957.1  141.32
    5043  141.32    5046  147.32  5052.8  157.27  5062.8  159.47  5092.8  179.21
  5102.8  183.69  5142.8  192.24  5242.8  199.62  5262.8  199.54  5332.8  204.18
  5402.8   210.4  5502.8  214.63  5522.8  216.64  5622.8  219.58  5678.7  222.81
#Mann= 3 , 1 , 0
 2588.80    0.13       0  4954.1   0.042       0    5046    0.13       0
Bank Sta=4954.10,5046.00
Exp/Cntr=0.3,0.1

Type RM Length L Ch R = 1 ,12258.1,1159.7,1159.7,1159.7
BEGIN DESCRIPTION:
Sandy Creek 12.0
END DESCRIPTION:
#Sta/Elev= 30
  4057.7  200.73  4117.7  197.59  4167.7   200.2  4197.7  197.71  4267.7  183.96
  4457.7  167.32  4607.7  159.98  4677.7  160.57  4727.7  153.89  4917.7  150.08
  4937.7  152.24  4954.1  146.53  4957.1  140.53  5042.9  140.53  5045.9  146.53
  5049.4   151.1  5069.4  151.61  5129.4   149.9  5239.4  152.88  5539.4  150.11
  5669.4   156.3  5739.4  152.93  5789.4  154.83  5799.4   152.5  5819.4  155.71
  5879.4  157.28  5939.4  176.81  5969.4  181.67  6059.4  191.29  6139.3  196.28
#Mann= 3 , 1 , 0
 4057.70    0.13       0  4954.1   0.042       0  5045.9    0.13       0
Bank Sta=4954.10,5045.90
Exp/Cntr=0.3,0.1

Type RM Length L Ch R = 1 ,11098.4,1098.4,1098.4,1098.4
BEGIN DESCRIPTION:
Sandy Creek 11.0
END DESCRIPTION:
#Sta/Elev= 30
  3807.1  195.36  3857.1  192.75  3947.1  181.82  3997.1  178.06  4057.1  178.88
  4147.1  173.04  4357.1  168.28  4437.1  164.27  4527.1  167.12  4627.1   164.2
  4717.1  156.77  4827.1  155.99  4937.1  151.58  4947.1  150.73  4953.5  145.81
  4956.5  139.81  5043.4  139.81  5046.4  145.81  5057.8  149.57  5067.8  150.95
  5137.8  145.06  5207.8  150.84  5267.8   149.2  5367.8  152.06  5457.8  157.39
  5477.8  159.95  5527.8  172.16  5627.8  192.22  5747.8  205.44  5828.4  210.22
#Mann= 3 , 1 , 0
 3807.10    0.13       0  4953.5   0.042       0  5046.4    0.13       0
Bank Sta=4953.50,5046.40
Exp/Cntr=0.3,0.1

Type RM Length L Ch R = 1 ,10000.0,1868.5,1868.5,1868.5
BEGIN DESCRIPTION:
Sandy Creek 10.0
END DESCRIPTION:
#Sta/Elev= 30
  3580.8  181.04  3720.8  176.48  3840.8   170.6  3860.8   170.7  3990.8  162.95
  4120.8  160.64  4190.8  154.34  4220.8  145.23  4240.8  147.95  4250.8  148.18
  4370.8  146.56  4420.8  148.69  4510.8  147.82  4790.8  151.76  4880.8  150.25
  4953.5  144.85  4956.5  138.85  5043.4  138.85  5046.4  144.85    5060  152.22
    5090  157.15    5120  156.98    5140  158.77    5260  162.13    5300  162.25
    5340  164.84    5390  171.06    5430  173.27    5610  191.69  5723.4  197.61
#Mann= 3 , 1 , 0
 3580.80    0.13       0  4953.5   0.042       0  5046.4    0.13       0
Bank Sta=4953.50,5046.40
Exp/Cntr=0.3,0.1

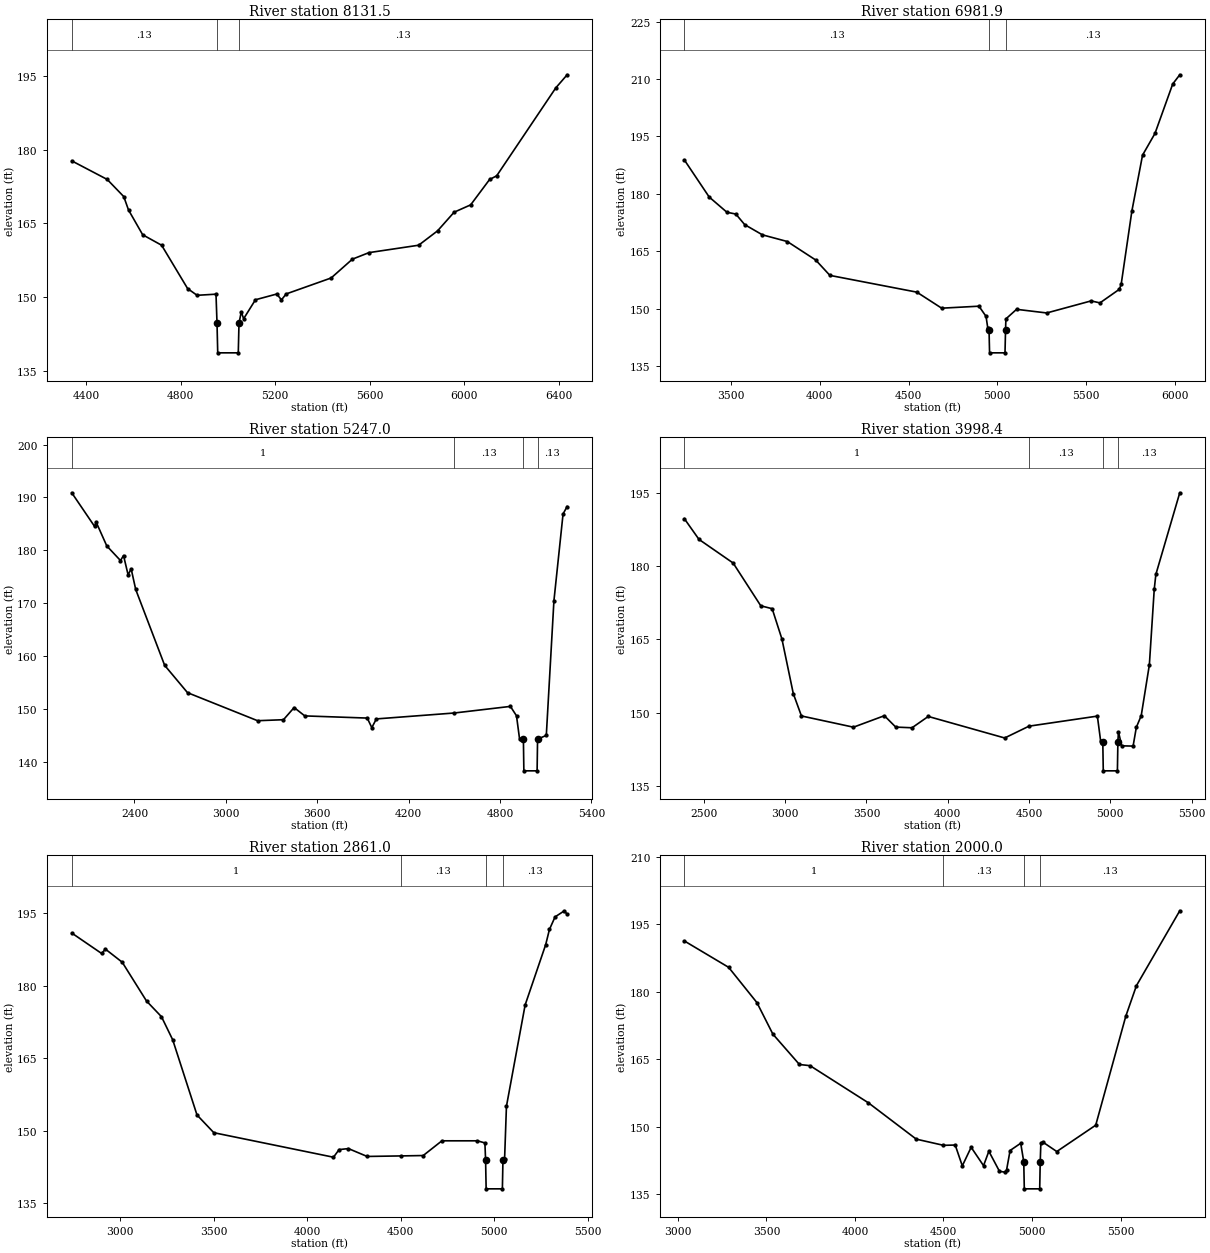
Type RM Length L Ch R = 1 ,8131.5,1149.6,1149.6,1149.6
BEGIN DESCRIPTION:
Sandy Creek 8.0
END DESCRIPTION:
#Sta/Elev= 30
  4339.2  177.75  4489.2  173.96  4559.2  170.46  4579.2  167.74  4639.2  162.68
  4719.2  160.55  4829.2  151.71  4869.2  150.34  4949.2  150.57  4953.5  144.61
  4956.5  138.61  5043.4  138.61  5046.4  144.61    5056  146.98    5066  145.56
    5116  149.43    5206   150.6    5226  149.41    5246  150.62    5436  153.87
    5526  157.71    5596  159.04  5806.1  160.55  5886.1  163.48  5956.1  167.28
  6026.1  168.78  6106.1  173.95  6136.1   174.7  6386.1  192.63  6434.1   195.3
#Mann= 3 , 1 , 0
 4339.20    0.13       0  4953.5   0.042       0  5046.4    0.13       0
Bank Sta=4953.50,5046.40
Exp/Cntr=0.3,0.1

Type RM Length L Ch R = 1 ,6981.9,1734.9,1734.9,1734.9
BEGIN DESCRIPTION:
Sandy Creek 6.0
END DESCRIPTION:
#Sta/Elev= 30
  3236.6  188.86  3376.6  179.17  3476.6  175.19  3526.6  174.73  3576.6  171.96
  3676.6  169.29  3816.6  167.55  3976.6  162.72  4056.6   158.7  4546.6  154.32
  4686.6  150.13  4896.6  150.65  4936.6  147.99  4946.6  144.88  4953.5  144.46
  4956.5  138.46  5043.5  138.46  5046.5  144.46  5048.6  147.33  5108.6  149.83
  5278.6  148.88  5528.6  152.03  5578.6  151.51  5688.6  155.09  5698.6   156.5
  5758.6  175.56  5818.6  190.12  5888.6  195.79  5988.6  208.71  6028.3  211.12
#Mann= 3 , 1 , 0
 3236.60    0.13       0  4953.5   0.042       0  5046.5    0.13       0
Bank Sta=4953.50,5046.50
Exp/Cntr=0.3,0.1

Type RM Length L Ch R = 1 ,5247.0,1248.6,1248.6,1248.6
BEGIN DESCRIPTION:
Sandy Creek 5.0
END DESCRIPTION:
#Sta/Elev= 30
  1988.2  190.88  2138.2  184.51  2148.2  185.34  2218.2  180.82  2308.2  178.05
  2328.2     179  2358.2  175.34  2378.2  176.49  2408.2  172.57  2598.2  158.21
  2748.2  153.04  3208.2  147.73  3378.2  147.92  3448.2  150.22  3518.2  148.64
  3928.2  148.23  3958.2  146.42  3988.2  148.07  4499.9  149.19  4868.2  150.44
  4908.2  148.66  4928.2  144.29  4953.5  144.24  4956.5  138.24  5043.5  138.24
  5046.5  144.24  5103.9  144.95  5153.9  170.44  5213.9  186.88  5240.7  188.28
#Mann= 4 , 1 , 0
 1988.20       1       0  4499.9    0.13       0  4953.5   0.042       0
  5046.5    0.13       0
Bank Sta=4953.50,5046.50
Exp/Cntr=0.3,0.1

Type RM Length L Ch R = 1 ,3998.4,1137.4,1137.4,1137.4
BEGIN DESCRIPTION:
Sandy Creek 4.0
END DESCRIPTION:
#Sta/Elev= 30
  2380.3  189.72  2470.3  185.48  2680.3  180.64  2850.3  171.88  2920.3  171.29
  2980.3  165.08  3050.3  153.89  3100.3  149.32  3420.3  147.02  3610.3  149.37
  3680.3  147.04  3780.3   146.9  3880.3  149.22  4350.3  144.81  4499.9  147.23
  4920.3  149.29  4940.3  144.22  4953.6  144.08  4956.6  138.08  5043.5  138.08
  5046.5  144.08    5050  146.09    5070   143.2    5140  143.15    5160     147
    5190  149.38    5240  159.78    5270  175.24    5280  178.31    5427  195.03
#Mann= 4 , 1 , 0
 2380.30       1       0  4499.9    0.13       0  4953.6   0.042       0
  5046.5    0.13       0
Bank Sta=4953.60,5046.50
Exp/Cntr=0.3,0.1

Type RM Length L Ch R = 1 ,2861.0,861,861,861
BEGIN DESCRIPTION:
Sandy Creek 3.0
END DESCRIPTION:
#Sta/Elev= 30
  2739.9  190.93  2899.9  186.69  2919.9   187.6  3009.9  184.88  3139.9  176.84
  3219.9  173.59  3279.9  168.81  3409.9  153.23  3499.9  149.56  4139.9  144.48
  4169.9  146.06  4219.9  146.27  4319.9  144.64  4499.9  144.75  4619.9  144.83
  4719.9  147.88  4909.9  147.88  4949.9  147.44  4953.5  143.93  4956.5  137.93
  5043.4  137.93  5046.4  143.93  5055.1  144.02  5065.1  155.03  5165.1  176.03
  5275.1  188.53  5295.1  191.67  5325.1  194.27  5375.1  195.54  5389.8   194.8
#Mann= 4 , 1 , 0
 2739.90       1       0  4499.9    0.13       0  4953.5   0.042       0
  5046.4    0.13       0
Bank Sta=4953.50,5046.40
Exp/Cntr=0.3,0.1

Type RM Length L Ch R = 1 ,2000.0,1631.6,1631.6,1631.6
BEGIN DESCRIPTION:
Sandy Creek 2.0
END DESCRIPTION:
#Sta/Elev= 30
  3036.3  191.26  3286.3  185.41  3446.3  177.57  3536.3  170.58  3686.3  163.84
  3746.3  163.58  4076.3  155.32  4346.3  147.27  4499.9   145.9  4566.3  145.96
  4606.3  141.34  4656.3  145.46  4726.3  141.38  4756.3  144.58  4816.3  140.13
  4846.3  139.95  4856.3   140.4  4876.3  144.75  4936.3  146.36  4953.5  142.24
  4956.5  136.24  5043.5  136.24  5046.5  142.24    5050  146.32    5060  146.65
    5140  144.52    5360  150.37    5530  174.58    5590  181.34  5834.7  197.96
#Mann= 4 , 1 , 0
 3036.30       1       0  4499.9    0.13       0  4953.5   0.042       0
  5046.5    0.13       0
Bank Sta=4953.50,5046.50
Exp/Cntr=0.3,0.1