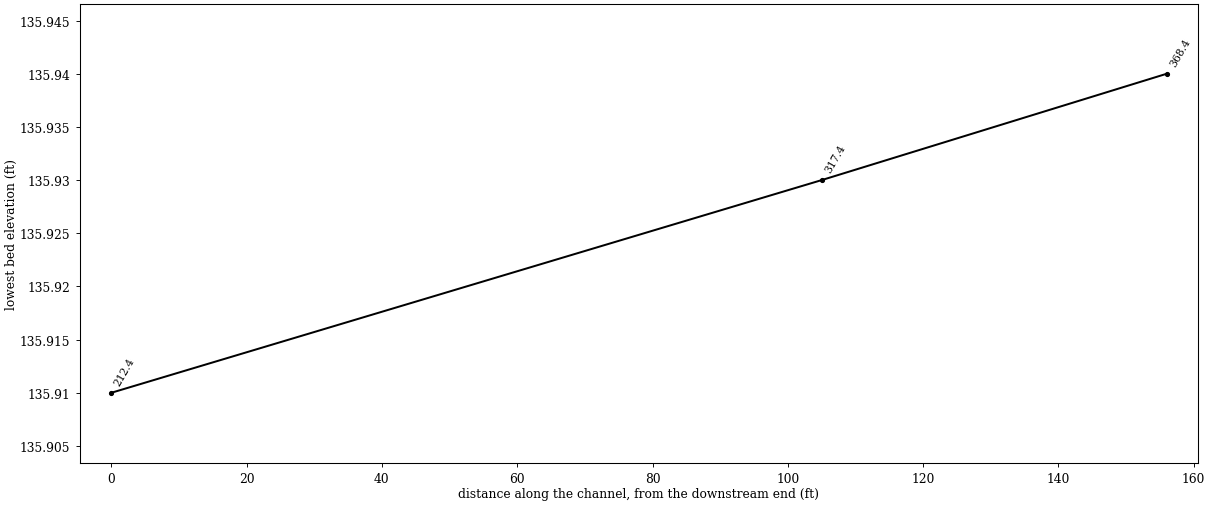
HEC-RAS study 020822_SANDY_CREEK.prj: Sandy Creek

--- 020822_SANDY_CREEK.g01 (geometry) --- (continued)

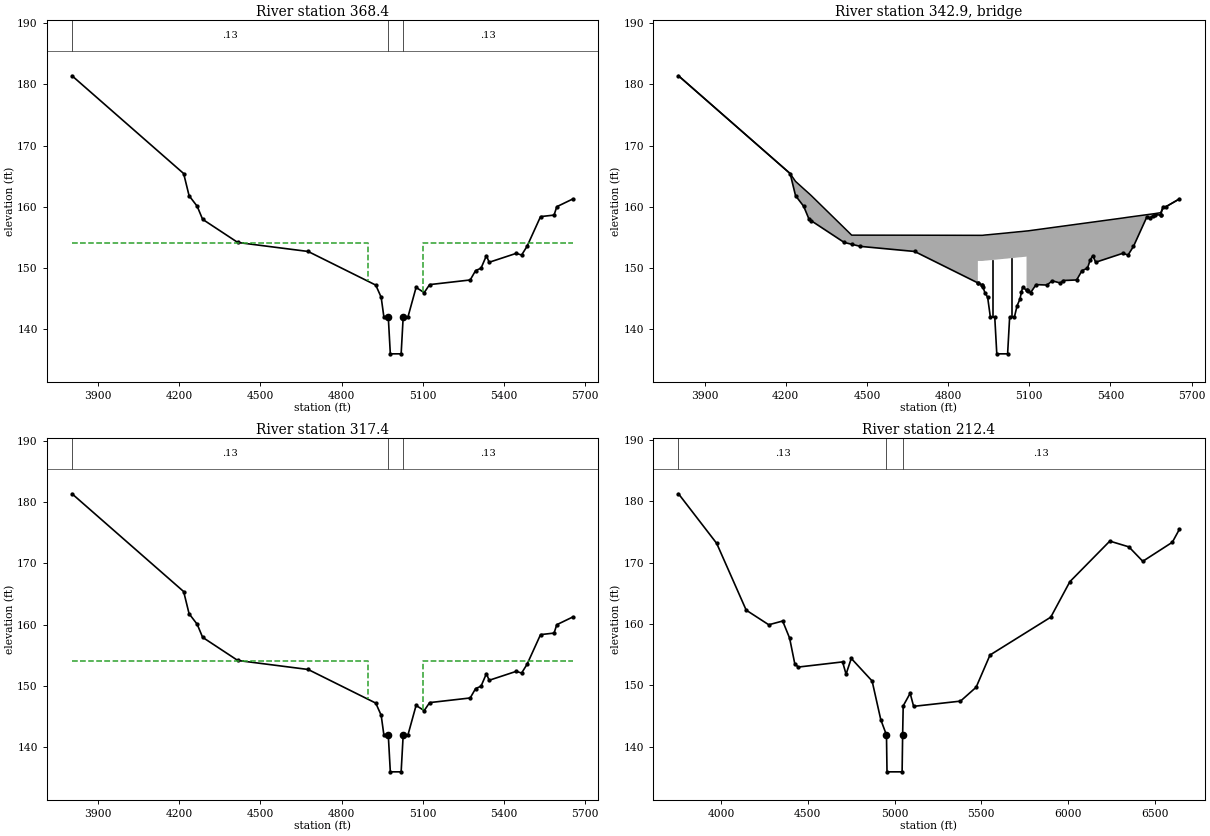
Type RM Length L Ch R = 1 ,368.4,51,51,51
BEGIN DESCRIPTION:
Upstream Section of Bridge/Culvert/Weir
END DESCRIPTION:
#Sta/Elev= 30
  3803.6  181.41  4216.2  165.42  4236.2   161.8  4266.2  160.07  4286.2  157.94
  4416.2  154.15  4676.2  152.68  4926.2  147.18  4946.2  145.19  4956.2  141.96
  4972.5  141.94    4980  135.94    5020  135.94  5027.5  141.94  5045.2  141.98
  5075.2   146.8  5105.2  145.95  5125.2  147.26  5275.2  148.02  5295.2  149.56
  5315.2  149.94  5335.2     152  5345.2  150.91  5445.2  152.37  5465.2   152.1
  5485.2  153.51  5535.2  158.38  5585.2  158.63  5595.2     160  5655.2  161.28
#Mann= 3 , 1 , 0
 3803.60    0.13       0  4972.5   0.042       0  5027.5    0.13       0
#XS Ineff= 2 , 0
       0    4899     154    5101       0     154
Bank Sta=4972.50,5027.50
Exp/Cntr=0.5,0.3

Type RM Length L Ch R = 3 ,342.9,,,
BEGIN DESCRIPTION:
Cooper Rd-1-TOR
Structure ID: Cooper Rd_sandy-Bridge
Approximate Survey Structure
END DESCRIPTION:
Bridge Culvert--1,0,-1,-1, 0
Deck Dist Width WeirC Skew NumUp NumDn MinLoCord MaxHiCord MaxSubmerge Is_Ogee
10,31,2.6,,54,54,,,0.95,0,1,1,,
  3803.6  4216.2  4236.2  4266.2  4286.2  4293.6  4416.2  4443.6  4476.2  4676.2
 4909.91    4910  4925.7  4926.2    4929  4936.2  4946.2  4956.2  4972.5    4980
    5020  5027.5  5045.2  5055.2  5065.2    5071  5075.2 5089.89    5090  5095.7
  5105.2  5125.2  5165.2  5185.2  5215.2  5225.2  5275.2  5295.2  5315.2  5325.2
  5335.2  5345.2  5445.2  5465.2  5485.2  5535.2  5545.2  5555.7  5565.2  5585.2
  5585.7  5595.2  5605.2  5655.2
  181.41  165.42  164.14  162.94  162.15  161.85  156.54  155.35  155.35  155.34
  155.32  155.32  155.32  155.32  155.33  155.37  155.41  155.45  155.52  155.55
  155.72  155.76  155.83  155.88  155.92  155.94  155.96  156.03  156.03  156.05
  156.11  156.23  156.47  156.59  156.77  156.83  157.13  157.25  157.37  157.43
  157.49  157.55  158.15  158.28   158.4   158.7  158.76  158.82  158.88  159.02
  159.02     160     160  161.28
  181.41  165.42   161.8  160.07  157.94  157.72  154.15  153.86  153.51  152.68
  147.54  151.13  151.13  151.13  151.14  151.18  151.22  151.26  151.33  151.36
  151.53  151.57  151.64  151.69  151.73  151.75  151.77  151.84  146.38  146.22
  145.95  147.26  147.19  147.88  147.51  147.93  148.02  149.56  149.94  151.29
     152  150.91  152.37   152.1  153.51  158.38  158.18  158.45  158.69  158.63
   158.7     160     160  161.28
  3803.6  4216.2  4236.2  4266.2  4286.2  4293.6  4416.2  4443.6  4476.2  4676.2
 4909.91    4910  4925.7  4926.2    4929  4936.2  4946.2  4956.2  4972.5    4980
    5020  5027.5  5045.2  5055.2  5065.2    5071  5075.2 5089.89    5090  5095.7
  5105.2  5125.2  5165.2  5185.2  5215.2  5225.2  5275.2  5295.2  5315.2  5325.2
  5335.2  5345.2  5445.2  5465.2  5485.2  5535.2  5545.2  5555.7  5565.2  5585.2
  5585.7  5595.2  5605.2  5655.2
   181.4  165.42  164.14  162.94  162.15  161.85  156.54  155.35  155.35  155.34
  155.32  155.32  155.32  155.32  155.33  155.37  155.41  155.45  155.52  155.55
  155.72  155.76  155.83  155.88  155.92  155.94  155.96  156.03  156.03  156.05
  156.11  156.23  156.47  156.59  156.77  156.83  157.13  157.25  157.37  157.43
  157.49  157.55  158.15  158.28   158.4   158.7  158.76  158.82  158.88  159.02
  159.02  159.99  159.99  161.27
   181.4  165.41  161.79  160.06  157.93  157.71  154.14  153.85   153.5  152.67
  147.53  151.12  151.12  151.12  151.13  151.17  151.21  151.25  151.32  151.35
  151.52  151.56  151.63  151.68  151.72  151.74  151.76  151.83  146.37  146.21
  145.94  147.25  147.18  147.87   147.5  147.92  148.01  149.55  149.93  151.28
  151.99   150.9  152.36  152.09   153.5  158.37  158.17  158.44  158.68  158.62
  158.69  159.99  159.99  161.27
Pier Skew, UpSta & Num, DnSta & Num=,4964.5, 2 ,4964.5, 2 , 0 , 0 , 0 ,,
       4       4
  140.95   152.3
       4       4
  140.94  152.29
Pier Skew, UpSta & Num, DnSta & Num=,5035.5, 2 ,5035.5, 2 , 0 , 0 , 0 ,,
       4       4
  140.95  152.61
       4       4
  140.94   152.6
Abutment Skew #Up #Dn=, 2 , 2
 4909.80 4929.00
  151.13  146.83
 4909.80 4929.00
  151.12  146.82
Abutment Skew #Up #Dn=, 2 , 2
 5071.00 5090.09
  145.98  151.84
 5071.00 5090.09
  145.97  151.83
BR Coef= 1 , 1 , 0 ,1.25, 0 ,,,0.8,0,2,0,
Wspro=,,,, 1 ,,,, 0 ,,,, 0 ,,,,-1 ,-1 ,-1 , 0 , 0 , 0 , 0 , 0
BC Design=,, 0 ,, 0 ,,,,,,
BR U #Sta/Elev= 54
  3803.6  181.41  4216.2  165.42  4236.2   161.8  4266.2  160.07  4286.2  157.94
  4293.6  157.72  4416.2  154.15  4443.6  153.86  4476.2  153.51  4676.2  152.68
 4909.91  147.54    4910  147.54  4925.7  147.19  4926.2  147.18    4929  146.83
  4936.2  145.93  4946.2  145.19  4956.2  141.96  4972.5  141.94    4980  135.94
    5020  135.94  5027.5  141.94  5045.2  141.98  5055.2  143.83  5065.2  144.84
    5071  145.98  5075.2   146.8 5089.89  146.38    5090  146.38  5095.7  146.22
  5105.2  145.95  5125.2  147.26  5165.2  147.19  5185.2  147.88  5215.2  147.51
  5225.2  147.93  5275.2  148.02  5295.2  149.56  5315.2  149.94  5325.2  151.29
  5335.2     152  5345.2  150.91  5445.2  152.37  5465.2   152.1  5485.2  153.51
  5535.2  158.38  5545.2  158.18  5555.7  158.45  5565.2  158.69  5585.2  158.63
  5585.7   158.7  5595.2     160  5605.2     160  5655.2  161.28
BR U #Mann= 3
 3803.60    0.13  4972.5   0.042  5027.5    0.13
BR U Banks=4972.50,5027.50
BR D #Sta/Elev= 54
  3803.6   181.4  4216.2  165.41  4236.2  161.79  4266.2  160.06  4286.2  157.93
  4293.6  157.71  4416.2  154.14  4443.6  153.85  4476.2   153.5  4676.2  152.67
 4909.91  147.53    4910  147.53  4925.7  147.18  4926.2  147.17    4929  146.82
  4936.2  145.92  4946.2  145.18  4956.2  141.95  4972.5  141.93    4980  135.93
    5020  135.93  5027.5  141.93  5045.2  141.97  5055.2  143.82  5065.2  144.83
    5071  145.97  5075.2  146.79 5089.89  146.37    5090  146.37  5095.7  146.21
  5105.2  145.94  5125.2  147.25  5165.2  147.18  5185.2  147.87  5215.2   147.5
  5225.2  147.92  5275.2  148.01  5295.2  149.55  5315.2  149.93  5325.2  151.28
  5335.2  151.99  5345.2   150.9  5445.2  152.36  5465.2  152.09  5485.2   153.5
  5535.2  158.37  5545.2  158.17  5555.7  158.44  5565.2  158.68  5585.2  158.62
  5585.7  158.69  5595.2  159.99  5605.2  159.99  5655.2  161.27
BR D #Mann= 3
 3803.60    0.13  4972.5   0.042  5027.5    0.13
BR D Banks=4972.50,5027.50

Type RM Length L Ch R = 1 ,317.4,105,105,105
BEGIN DESCRIPTION:
Downstream Section of Bridge/Culvert/Weir
END DESCRIPTION:
#Sta/Elev= 30
  3803.6   181.4  4216.2  165.41  4236.2  161.79  4266.2  160.06  4286.2  157.93
  4416.2  154.14  4676.2  152.67  4926.2  147.17  4946.2  145.18  4956.2  141.95
  4972.5  141.93    4980  135.93    5020  135.93  5027.5  141.93  5045.2  141.97
  5075.2  146.79  5105.2  145.94  5125.2  147.25  5275.2  148.01  5295.2  149.55
  5315.2  149.93  5335.2  151.99  5345.2   150.9  5445.2  152.36  5465.2  152.09
  5485.2   153.5  5535.2  158.37  5585.2  158.62  5595.2  159.99  5655.2  161.27
#Mann= 3 , 1 , 0
 3803.60    0.13       0  4972.5   0.042       0  5027.5    0.13       0
#XS Ineff= 2 , 0
       0    4899     154    5101       0     154
Bank Sta=4972.50,5027.50
Exp/Cntr=0.5,0.3

Type RM Length L Ch R = 1 ,212.4,0,0,0
BEGIN DESCRIPTION:
Sandy Creek 1.0
END DESCRIPTION:
#Sta/Elev= 30
  3755.5  181.21  3975.5  173.13  4145.5  162.25  4275.5  159.87  4355.5  160.48
  4395.5   157.7  4425.5  153.49  4445.5  152.98  4700.7  153.82  4720.7  151.82
  4750.7  154.39  4870.7  150.71  4920.7   144.4  4953.5  141.91  4956.5  135.91
  5043.5  135.91  5046.5  141.91  5049.8  146.66  5089.8  148.71  5109.8  146.58
  5379.8  147.43  5469.8  149.69  5549.8  154.94  5899.8  161.11  6009.8  166.89
  6239.8   173.5  6349.8  172.56  6429.8  170.21  6599.8  173.31  6641.1  175.45
#Mann= 3 , 1 , 0
 3755.50    0.13       0  4953.5   0.042       0  5046.5    0.13       0
Bank Sta=4953.50,5046.50
Exp/Cntr=0.3,0.1

Chan Stop Cuts=-1