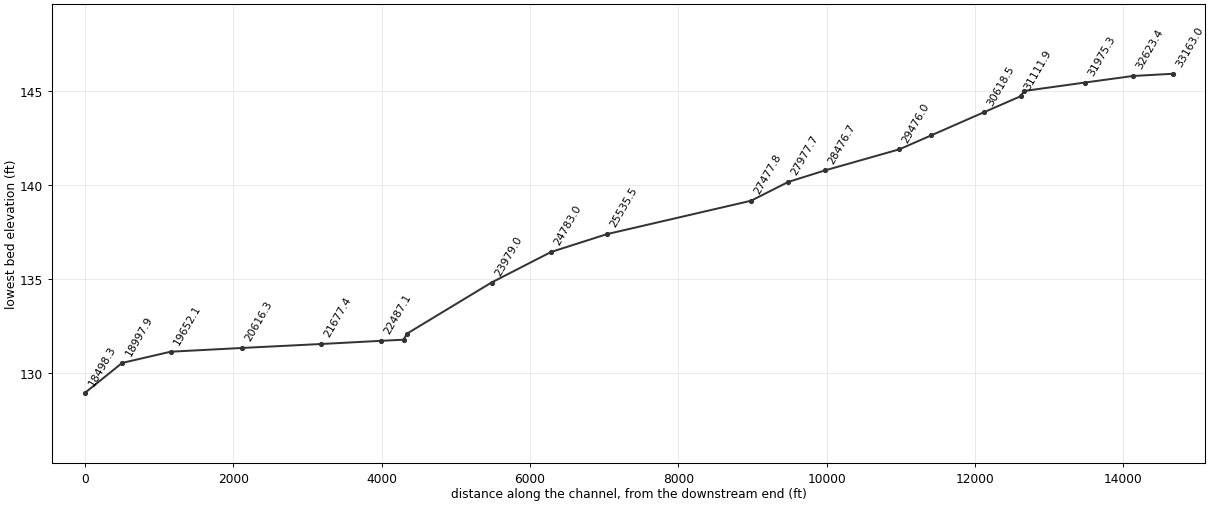
--- 020515_pig_basket_creek.prj (project) ---

Proj Title=Pig Basket Creek-changed
Current Plan=p01
Default Exp/Contr=.3,.1
English Units
Geom File=g01
Flow File=f01
Plan File=p01
Y Axis Title=Elevation
X Axis Title(PF)=Main Channel Distance
X Axis Title(XS)=Station
BEGIN DESCRIPTION:
NCFPM-Tar Pam Basin
END DESCRIPTION:
DSS Export Rating Curves= 0
DSS Export Rating Curve Sorted= 0
DSS Export Volume Flow Curves= 0
DXF OffsetX= 0
DXF OffsetY= 0
DXF ScaleX= 1
DXF ScaleY= 10

--- 020515_pig_basket_creek.p01 (plan) ---

Plan Title=Pig Basket Creek
Version=Version 3.0.1  Mar 2001
Short Identifier=Base Plan
Geom File=g01
Flow File=f01
Subcritical Flow
K Sum by GR= 0
Std Step Tol= 0.01
Critical Tol= 0.01
Num of Std Step Trials= 20
Max Error Tol= 0.3
Flow Tol Ratio= 0.001
Split Flow NTrial= 30
Split Flow Tol= 0.02
Split Flow Ratio= 0.02
Log Output Level= 0
Friction Slope Method= 1
Unsteady Friction Slope Method= 2
Parabolic Critical Depth
Global Vel Dist= 0 , 0 , 0
Global Log Level= 0
CheckData=True
Encroach Param=-1 ,0,0, 2
Encroach River=Main Stem
Encroach Reach=Reach - 1
Encroach Node=33163.0
       4      .7
Encroach Node=32623.4
       1    4299    5053
Encroach Node=31975.3
       4      .3
Encroach Node=31156.9
       1    4775    5059
Encroach Node=31134.4
       1    4775    5059
Encroach Node=31111.9
       1    4775    5059
Encroach Node=30618.5
       1    4450    5330
Encroach Node=29903.7
       4      .7
Encroach Node=29476.0
       4      .7
Encroach Node=28476.7
       4      .7
Encroach Node=27977.7
       1    4056    5053
Encroach Node=27477.8
       4      .7
Encroach Node=25535.5
       4      .7
Encroach Node=24783.0
       4      .7
Encroach Node=23979.0
       4      .7
Encroach Node=22837.6
       4      .7
Encroach Node=22815.1
       4      .7
Encroach Node=22792.6
       4      .7
Encroach Node=22487.1
       1    4270    5068
Encroach Node=21677.4
       4      .7
Encroach Node=20616.3
       1    3810    5075
Encroach Node=19652.1
       1    4145    5075
Encroach Node=18997.9
       4      .7
Encroach Node=18498.3
       4      .7
Encroach Node=18000.0
       4      .7
Encroach Node=17238.1
       4      .7
Encroach Node=16207.2
       1    4180    5047
Encroach Node=16184.2
       1    4180    5047
Encroach Node=16161.2
       1    4180    5047
Encroach Node=15500.0
       1    4490    5088
Encroach Node=14500.0
       1    4579    5811
Encroach Node=14104.6
       4      .7
Encroach Node=13500.0
       4      .7
Encroach Node=12749.2
       4      .7
Encroach Node=12085.4
       4      .7
Encroach Node=11529.3
       4      .7
Encroach Node=11000.0
       4      .7
Encroach Node=10500.0
       4      .7
Encroach Node=9676.9
       4      .7
Encroach Node=8773.2
       1    3500    5076
Encroach Node=8746.7
       1    3500    5076
Encroach Node=8720.2
       1    3500    5076
Encroach Node=8560.1
       1    3500    5100
Computation Interval=1HOUR
Output Interval=1HOUR
Run HTab= 0
Run UNet= 0
Run PostProcess= 0
UNET Theta= 1
UNET ZTol= 0.02
UNET ZSATol= 0.1
UNET MxIter= 20
UNET MaxInSteps= 20
UNET DtIC= 0
UNET DtMin= 0
UNET MaxCRTS= 20
UNET WFStab= 2
UNET SFStab= 1
UNET WFX= 1
UNET SFX= 1
UNET Convert EG Bridges=-1
UNET Use Existing IB Tables=-1
Instantaneous Interval=1HOUR
Write IC File= 0
Write Velocity= 0
Write Detailed= 0

--- 020515_pig_basket_creek.f01 (steady flow) ---

Flow Title=Pig Basket Creek
Version=Version 3.0.1  Mar 2001
Number of Profiles= 2
Profile Names=100-YEAR,AFW
River Rch & RM=Main Stem,Reach - 1       ,33163.0
    4320    4320
River Rch & RM=Main Stem,Reach - 1       ,31975.3
    4528    4528
River Rch & RM=Main Stem,Reach - 1       ,27477.8
    4824    4824
River Rch & RM=Main Stem,Reach - 1       ,20616.3
    5153    5153
River Rch & RM=Main Stem,Reach - 1       ,11529.3
    7155    7155
Boundary for River Rch & Prof#=Main Stem,Reach - 1       , 1
Up Type= 0
Dn Type= 1
Dn Known WS=126.82
Boundary for River Rch & Prof#=Main Stem,Reach - 1       , 2
Up Type= 0
Dn Type= 1
Dn Known WS=127.4
DSS Import GetInterval= 0
DSS Import GetPeak= 0
DSS Import FillOption= 0

--- 020515_pig_basket_creek.g01 (geometry) ---

Geom Title=Geom 01 by CodeH2 for Windows

River Reach=Main Stem,Reach - 1
Reach XY= 2
              .5             .95              .5             .05

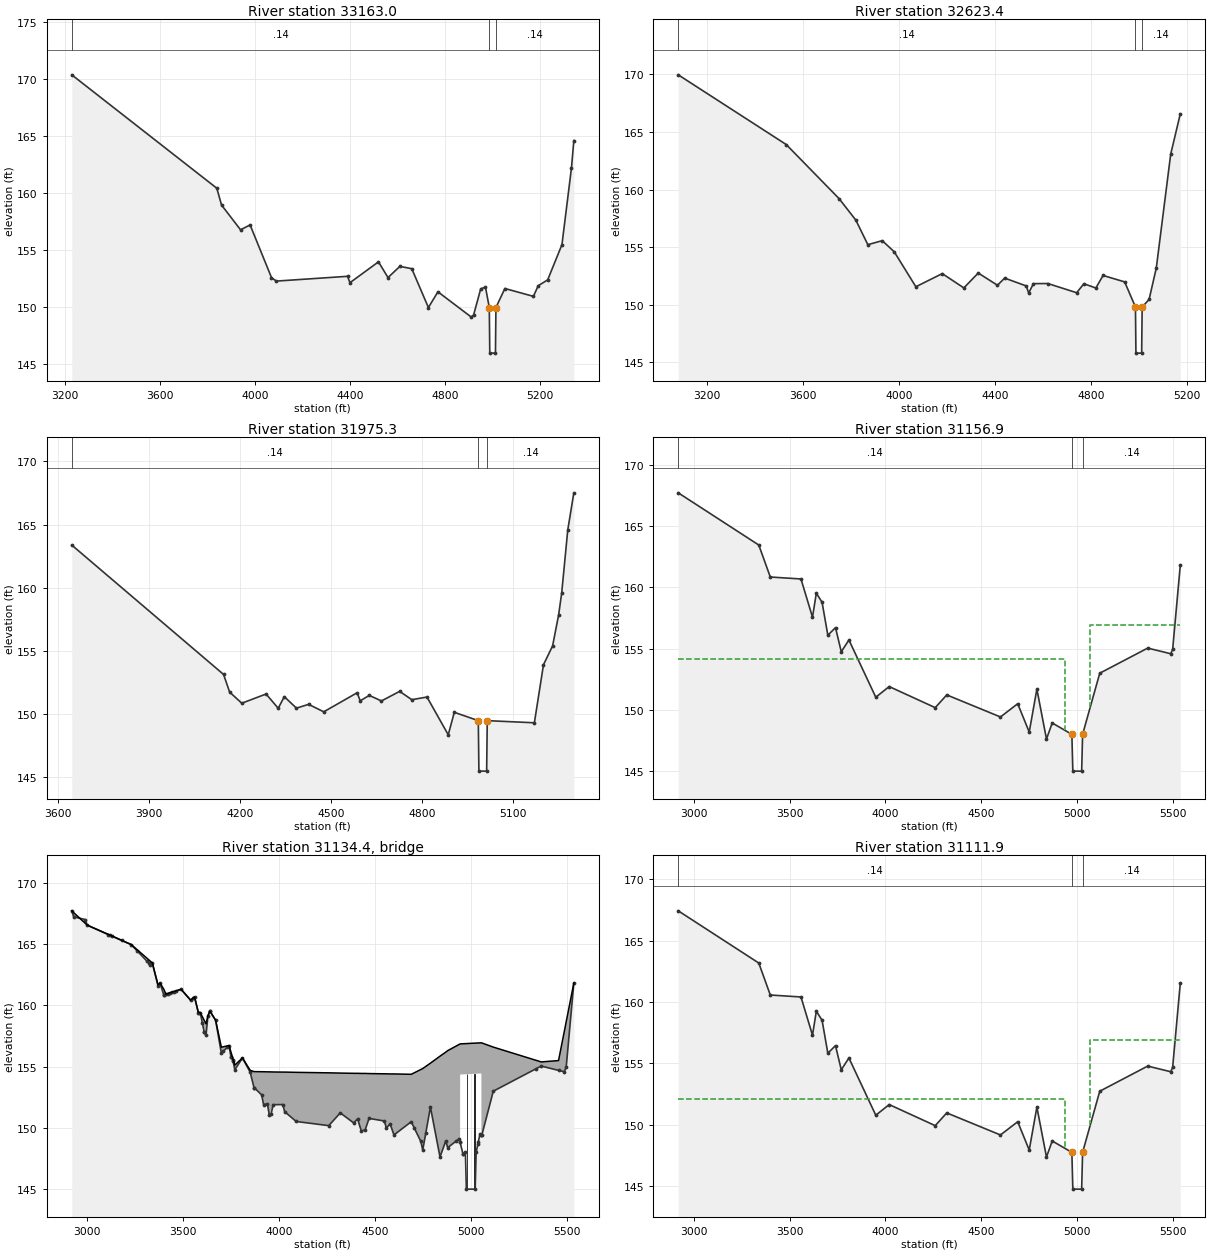
Type RM Length L Ch R = 1 ,33163.0,539.6,539.6,539.6
BEGIN DESCRIPTION:
Pig Basket Creek 65.0
END DESCRIPTION:
#Sta/Elev= 30
    3230  170.35    3840   160.4    3860  158.92    3940  156.75    3980  157.18
    4070  152.56    4090  152.25    4390  152.67    4400  152.11    4520  153.94
    4560  152.56    4610  153.54    4660  153.34    4730  149.93    4770  151.31
    4910   149.1    4920  149.27    4950  151.57    4970  151.72  4986.1  149.93
  4988.1  145.93    5012  145.93    5014  149.93  5051.7   151.6  5171.7  150.91
  5191.7  151.84  5231.7  152.36  5291.7  155.45  5331.7  162.18  5341.7  164.58
#Mann= 3 , 1 , 0
 3230.00    0.14       0  4986.1   0.045       0    5014    0.14       0
Bank Sta=4986.10,5014.00
Exp/Cntr=0.3,0.1

Type RM Length L Ch R = 1 ,32623.4,648.1,648.1,648.1
BEGIN DESCRIPTION:
Pig Basket Creek 64.0
END DESCRIPTION:
#Sta/Elev= 30
  3081.2  169.96  3531.2  163.91  3751.2  159.22  3821.2  157.35  3871.2  155.22
  3931.2  155.57  3981.2   154.6  4071.2  151.57  4181.2  152.71  4271.2  151.47
  4331.2  152.76  4411.2   151.7  4441.2  152.32  4531.2  151.64  4541.2  151.03
  4561.2  151.84  4621.2  151.85  4741.2  151.05  4771.2  151.83  4821.2  151.46
  4851.2  152.55  4941.2  151.99  4986.1  149.81  4988.1  145.81    5012  145.81
    5014  149.81    5043  150.47    5073   153.2    5133  163.08    5173  166.58
#Mann= 3 , 1 , 0
 3081.20    0.14       0  4986.1   0.045       0    5014    0.14       0
Bank Sta=4986.10,5014.00
Exp/Cntr=0.3,0.1

Type RM Length L Ch R = 1 ,31975.3,818.4,818.4,818.4
BEGIN DESCRIPTION:
Pig Basket Creek 63.0
END DESCRIPTION:
#Sta/Elev= 30
  3646.3  163.37  4146.3  153.12  4166.3  151.72  4206.3  150.84  4286.3  151.57
  4326.3  150.44  4346.3  151.36  4386.3  150.45  4426.3  150.75  4476.3  150.16
  4586.3  151.67  4596.3  151.03  4626.3  151.46  4666.3  151.02  4726.3  151.78
  4766.3  151.12  4816.3  151.33  4886.3  148.34  4906.3  150.12  4985.3  149.46
  4987.3  145.46  5012.8  145.46  5014.8  149.46    5170  149.29    5200  153.89
    5230  155.38    5250  157.85    5260  159.58    5280  164.57    5300  167.51
#Mann= 3 , 1 , 0
 3646.30    0.14       0  4985.3   0.045       0  5014.8    0.14       0
Bank Sta=4985.30,5014.80
Exp/Cntr=0.3,0.1

Type RM Length L Ch R = 1 ,31156.9,45,45,45
BEGIN DESCRIPTION:
Upstream Section of Bridge/Culvert/Weir
END DESCRIPTION:
#Sta/Elev= 30
  2919.6  167.72  3339.6  163.46  3399.6  160.85  3559.6  160.69  3619.6  157.57
  3639.6  159.53  3669.6  158.79  3699.6   156.1  3739.6  156.72  3769.6  154.75
  3809.6  155.71  3949.6  151.04  4019.6  151.91  4259.6  150.19  4319.6  151.23
  4599.6  149.43  4689.6  150.51  4749.6   148.2  4789.6   151.7  4839.6  147.63
  4869.6  148.94    4972  148.01    4977  145.01    5023  145.01    5028  148.01
  5117.4     153  5367.4  155.05  5487.4  154.59  5497.4  154.94  5537.4  161.83
#Mann= 3 , 1 , 0
 2919.60    0.14       0    4972   0.045       0    5028    0.14       0
#XS Ineff= 2 , 0
       0    4934  154.18    5066       0  156.92
Bank Sta=4972.00,5028.00
Exp/Cntr=0.5,0.3

Type RM Length L Ch R = 3 ,31134.4,,,
BEGIN DESCRIPTION:
Taylor Store Rd-TOR
Structure ID: Taylors Store Rd-Bridge
Approximate Survey Structure
END DESCRIPTION:
Bridge Culvert--1,0,-1,-1, 0
Deck Dist Width WeirC Skew NumUp NumDn MinLoCord MaxHiCord MaxSubmerge Is_Ogee
10,25,2.6,, 60, 60,,,0.95,0,1,1,,
  2919.6  2929.6  2999.6  3229.6  3339.6  3369.6  3379.6  3399.6  3410.5  3489.6
  3539.6  3559.6  3579.6  3589.6  3619.6  3629.6  3639.6  3669.6  3699.6  3739.6
  3769.6  3809.6  3849.6  3869.6  3909.6  3919.6  3939.6  3949.6  3969.6  4019.6
  4029.6  4089.6  4259.6  4319.6  4389.6  4409.6  4429.6  4449.6  4469.6  4549.6
  4559.6  4579.6  4599.6  4689.6  4749.6  4789.6  4839.6  4869.6  4879.6 4944.41
  4944.5 5055.39  5055.5  5057.4  5117.4  5367.4  5457.6  5487.4  5497.4  5537.4
  167.71  167.56  166.55  164.96  163.46  161.66  161.82  161.31  160.91  161.31
  160.42  160.69  159.41   159.4  158.49  159.15  159.53  158.79  156.58  156.72
  155.12  155.71   154.7  154.59  154.58  154.58  154.57  154.57  154.56  154.55
  154.55  154.53  154.49  154.47  154.45  154.45  154.44  154.44  154.43  154.41
  154.41   154.4   154.4  154.37  154.84  155.28  155.85  156.18   156.3  156.85
  156.85  156.94  156.94  156.93  156.59  155.38  155.49  157.85  158.65  161.82
  167.71  167.22  166.54  164.95  163.45  161.57  161.81  160.84   160.9   161.3
  160.41  160.68   159.4  159.39  157.56  159.14  159.52  158.78  156.09  156.71
  154.74   155.7  154.55  153.29  152.69   151.9  151.96  151.03  151.89   151.9
  151.32  150.52  150.18  151.22   150.4  150.73  149.73  149.84  150.77  150.56
  149.99  150.31  149.42   150.5  148.19  151.69  147.62  148.93  148.38  148.81
  154.35  154.44   149.4  149.39  152.99  155.04  154.69  154.58  154.93  161.82
  2919.6  2929.6  2999.6  3229.6  3339.6  3369.6  3379.6  3399.6  3410.5  3489.6
  3539.6  3559.6  3579.6  3589.6  3619.6  3629.6  3639.6  3669.6  3699.6  3739.6
  3769.6  3809.6  3849.6  3869.6  3909.6  3919.6  3939.6  3949.6  3969.6  4019.6
  4029.6  4089.6  4259.6  4319.6  4389.6  4409.6  4429.6  4449.6  4469.6  4549.6
  4559.6  4579.6  4599.6  4689.6  4749.6  4789.6  4839.6  4869.6  4879.6 4944.41
  4944.5 5055.39  5055.5  5057.4  5117.4  5367.4  5457.6  5487.4  5497.4  5537.4
  167.71  167.56  166.55  164.96  163.46  161.66  161.82  161.31  160.91  161.31
  160.42  160.69  159.41   159.4  158.49  159.15  159.53  158.79  156.58  156.72
  155.12  155.71   154.7  154.59  154.58  154.58  154.57  154.57  154.56  154.55
  154.55  154.53  154.49  154.47  154.45  154.45  154.44  154.44  154.43  154.41
  154.41   154.4   154.4  154.37  154.84  155.28  155.85  156.18   156.3  156.85
  156.85  156.94  156.94  156.93  156.59  155.38  155.49  157.85  158.65  161.82
  167.46  166.97  166.29   164.7   163.2  161.32  161.56  160.59  160.65  161.05
  160.16  160.43  159.15  159.14  157.31  158.89  159.27  158.53  155.84  156.46
  154.49  155.45   154.3  153.04  152.44  151.65  151.71  150.78  151.64  151.65
  151.07  150.27  149.93  150.97  150.15  150.48  149.48  149.59  150.52  150.31
  149.74  150.06  149.17  150.25  147.94  151.44  147.37  148.68  148.13  148.56
   154.1  154.19  149.15  149.14  152.74  154.79  154.44  154.33  154.68  161.57
Pier Skew, UpSta & Num, DnSta & Num=,4980.2, 2 ,4980.2, 2 , 0 , 0 , 0 ,,
       1       1
     144  155.43
       1       1
  143.75  155.18
Pier Skew, UpSta & Num, DnSta & Num=,5019.7, 2 ,5019.7, 2 , 0 , 0 , 0 ,,
       1       1
     144   155.5
       1       1
  143.75  155.25
Abutment Skew #Up #Dn=, 2 , 2
 4944.30 4960.50
  154.35  147.86
 4944.30 4960.50
  154.10  147.61
Abutment Skew #Up #Dn=, 2 , 2
 5039.50 5055.59
  148.87  154.44
 5039.50 5055.59
  148.62  154.19
BR Coef= 1 , 1 , 0 ,1.25, 0 ,,,0.8,0,2,0,
Wspro=,,,, 1 ,,,, 0 ,,,, 0 ,,,,-1 ,-1 ,-1 , 0 , 0 , 0 , 0 , 0
BC Design=,, 0 ,, 0 ,,,,,,
BR U #Sta/Elev= 104
  2919.6  167.71  2929.6  167.22  2989.6     167  2999.6  166.54  3110.5  165.77
  3120.5   165.7  3130.5  165.64  3180.5  165.29  3229.6  164.95  3260.5  164.44
  3310.5  163.62  3320.5  163.45  3329.6   163.3  3339.6  163.45  3369.6  161.57
  3379.6  161.81  3399.6  160.84  3400.5  160.84  3410.5   160.9  3420.5  160.95
  3430.5     161  3440.5  161.05  3450.5   161.1  3460.5  161.15  3489.6   161.3
  3539.6  160.41  3550.5  160.56  3559.6  160.68  3579.6   159.4  3580.5   159.4
  3589.6  159.39  3600.5  158.55  3609.6  157.85  3610.5  157.82  3619.6  157.56
  3629.6  159.14  3639.6  159.52  3640.5   159.5  3669.6  158.78  3699.6  156.09
  3710.5  156.26  3730.5  156.57  3739.6  156.71  3749.6   155.8  3750.5  155.78
  3759.6  155.54  3760.5  155.47  3769.6  154.74  3809.6   155.7  3849.6  154.55
  3869.6  153.29  3870.5  153.28  3909.6  152.69  3919.6   151.9  3939.6  151.96
  3949.6  151.03  3959.6  151.17  3969.6  151.89  4019.6   151.9  4029.6  151.32
  4089.6  150.52  4259.6  150.18  4319.6  151.22  4389.6   150.4  4409.6  150.73
  4429.6  149.73  4449.6  149.84  4469.6  150.77  4549.6  150.56  4559.6  149.99
  4579.6  150.31  4599.6  149.42  4689.6   150.5  4705.3  149.99  4739.6  148.89
  4749.6  148.19  4765.3  149.56  4789.6  151.69  4839.6  147.62  4869.6  148.93
  4879.6  148.38  4925.3  148.94  4939.6  149.12 4944.41  148.81  4944.5  148.81
  4959.6  147.85  4960.5  147.86    4972     148    4977     145    5023     145
    5028     148  5037.6  148.72  5039.5  148.87  5047.4  149.46 5055.39   149.4
  5055.5   149.4  5057.4  149.39  5117.4  152.99  5337.6   154.8  5367.4  155.04
  5457.6  154.69  5487.4  154.58  5497.4  154.93  5537.4  161.82
BR U #Mann= 3
 2919.60    0.14    4972   0.045    5028    0.14
BR U Banks=4972.00,5028.00
BR D #Sta/Elev= 104
  2919.6  167.46  2929.6  166.97  2989.6  166.75  2999.6  166.29  3110.5  165.52
  3120.5  165.45  3130.5  165.39  3180.5  165.04  3229.6   164.7  3260.5  164.19
  3310.5  163.37  3320.5   163.2  3329.6  163.05  3339.6   163.2  3369.6  161.32
  3379.6  161.56  3399.6  160.59  3400.5  160.59  3410.5  160.65  3420.5   160.7
  3430.5  160.75  3440.5   160.8  3450.5  160.85  3460.5   160.9  3489.6  161.05
  3539.6  160.16  3550.5  160.31  3559.6  160.43  3579.6  159.15  3580.5  159.15
  3589.6  159.14  3600.5   158.3  3609.6   157.6  3610.5  157.57  3619.6  157.31
  3629.6  158.89  3639.6  159.27  3640.5  159.25  3669.6  158.53  3699.6  155.84
  3710.5  156.01  3730.5  156.32  3739.6  156.46  3749.6  155.55  3750.5  155.53
  3759.6  155.29  3760.5  155.22  3769.6  154.49  3809.6  155.45  3849.6   154.3
  3869.6  153.04  3870.5  153.03  3909.6  152.44  3919.6  151.65  3939.6  151.71
  3949.6  150.78  3959.6  150.92  3969.6  151.64  4019.6  151.65  4029.6  151.07
  4089.6  150.27  4259.6  149.93  4319.6  150.97  4389.6  150.15  4409.6  150.48
  4429.6  149.48  4449.6  149.59  4469.6  150.52  4549.6  150.31  4559.6  149.74
  4579.6  150.06  4599.6  149.17  4689.6  150.25  4705.3  149.74  4739.6  148.64
  4749.6  147.94  4765.3  149.31  4789.6  151.44  4839.6  147.37  4869.6  148.68
  4879.6  148.13  4925.3  148.69  4939.6  148.87 4944.41  148.56  4944.5  148.56
  4959.6   147.6  4960.5  147.61    4972  147.75    4977  144.75    5023  144.75
    5028  147.75  5037.6  148.47  5039.5  148.62  5047.4  149.21 5055.39  149.15
  5055.5  149.15  5057.4  149.14  5117.4  152.74  5337.6  154.55  5367.4  154.79
  5457.6  154.44  5487.4  154.33  5497.4  154.68  5537.4  161.57
BR D #Mann= 3
 2919.60    0.14    4972   0.045    5028    0.14
BR D Banks=4972.00,5028.00

Type RM Length L Ch R = 1 ,31111.9,493.4,493.4,493.4
BEGIN DESCRIPTION:
Downstream Section of Bridge/Culvert/Weir
END DESCRIPTION:
#Sta/Elev= 30
  2919.6  167.44  3339.6  163.18  3399.6  160.57  3559.6  160.41  3619.6  157.29
  3639.6  159.25  3669.6  158.51  3699.6  155.82  3739.6  156.44  3769.6  154.47
  3809.6  155.43  3949.6  150.76  4019.6  151.63  4259.6  149.91  4319.6  150.95
  4599.6  149.15  4689.6  150.23  4749.6  147.92  4789.6  151.42  4839.6  147.35
  4869.6  148.66    4972  147.73    4977  144.73    5023  144.73    5028  147.73
  5117.4  152.72  5367.4  154.77  5487.4  154.31  5497.4  154.66  5537.4  161.55
#Mann= 3 , 1 , 0
 2919.60    0.14       0    4972   0.045       0    5028    0.14       0
#XS Ineff= 2 , 0
       0    4934  152.12    5066       0  156.92
Bank Sta=4972.00,5028.00
Exp/Cntr=0.5,0.3

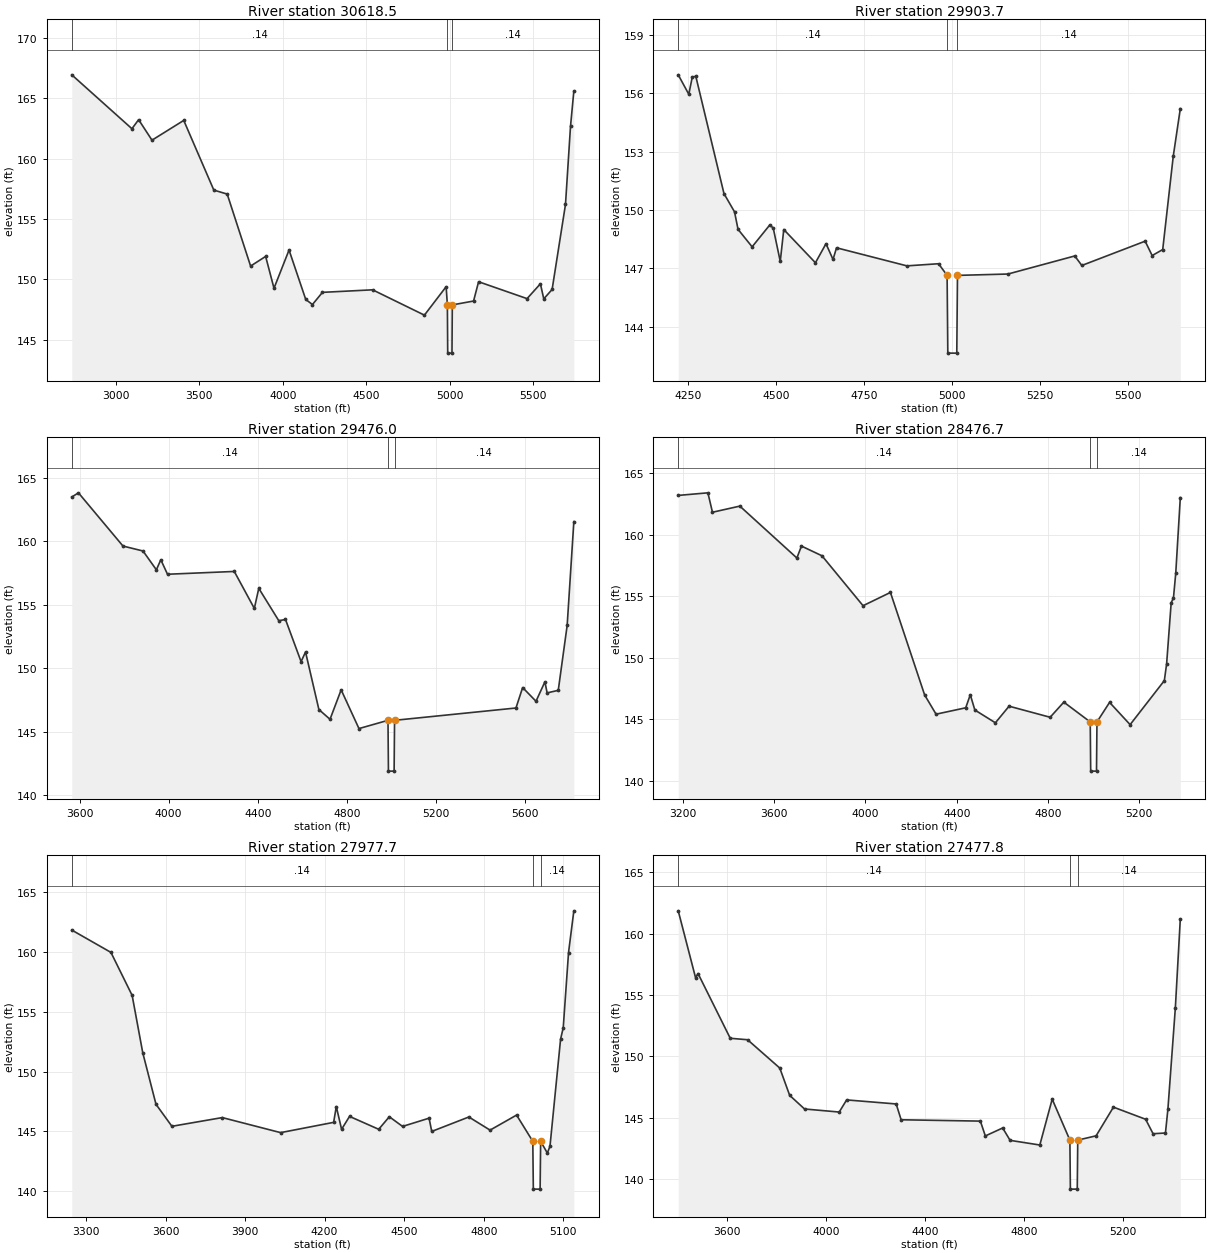
Type RM Length L Ch R = 1 ,30618.5,714.8,714.8,714.8
BEGIN DESCRIPTION:
Pig Basket Creek 60.0
END DESCRIPTION:
#Sta/Elev= 30
  2737.8  166.96  3097.8  162.49  3137.8  163.24  3217.8  161.54  3407.8  163.18
  3587.8   157.4  3667.8  157.07  3807.8   151.1  3897.8   151.9  3947.8  149.26
  4037.8  152.43  4137.8  148.33  4177.8  147.91  4237.8  148.92  4537.8  149.13
  4847.8  147.03  4977.8  149.39  4985.2  147.88  4987.2  143.88  5012.7  143.88
  5014.7  147.88  5141.9   148.2  5171.9   149.8  5461.9   148.4  5541.9  149.63
  5561.9  148.38  5611.9  149.16  5691.9  156.21  5721.9  162.68  5741.9  165.61
#Mann= 3 , 1 , 0
 2737.80    0.14       0  4985.2   0.045       0  5014.7    0.14       0
Bank Sta=4985.20,5014.70
Exp/Cntr=0.3,0.1

Type RM Length L Ch R = 1 ,29903.7,427.7,427.7,427.7
BEGIN DESCRIPTION:
Pig Basket Creek 59.0
END DESCRIPTION:
#Sta/Elev= 30
    4221  156.96    4251  155.96    4261  156.85    4271  156.88    4351  150.85
    4381  149.91    4391  149.01    4431  148.11    4481  149.23    4491  149.08
    4511  147.36    4521     149    4611  147.29    4641  148.27    4661  147.46
    4671  148.06    4871  147.13    4961  147.24  4985.3  146.64  4987.3  142.64
  5012.8  142.64  5014.8  146.64  5158.2  146.71  5348.2  147.64  5368.2  147.15
  5548.2   148.4  5568.2  147.66  5598.2  147.97  5628.2  152.78  5648.2  155.22
#Mann= 3 , 1 , 0
 4221.00    0.14       0  4985.3   0.045       0  5014.8    0.14       0
Bank Sta=4985.30,5014.80
Exp/Cntr=0.3,0.1

Type RM Length L Ch R = 1 ,29476.0,999.3,999.3,999.3
BEGIN DESCRIPTION:
Pig Basket Creek 58.0
END DESCRIPTION:
#Sta/Elev= 30
  3564.8  163.48  3594.8  163.81  3794.8  159.62  3884.8  159.23  3944.8  157.75
  3964.8  158.54  3994.8   157.4  4294.8  157.62  4384.8  154.71  4404.8  156.29
  4494.8  153.74  4524.8  153.84  4594.8  150.52  4614.8  151.28  4674.8  146.75
  4724.8  145.98  4774.8   148.3  4854.8  145.25  4985.2   145.9  4987.2   141.9
  5012.7   141.9  5014.7   145.9    5560  146.87    5590  148.48    5650   147.4
    5690  148.93    5700  148.06    5750  148.26    5790  153.37    5820  161.54
#Mann= 3 , 1 , 0
 3564.80    0.14       0  4985.2   0.045       0  5014.7    0.14       0
Bank Sta=4985.20,5014.70
Exp/Cntr=0.3,0.1

Type RM Length L Ch R = 1 ,28476.7,499,499,499
BEGIN DESCRIPTION:
Pig Basket Creek 56.0
END DESCRIPTION:
#Sta/Elev= 30
  3179.5   163.2  3309.5  163.41  3329.5  161.83  3449.5  162.33  3699.5  158.11
  3719.5  159.08  3809.5  158.29  3989.5  154.23  4109.5  155.31  4259.5  146.97
  4309.5  145.41  4439.5  145.93  4459.5  146.99  4479.5  145.75  4569.5  144.71
  4629.5  146.06  4809.5  145.16  4869.5  146.39  4985.2  144.78  4987.2  140.78
  5012.7  140.78  5014.7  144.78    5070  146.37    5160  144.56    5310  148.14
    5320   149.5    5340  154.47    5350  154.87    5360  156.87    5380  163.02
#Mann= 3 , 1 , 0
 3179.50    0.14       0  4985.2   0.045       0  5014.7    0.14       0
Bank Sta=4985.20,5014.70
Exp/Cntr=0.3,0.1

Type RM Length L Ch R = 1 ,27977.7,499.9,499.9,499.9
BEGIN DESCRIPTION:
Pig Basket Creek 55.0
END DESCRIPTION:
#Sta/Elev= 30
  3246.3  161.85    3394  159.98    3474  156.38    3514  151.58    3564  147.26
    3624  145.42    3814  146.15    4034  144.89    4234  145.75    4244  147.07
    4264  145.17    4294  146.25    4404  145.17    4444  146.22    4494  145.41
    4594   146.1    4604  144.99    4744   146.2    4824   145.1    4924  146.36
  4985.2  144.16  4987.2  140.16  5012.8  140.16  5014.8  144.16    5040  143.18
    5050  143.75    5090  152.72    5100  153.67    5120  159.97    5140  163.46
#Mann= 3 , 1 , 0
 3246.30    0.14       0  4985.2   0.045       0  5014.8    0.14       0
Bank Sta=4985.20,5014.80
Exp/Cntr=0.3,0.1

Type RM Length L Ch R = 1 ,27477.8,1942.3,1942.3,1942.3
BEGIN DESCRIPTION:
Pig Basket Creek 54.0
END DESCRIPTION:
#Sta/Elev= 30
  3402.7  161.87  3472.7  156.41  3482.7  156.75  3612.7  151.47  3682.7  151.35
  3812.7  149.04  3852.7  146.81  3912.7   145.7  4052.7  145.45  4082.7  146.44
  4282.7  146.11  4302.7  144.82  4622.7  144.71  4642.7   143.5  4712.7  144.15
  4742.7  143.14  4862.7  142.76  4912.7   146.5  4984.1  143.16  4986.1  139.16
  5013.9  139.16  5015.9  143.16    5090  143.51    5160  145.85    5290  144.86
    5320  143.68    5370  143.74    5380  145.71    5410  153.96    5430  161.21
#Mann= 3 , 1 , 0
 3402.70    0.14       0  4984.1   0.045       0  5015.9    0.14       0
Bank Sta=4984.10,5015.90
Exp/Cntr=0.3,0.1

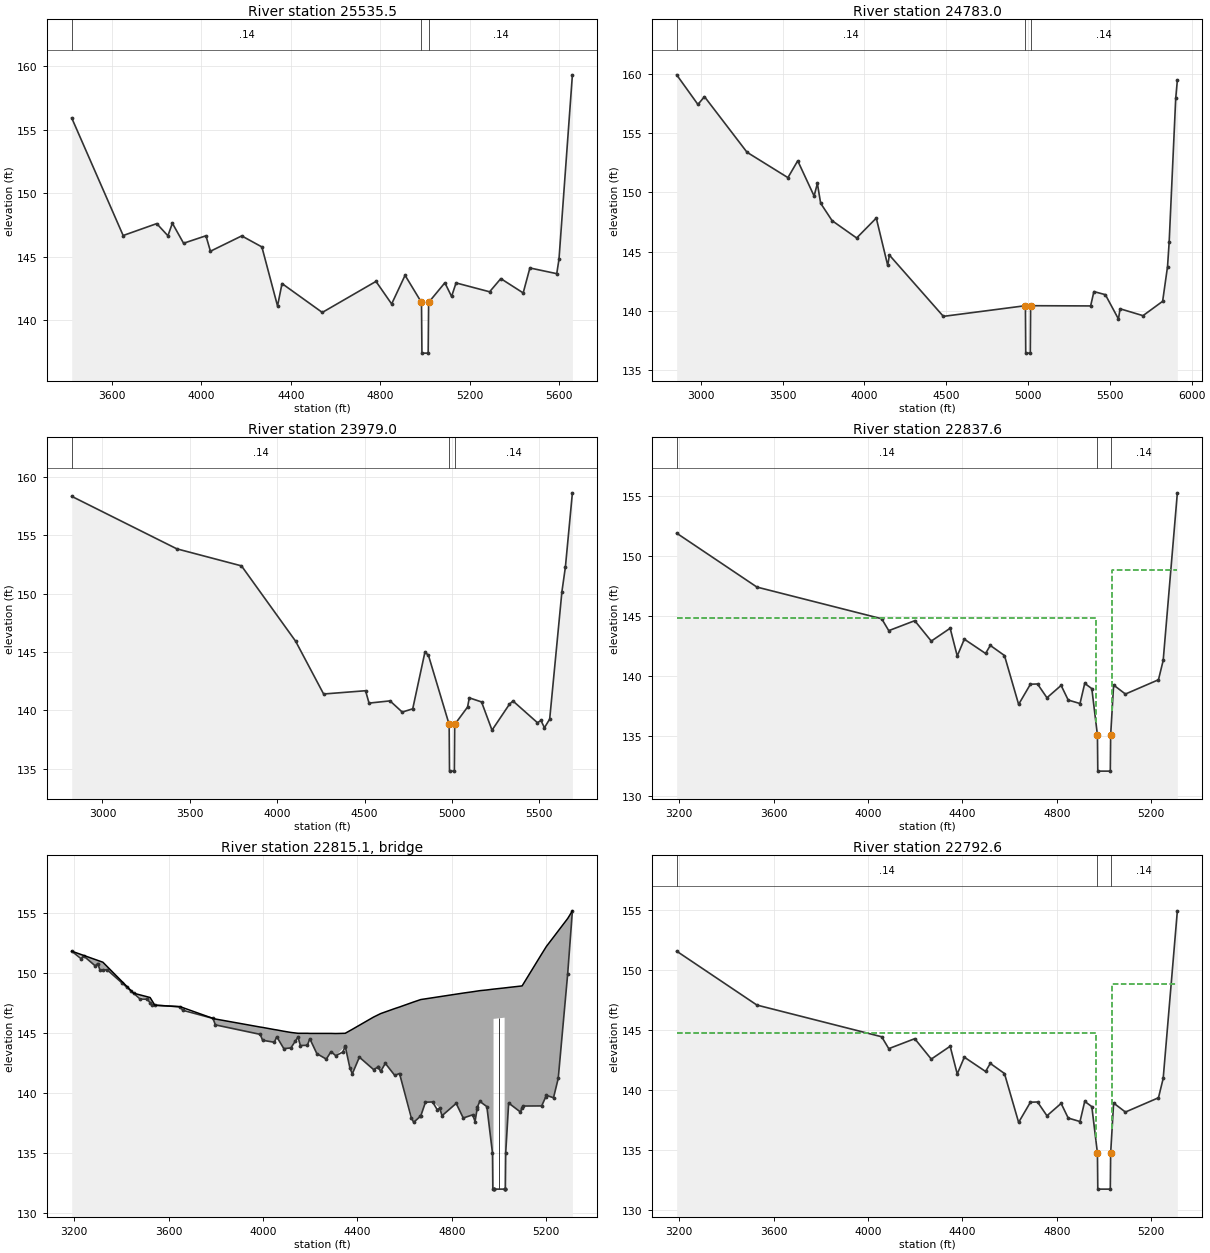
Type RM Length L Ch R = 1 ,25535.5,752.5,752.5,752.5
BEGIN DESCRIPTION:
Pig Basket Creek 50.0
END DESCRIPTION:
#Sta/Elev= 30
  3420.7  155.94  3650.7  146.66  3800.7   147.6  3850.7  146.64  3870.7  147.63
  3920.7  146.05  4020.7  146.64  4040.7  145.42  4180.7  146.63  4270.7  145.76
  4340.7   141.1  4360.7  142.87  4540.7  140.59  4780.7  143.04  4850.7  141.26
  4910.7  143.52  4984.1  141.38  4986.1  137.38    5014  137.38    5016  141.38
  5088.6  142.93  5118.6  141.85  5138.6  142.92  5288.6  142.22  5338.6  143.26
  5438.6  142.13  5468.6   144.1  5588.6  143.65  5598.6  144.78  5658.6  159.34
#Mann= 3 , 1 , 0
 3420.70    0.14       0  4984.1   0.045       0    5016    0.14       0
Bank Sta=4984.10,5016.00
Exp/Cntr=0.3,0.1

Type RM Length L Ch R = 1 ,24783.0,804,804,804
BEGIN DESCRIPTION:
Pig Basket Creek 49.0
END DESCRIPTION:
#Sta/Elev= 30
  2852.7   159.9  2982.7   157.4  3022.7  158.06  3282.7  153.37  3532.7  151.23
  3592.7  152.65  3692.7  149.68  3712.7  150.74  3732.7  149.07  3802.7   147.6
  3952.7  146.14  4072.7  147.82  4142.7  143.82  4152.7   144.7  4482.7  139.53
  4984.1  140.43  4986.1  136.43    5014  136.43    5016  140.43  5382.7  140.41
  5402.7  141.62  5472.7  141.36  5552.7  139.31  5562.7  140.17  5702.7  139.59
  5822.7   140.8  5852.7  143.73  5862.7  145.81  5902.7  157.92  5912.7  159.45
#Mann= 3 , 1 , 0
 2852.70    0.14       0  4984.1   0.045       0    5016    0.14       0
Bank Sta=4984.10,5016.00
Exp/Cntr=0.3,0.1

Type RM Length L Ch R = 1 ,23979.0,1141.4,1141.4,1141.4
BEGIN DESCRIPTION:
Pig Basket Creek 47.0
END DESCRIPTION:
#Sta/Elev= 29
    2824  158.35  3425.6  153.85  3795.6  152.39  4105.6  145.93  4265.6  141.41
  4505.6  141.69  4525.6  140.63  4645.6  140.82  4715.6  139.86  4775.6  140.14
  4845.6  145.01  4865.6  144.72  4984.1   138.8  4986.1   134.8  5013.9   134.8
  5015.9   138.8  5089.4  140.29  5099.4  141.08  5169.4  140.73  5229.4  138.31
  5329.4  140.54  5349.4  140.81  5489.4  138.95  5509.4  139.14  5529.4  138.52
  5559.4  139.26  5629.4  150.18  5649.4   152.3  5689.4  158.65
#Mann= 3 , 1 , 0
 2824.00    0.14       0  4984.1   0.045       0  5015.9    0.14       0
Bank Sta=4984.10,5015.90
Exp/Cntr=0.3,0.1

Type RM Length L Ch R = 1 ,22837.6,45,45,45
BEGIN DESCRIPTION:
Upstream Section of Bridge/Culvert/Weir
END DESCRIPTION:
#Sta/Elev= 30
  3189.8  151.89  3529.8   147.4  4058.2  144.76  4088.2  143.77  4198.2   144.6
  4268.2   142.9  4348.2  143.97  4378.2  141.66  4408.2  143.06  4498.2  141.87
  4518.2  142.54  4578.2   141.7  4638.2  137.63  4688.2  139.31  4718.2  139.33
  4758.2  138.18  4818.2  139.21  4848.2  137.99  4898.2   137.7  4918.2  139.38
  4948.2  138.94    4972  135.07  4973.5  132.07  5026.5  132.07    5028  135.07
  5040.5  139.24  5090.5  138.49  5230.5  139.68  5250.5  141.29  5310.5  155.25
#Mann= 3 , 1 , 0
 3189.80    0.14       0    4972   0.045       0    5028    0.14       0
#XS Ineff= 2 , 0
       0    4966  144.79    5034       0   148.8
Bank Sta=4972.00,5028.00
Exp/Cntr=0.5,0.3

Type RM Length L Ch R = 3 ,22815.1,,,
BEGIN DESCRIPTION:
Womble Rd-TOR
Structure ID: Womble Rd-Bridge
Approximate Survey Structure
END DESCRIPTION:
Bridge Culvert--1,0,-1,-1, 0
Deck Dist Width WeirC Skew NumUp NumDn MinLoCord MaxHiCord MaxSubmerge Is_Ogee
10,25,2.6,, 60, 60,,,0.95,0,1,1,,
  3189.8  3321.9  3451.9  3521.9  3541.9  3649.8  3788.2  3798.2  3988.2  3998.2
  4048.2  4058.2  4088.2  4118.2  4148.2  4158.2  4188.2  4198.2  4228.2  4268.2
  4288.2  4308.2  4348.2  4378.2  4408.2  4468.2  4498.2  4518.2  4558.2  4578.2
  4638.2  4668.2  4688.2  4718.2  4748.2  4758.2  4818.2  4848.2  4888.2  4898.2
  4908.2  4918.2  4948.2    4972  4973.5 4976.41  4976.5 5023.39  5023.5  5026.5
    5028  5040.5  5090.5  5097.6  5180.5  5200.5  5230.5  5250.5  5290.5  5310.5
  151.82   150.9  148.32  147.96  147.32  147.19  146.22  146.17   145.5  145.47
  145.29  145.26  145.15  145.05  144.98  144.98  144.98  144.97  144.97  144.97
  144.97  144.96  144.98  145.31  145.65  146.33  146.62  146.76  147.04  147.17
  147.59  147.79  147.85  147.94  148.03  148.06  148.24  148.33  148.44  148.47
   148.5  148.53  148.59  148.65  148.65  148.66  148.66  148.76  148.76  148.77
  148.77   148.8  148.91  148.93  151.59  152.22  152.99  153.51  154.54  155.18
  151.82  150.25  148.32  147.52  147.32  147.19  146.22  145.68  144.89   144.4
  144.23  144.69   143.7  143.76  144.67  143.96  143.98  144.53  143.28  142.83
  143.45  143.11   143.9  141.59  142.99  141.96   141.8  142.47  141.47  141.63
  137.56  138.09  139.24  139.26  138.76  138.11  139.14  137.92  138.19  137.63
  138.83  139.31  138.87     135     132     132  146.18  146.28     132     132
     135  139.17  138.42  138.78  138.93  139.81  139.61  141.22  149.92  155.18
  3189.8  3321.9  3421.9  3521.9  3541.9  3649.8  3788.2  3798.2  3988.2  3998.2
  4048.2  4058.2  4088.2  4118.2  4148.2  4158.2  4188.2  4198.2  4228.2  4268.2
  4288.2  4308.2  4348.2  4378.2  4408.2  4468.2  4498.2  4518.2  4558.2  4578.2
  4638.2  4668.2  4688.2  4718.2  4748.2  4758.2  4818.2  4848.2  4888.2  4898.2
  4908.2  4918.2  4948.2    4972  4973.5 4976.41  4976.5 5023.39  5023.5  5026.5
    5028  5040.5  5090.5  5097.6  5180.5  5200.5  5230.5  5250.5  5290.5  5310.5
   151.7   150.9  148.73  147.96  147.21  147.08   146.2  146.17   145.5  145.47
  145.29  145.26  145.15  145.05  144.98  144.98  144.98  144.97  144.97  144.97
  144.97  144.96  144.98  145.31  145.65  146.33  146.62  146.76  147.04  147.17
  147.59  147.79  147.85  147.94  148.03  148.06  148.24  148.33  148.44  148.47
   148.5  148.53  148.59  148.65  148.65  148.66  148.66  148.76  148.76  148.77
  148.77   148.8  148.91  148.93  151.59  152.22  152.99  153.51  154.54  155.06
  151.57     150  148.59  147.27  147.07  146.94  145.97  145.43  144.64  144.15
  143.98  144.44  143.45  143.51  144.42  143.71  143.73  144.28  143.03  142.58
   143.2  142.86  143.65  141.34  142.74  141.71  141.55  142.22  141.22  141.38
  137.31  137.84  138.99  139.01  138.51  137.86  138.89  137.67  137.94  137.38
  138.58  139.06  138.62  134.75  131.75  131.75  145.93  146.03  131.75  131.75
  134.75  138.92  138.17  138.53  138.68  139.56  139.36  140.97  149.67  154.93
Pier Skew, UpSta & Num, DnSta & Num=,5000.0, 2 ,5000.0, 2 , 0 , 0 , 0 ,,
       2       2
     131  147.23
       2       2
  130.75  146.98
BR Coef= 1 , 1 , 0 ,1.25, 0 ,,,0.8,0,2,0,
Wspro=,,,, 1 ,,,, 0 ,,,, 0 ,,,,-1 ,-1 ,-1 , 0 , 0 , 0 , 0 , 0
BC Design=,, 0 ,, 0 ,,,,,,
BR U #Sta/Elev= 87
  3189.8  151.82  3229.8  151.19  3239.8  151.43  3289.8  150.59  3299.8  150.79
  3309.8  150.23  3321.9  150.25  3339.8  150.27  3401.9  149.19  3421.9  148.84
  3441.9  148.49  3451.9  148.32  3479.8  147.83  3509.8  147.82  3521.9  147.52
  3529.8  147.33  3541.9  147.32  3649.8  147.19  3659.8   146.9  3788.2  146.22
  3798.2  145.68  3988.2  144.89  3998.2   144.4  4048.2  144.23  4058.2  144.69
  4088.2   143.7  4118.2  143.76  4136.8  144.32  4148.2  144.67  4158.2  143.96
  4188.2  143.98  4198.2  144.53  4228.2  143.28  4268.2  142.83  4288.2  143.45
  4308.2  143.11  4338.2  143.42  4346.8  143.83  4348.2   143.9  4368.2  142.09
  4378.2  141.59  4408.2  142.99  4468.2  141.96  4486.8  142.16  4488.2  142.17
  4498.2   141.8  4518.2  142.47  4558.2  141.47  4578.2  141.63  4628.2  137.95
  4638.2  137.56  4666.8  138.07  4668.2  138.09  4688.2  139.24  4718.2  139.26
  4738.2  138.61  4748.2  138.76  4758.2  138.11  4818.2  139.14  4848.2  137.92
  4888.2  138.19  4898.2  137.63  4906.8  138.66  4908.2  138.83  4918.2  139.31
  4948.2  138.87    4972     135  4973.5     132 4976.41     132  4976.5     132
  4976.6     132  5023.3     132 5023.39     132  5023.5     132  5026.5     132
    5028     135  5040.5  139.17  5090.5  138.42  5097.6  138.78  5100.5  138.92
  5180.5  138.93  5197.6  139.68  5200.5  139.81  5230.5  139.61  5250.5  141.22
  5290.5  149.92  5310.5  155.18
BR U #Mann= 3
 3189.80    0.14    4972   0.045    5028    0.14
BR U Banks=4972.00,5028.00
BR D #Sta/Elev= 87
  3189.8  151.57  3229.8  150.94  3239.8  151.18  3289.8  150.34  3299.8  150.54
  3309.8  149.98  3321.9     150  3339.8  150.02  3401.9  148.94  3421.9  148.59
  3441.9  148.24  3451.9  148.07  3479.8  147.58  3509.8  147.57  3521.9  147.27
  3529.8  147.08  3541.9  147.07  3649.8  146.94  3659.8  146.65  3788.2  145.97
  3798.2  145.43  3988.2  144.64  3998.2  144.15  4048.2  143.98  4058.2  144.44
  4088.2  143.45  4118.2  143.51  4136.8  144.07  4148.2  144.42  4158.2  143.71
  4188.2  143.73  4198.2  144.28  4228.2  143.03  4268.2  142.58  4288.2   143.2
  4308.2  142.86  4338.2  143.17  4346.8  143.58  4348.2  143.65  4368.2  141.84
  4378.2  141.34  4408.2  142.74  4468.2  141.71  4486.8  141.91  4488.2  141.92
  4498.2  141.55  4518.2  142.22  4558.2  141.22  4578.2  141.38  4628.2   137.7
  4638.2  137.31  4666.8  137.82  4668.2  137.84  4688.2  138.99  4718.2  139.01
  4738.2  138.36  4748.2  138.51  4758.2  137.86  4818.2  138.89  4848.2  137.67
  4888.2  137.94  4898.2  137.38  4906.8  138.41  4908.2  138.58  4918.2  139.06
  4948.2  138.62    4972  134.75  4973.5  131.75 4976.41  131.75  4976.5  131.75
  4976.6  131.75  5023.3  131.75 5023.39  131.75  5023.5  131.75  5026.5  131.75
    5028  134.75  5040.5  138.92  5090.5  138.17  5097.6  138.53  5100.5  138.67
  5180.5  138.68  5197.6  139.43  5200.5  139.56  5230.5  139.36  5250.5  140.97
  5290.5  149.67  5310.5  154.93
BR D #Mann= 3
 3189.80    0.14    4972   0.045    5028    0.14
BR D Banks=4972.00,5028.00

Type RM Length L Ch R = 1 ,22792.6,305.5,305.5,305.5
BEGIN DESCRIPTION:
Downstream Section of Bridge/Culvert/Weir
END DESCRIPTION:
#Sta/Elev= 30
  3189.8  151.57  3529.8  147.08  4058.2  144.44  4088.2  143.45  4198.2  144.28
  4268.2  142.58  4348.2  143.65  4378.2  141.34  4408.2  142.74  4498.2  141.55
  4518.2  142.22  4578.2  141.38  4638.2  137.31  4688.2  138.99  4718.2  139.01
  4758.2  137.86  4818.2  138.89  4848.2  137.67  4898.2  137.38  4918.2  139.06
  4948.2  138.62    4972  134.75  4973.5  131.75  5026.5  131.75    5028  134.75
  5040.5  138.92  5090.5  138.17  5230.5  139.36  5250.5  140.97  5310.5  154.93
#Mann= 3 , 1 , 0
 3189.80    0.14       0    4972   0.045       0    5028    0.14       0
#XS Ineff= 2 , 0
       0    4966  144.79    5034       0   148.8
Bank Sta=4972.00,5028.00
Exp/Cntr=0.5,0.3

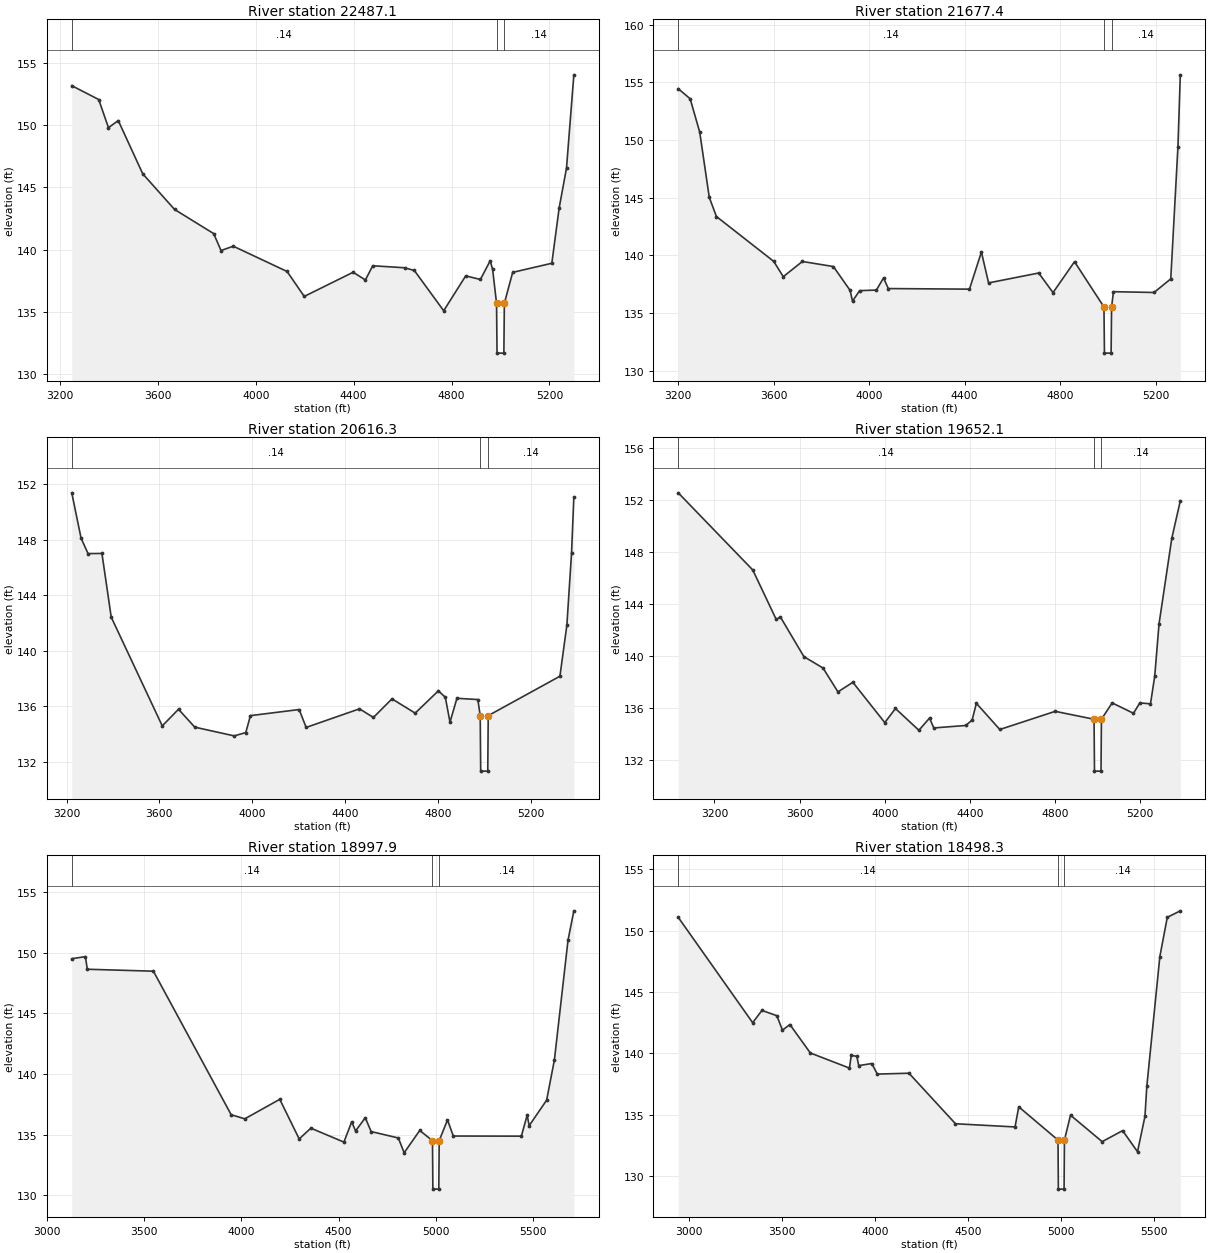
Type RM Length L Ch R = 1 ,22487.1,809.7,809.7,809.7
BEGIN DESCRIPTION:
Pig Basket Creek 44.0
END DESCRIPTION:
#Sta/Elev= 30
  3248.1  153.15  3358.1  152.04  3398.1  149.78  3438.1  150.35  3538.1  146.08
  3668.1  143.22  3828.1  141.28  3858.1  139.92  3908.1  140.27  4128.1  138.24
  4198.1  136.24  4398.1  138.18  4448.1  137.56  4478.1   138.7  4608.1  138.54
  4648.1  138.32  4768.1  135.09  4858.1  137.89  4918.1   137.6  4958.1   139.1
  4968.1  138.41  4984.1  135.69  4986.1  131.69    5014  131.69    5016  135.69
    5050  138.17    5210   138.9    5240  143.34    5270  146.54    5300  154.02
#Mann= 3 , 1 , 0
 3248.10    0.14       0  4984.1   0.045       0    5016    0.14       0
Bank Sta=4984.10,5016.00
Exp/Cntr=0.3,0.1

Type RM Length L Ch R = 1 ,21677.4,1061.1,1061.1,1061.1
BEGIN DESCRIPTION:
Pig Basket Creek 42.0
END DESCRIPTION:
#Sta/Elev= 30
  3200.6  154.46  3250.6  153.58  3290.6  150.69  3330.6  145.03  3360.6  143.37
  3600.6  139.48  3640.6  138.15  3720.6  139.47  3850.6  139.03  3920.6  136.96
  3930.6  136.03  3960.6  136.94  4030.6  136.99  4060.6  138.04  4080.6  137.12
  4420.6  137.07  4470.6  140.29  4500.6  137.61  4710.6  138.47  4770.6  136.77
  4860.6  139.45    4984  135.52    4986  131.52  5013.9  131.52  5015.9  135.52
  5023.8  136.85  5193.8  136.78  5263.8  137.96  5293.8  149.39  5303.8  155.66
#Mann= 3 , 1 , 0
 3200.60    0.14       0    4984   0.045       0  5015.9    0.14       0
Bank Sta=4984.00,5015.90
Exp/Cntr=0.3,0.1

Type RM Length L Ch R = 1 ,20616.3,964.2,964.2,964.2
BEGIN DESCRIPTION:
Pig Basket Creek 40.0
END DESCRIPTION:
#Sta/Elev= 30
  3222.4  151.37  3262.4  148.11  3292.4  146.99  3352.4     147  3392.4  142.41
  3612.4  134.57  3682.4  135.77  3752.4  134.48  3922.4  133.85  3972.4  134.09
  3992.4  135.31  4202.4  135.75  4232.4  134.46  4462.4   135.8  4522.4  135.18
  4602.4  136.52  4702.4  135.49  4802.4   137.1  4832.4  136.63  4852.4  134.84
  4882.4  136.56  4972.4  136.47  4982.7  135.31  4984.7  131.31  5015.2  131.31
  5017.2  135.31  5326.2  138.15  5356.2  141.84  5376.2  147.01  5386.2  151.05
#Mann= 3 , 1 , 0
 3222.40    0.14       0  4982.7   0.045       0  5017.2    0.14       0
Bank Sta=4982.70,5017.20
Exp/Cntr=0.3,0.1

Type RM Length L Ch R = 1 ,19652.1,654.2,654.2,654.2
BEGIN DESCRIPTION:
Pig Basket Creek 38.0
END DESCRIPTION:
#Sta/Elev= 30
  3030.1  152.57  3380.1  146.62  3490.1  142.81  3510.1  142.99  3620.1  139.94
  3710.1  139.06  3780.1  137.22  3850.1  137.96  4000.1  134.85  4050.1  135.94
  4160.1  134.26  4210.1   135.2  4230.1  134.44  4380.1  134.63  4410.1  135.05
  4430.1  136.34  4540.1  134.32  4800.1  135.72  4982.7  135.11  4984.7  131.11
  5015.3  131.11  5017.3  135.11  5067.7  136.37  5167.7  135.57  5197.7  136.37
  5247.7   136.3  5267.7  138.45  5287.7  142.45  5347.7  149.06  5387.7  151.96
#Mann= 3 , 1 , 0
 3030.10    0.14       0  4982.7   0.045       0  5017.3    0.14       0
Bank Sta=4982.70,5017.30
Exp/Cntr=0.3,0.1

Type RM Length L Ch R = 1 ,18997.9,499.6,499.6,499.6
BEGIN DESCRIPTION:
Pig Basket Creek 37.0
END DESCRIPTION:
#Sta/Elev= 30
  3127.1  149.52  3197.1  149.69  3207.1  148.65  3547.1  148.49  3947.1  136.65
  4017.1  136.31  4197.1  137.92  4297.1  134.65  4357.1  135.54  4527.1  134.39
  4567.1  136.06  4587.1  135.31  4637.1   136.4  4667.1  135.26  4807.1  134.73
  4837.1  133.51  4917.1  135.35  4982.8  134.51  4984.8  130.51  5015.3  130.51
  5017.3  134.51    5060  136.22    5090  134.89    5440  134.88    5470  136.62
    5480  135.74    5570  137.85    5610  141.17    5680  151.04    5710  153.47
#Mann= 3 , 1 , 0
 3127.10    0.14       0  4982.8   0.045       0  5017.3    0.14       0
Bank Sta=4982.80,5017.30
Exp/Cntr=0.3,0.1

Type RM Length L Ch R = 1 ,18498.3,498.3,498.3,498.3
BEGIN DESCRIPTION:
Pig Basket Creek 36.0
END DESCRIPTION:
#Sta/Elev= 30
  2941.8  151.08  3341.8  142.49  3391.8  143.49  3471.8  143.06  3501.8  141.88
  3541.8  142.34  3651.8  140.02  3861.8  138.79  3871.8  139.83  3901.8  139.74
  3911.8  138.99  3981.8  139.16  4011.8   138.3  4181.8  138.37  4431.8  134.25
  4751.8  133.99  4771.8  135.63  4982.7  132.92  4984.7  128.92  5015.3  128.92
  5017.3  132.92    5050  134.95    5220  132.79    5330  133.69    5410  131.97
    5450  134.85    5460   137.3    5530  147.88    5570  151.08    5640  151.61
#Mann= 3 , 1 , 0
 2941.80    0.14       0  4982.7   0.045       0  5017.3    0.14       0
Bank Sta=4982.70,5017.30
Exp/Cntr=0.3,0.1