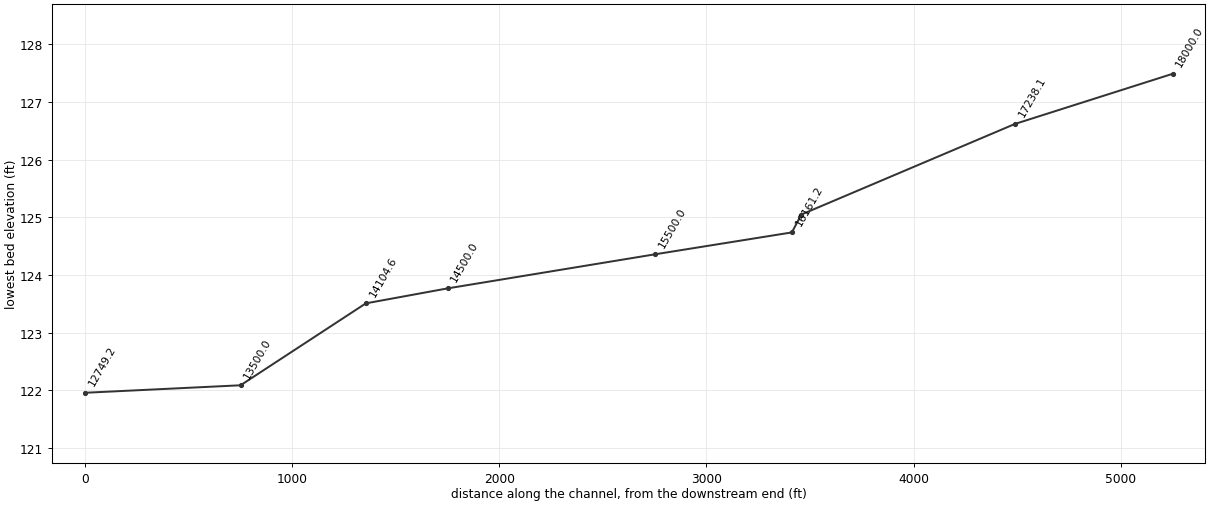
HEC-RAS study 020515_pig_basket_creek.prj: Pig Basket Creek-changed

--- 020515_pig_basket_creek.g01 (geometry) --- (continued)

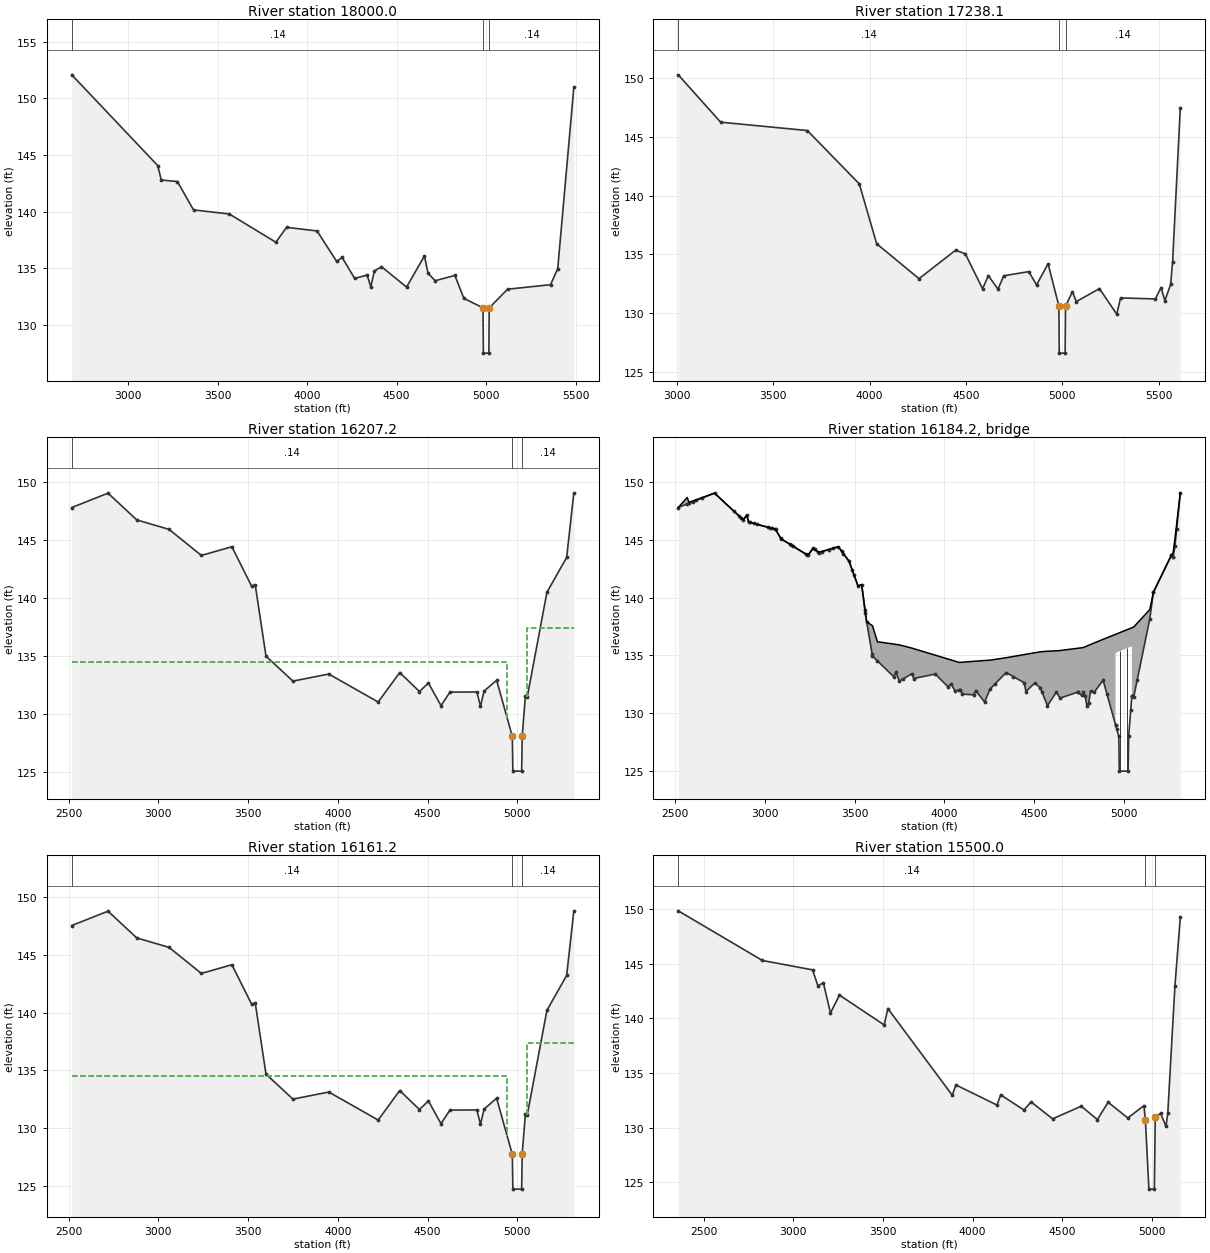
Type RM Length L Ch R = 1 ,18000.0,761.9,761.9,761.9
BEGIN DESCRIPTION:
Pig Basket Creek 35.0
END DESCRIPTION:
#Sta/Elev= 30
  2685.6  152.09  3165.6  144.07  3185.6  142.79  3275.6  142.66  3365.6  140.15
  3565.6  139.79  3825.6  137.29  3885.6  138.61  4055.6  138.29  4165.6  135.59
  4195.6  135.95  4265.6  134.09  4335.6  134.39  4355.6  133.34  4375.6  134.74
  4415.6  135.13  4555.6  133.33  4655.6  136.08  4675.6  134.55  4715.6  133.89
  4825.6  134.36  4875.6  132.33  4982.7  131.49  4984.7  127.49  5015.3  127.49
  5017.3  131.49    5120  133.14    5360  133.54    5400  134.96    5490  150.98
#Mann= 3 , 1 , 0
 2685.60    0.14       0  4982.7   0.045       0  5017.3    0.14       0
Bank Sta=4982.70,5017.30
Exp/Cntr=0.3,0.1

Type RM Length L Ch R = 1 ,17238.1,1030.9,1030.9,1030.9
BEGIN DESCRIPTION:
Pig Basket Creek 33.0
END DESCRIPTION:
#Sta/Elev= 30
  3006.7  150.25  3226.7  146.23  3676.7  145.52  3946.7  140.99  4036.7  135.91
  4256.7  132.94  4446.7  135.36  4496.7  135.05  4586.7  132.09  4616.7   133.2
  4666.7  132.05  4696.7  133.19  4826.7  133.54  4866.7  132.41  4926.7  134.21
  4982.7  130.62  4984.7  126.62  5015.2  126.62  5017.2  130.62  5053.1  131.82
  5073.1  130.99  5193.1   132.1  5283.1  129.93  5303.1  131.31  5483.1  131.22
  5513.1  132.18  5533.1  131.08  5563.1  132.46  5573.1  134.39  5613.1  147.45
#Mann= 3 , 1 , 0
 3006.70    0.14       0  4982.7   0.045       0  5017.2    0.14       0
Bank Sta=4982.70,5017.20
Exp/Cntr=0.3,0.1

Type RM Length L Ch R = 1 ,16207.2,46,46,46
BEGIN DESCRIPTION:
Upstream Section of Bridge/Culvert/Weir
END DESCRIPTION:
#Sta/Elev= 30
  2517.9  147.83    2720  149.07    2880  146.76    3060  145.94    3240  143.69
    3410  144.44    3520  141.03    3540  141.16    3600  134.99    3750  132.83
    3950  133.44  4225.1  131.02  4345.1  133.57  4455.1  131.93  4505.1  132.67
  4575.1  130.71  4625.1  131.88  4775.1  131.89  4795.1  130.65  4815.1  131.97
  4885.1   132.9  4972.5  128.05  4975.5  125.05  5024.5  125.05  5027.5  128.05
  5045.3  131.56  5055.3  131.42  5165.3   140.5  5275.3  143.52  5315.3   149.1
#Mann= 3 , 1 , 0
 2517.90    0.14       0  4972.5   0.045       0  5027.5    0.14       0
#XS Ineff= 2 , 0
       0    4944  134.48    5056       0  137.41
Bank Sta=4972.50,5027.50
Exp/Cntr=0.5,0.3

Type RM Length L Ch R = 3 ,16184.2,,,
BEGIN DESCRIPTION:
Exum Rd-TOR
Structure ID: Exum Rd-Bridge
Approximate Survey Structure
END DESCRIPTION:
Bridge Culvert--1,0,-1,-1, 0
Deck Dist Width WeirC Skew NumUp NumDn MinLoCord MaxHiCord MaxSubmerge Is_Ogee
10,26,2.6,, 60, 60,,,0.95,0,1,1,,
  2517.9  2567.9  2577.9    2720    2880    2900    2910    3060    3090    3240
    3270    3300    3410    3470    3520    3540  3567.9    3600  3627.9    3720
    3730    3750    3820    3830    3950    4020    4040    4060  4084.6    4100
  4165.1  4175.1  4225.1  4255.1  4345.1  4445.1  4455.1  4505.1  4535.1  4575.1
  4625.1  4645.1  4775.1  4785.1  4795.1  4805.1  4815.1  4835.1  4885.1 4954.41
  4954.5 5045.39  5045.5  5055.3  5145.3  5165.3  5265.3  5275.2  5285.3  5315.3
  147.78  148.65  148.22  149.03  146.72  147.13  146.53   145.9  145.09  143.65
  144.27   143.9   144.4  143.13  140.99  141.12  137.91  137.56  136.18  135.98
  135.95  135.91  135.63  135.58  135.02  134.69   134.6   134.5  134.39  134.41
  134.49   134.5  134.56  134.59   134.8  135.07   135.1  135.23  135.31  135.36
   135.4  135.42  135.68  135.75  135.81  135.88  135.94  136.07  136.39  136.82
  136.82  137.39  137.39  137.45  138.96  140.46  143.66  143.87  145.07  149.05
  147.78  148.09  148.15  149.02  146.71  147.12  146.52  145.89  145.08  143.64
  144.26  143.89  144.39  143.12  140.98  141.11   137.9  134.94  134.52  133.14
  133.54  132.78  133.42     133  133.39   132.3   132.5  131.91  132.02  131.66
  131.59  131.96  130.97  132.09  133.52  132.64  131.88  132.62  132.19  130.66
  131.83  131.31  131.84   131.5   130.6  130.92  131.92  131.81  132.85     129
  135.22  135.79  131.51  131.37  138.17  140.45  143.65  143.47  144.42  149.05
  2517.9  2567.9  2577.9    2720    2880    2900    2910    3060    3090    3240
    3270    3300    3410    3470    3520    3540  3567.9    3600  3627.9    3720
    3730    3750    3820    3830    3950    4020    4040    4060  4084.6    4100
  4165.1  4175.1  4225.1  4255.1  4345.1  4445.1  4455.1  4505.1  4535.1  4575.1
  4625.1  4645.1  4775.1  4785.1  4795.1  4805.1  4815.1  4835.1  4885.1 4954.41
  4954.5 5045.39  5045.5  5055.3  5145.3  5165.3  5265.3  5275.2  5285.3  5315.3
  147.78  148.65  148.22  149.03  146.72  147.13  146.53   145.9  145.09  143.65
  144.27   143.9   144.4  143.13  140.99  141.12  137.91  137.56  136.18  135.98
  135.95  135.91  135.63  135.58  135.02  134.69   134.6   134.5  134.39  134.41
  134.49   134.5  134.56  134.59   134.8  135.07   135.1  135.23  135.31  135.36
   135.4  135.42  135.68  135.75  135.81  135.88  135.94  136.07  136.39  136.82
  136.82  137.39  137.39  137.45  138.96  140.46  143.66  143.87  145.07  149.05
  147.53  147.84   147.9  148.77  146.46  146.87  146.27  145.64  144.83  143.39
  144.01  143.64  144.14  142.87  140.73  140.86  137.65  134.69  134.27  132.89
  133.29  132.53  133.17  132.75  133.14  132.05  132.25  131.66  131.77  131.41
  131.34  131.71  130.72  131.84  133.27  132.39  131.63  132.37  131.94  130.41
  131.58  131.06  131.59  131.25  130.35  130.67  131.67  131.56   132.6  128.75
  134.97  135.54  131.26  131.12  137.92   140.2   143.4  143.22  144.17   148.8
Pier Skew, UpSta & Num, DnSta & Num=,4980.5, 2 ,4980.5, 2 , 0 , 0 , 0 ,,
       1       1
     124  136.38
       1       1
  123.75  136.13
Pier Skew, UpSta & Num, DnSta & Num=,5019.5, 2 ,5019.5, 2 , 0 , 0 , 0 ,,
       1       1
     124  136.63
       1       1
  123.75  136.38
Abutment Skew #Up #Dn=, 2 , 2
 4954.30 4961.00
  135.22  128.64
 4954.30 4961.00
  134.97  128.39
Abutment Skew #Up #Dn=, 2 , 2
 5039.00 5045.59
  130.27  135.79
 5039.00 5045.59
  130.02  135.54
BR Coef= 1 , 1 , 0 ,1.25, 0 ,,,0.8,0,2,0,
Wspro=,,,, 1 ,,,, 0 ,,,, 0 ,,,,-1 ,-1 ,-1 , 0 , 0 , 0 , 0 , 0
BC Design=,, 0 ,, 0 ,,,,,,
BR U #Sta/Elev= 111
  2517.9  147.78  2567.9  148.09  2577.9  148.15  2597.9  148.27  2617.9  148.39
  2647.9  148.58    2720  149.02  2827.9  147.46  2857.9  147.03  2867.9  146.88
    2880  146.71    2900  147.12    2910  146.52  2917.9  146.49  2937.9   146.4
  2957.9  146.32  3017.9  146.07  3027.9  146.02  3037.9  145.98  3057.9   145.9
    3060  145.89  3087.9  145.14    3090  145.08  3137.9  144.62  3147.9  144.52
  3157.9  144.43  3227.9  143.76  3237.9  143.66    3240  143.64    3270  144.26
  3277.9  144.16  3297.9  143.92    3300  143.89  3317.9  143.97  3357.9  144.15
  3377.9  144.24    3410  144.39  3427.9  144.01  3437.9   143.8    3470  143.12
  3487.9  142.35  3497.9  141.93    3520  140.98    3540  141.11  3557.9  138.89
    3560  138.63  3567.9   137.9  3597.9  135.13    3600  134.94  3627.9  134.52
    3720  133.14    3730  133.54    3750  132.78  3767.9  132.94    3820  133.42
    3830     133    3950  133.39    4020   132.3    4040   132.5    4060  131.91
  4084.6  132.02    4090  132.05    4100  131.66  4165.1  131.59  4175.1  131.96
  4225.1  130.97  4255.1  132.09  4284.6  132.56  4345.1  133.52  4385.1  133.17
  4445.1  132.64  4455.1  131.88  4505.1  132.62  4535.1  132.19  4544.6  131.83
  4575.1  130.66  4625.1  131.83  4645.1  131.31  4745.1  131.83  4746.8  131.81
  4765.1  131.55  4775.1  131.84  4785.1   131.5  4795.1   130.6  4805.1  130.92
  4815.1  131.92  4835.1  131.81  4885.1  132.85  4906.8  131.65 4954.41     129
  4954.5     129    4961  128.64  4972.5     128  4975.5     125  5024.5     125
  5027.5     128    5039  130.27  5045.3  131.51 5045.39  131.51  5045.5  131.51
  5055.3  131.37  5075.3  132.88  5145.3  138.17  5165.2  140.44  5165.3  140.45
  5265.3  143.65  5275.2  143.47  5275.3  143.47  5285.3  144.42  5295.3  145.96
  5315.3  149.05
BR U #Mann= 3
 2517.90    0.14  4972.5   0.045  5027.5    0.14
BR U Banks=4972.50,5027.50
BR D #Sta/Elev= 111
  2517.9  147.53  2567.9  147.84  2577.9   147.9  2597.9  148.02  2617.9  148.14
  2647.9  148.33    2720  148.77  2827.9  147.21  2857.9  146.78  2867.9  146.63
    2880  146.46    2900  146.87    2910  146.27  2917.9  146.24  2937.9  146.15
  2957.9  146.07  3017.9  145.82  3027.9  145.77  3037.9  145.73  3057.9  145.65
    3060  145.64  3087.9  144.89    3090  144.83  3137.9  144.37  3147.9  144.27
  3157.9  144.18  3227.9  143.51  3237.9  143.41    3240  143.39    3270  144.01
  3277.9  143.91  3297.9  143.67    3300  143.64  3317.9  143.72  3357.9   143.9
  3377.9  143.99    3410  144.14  3427.9  143.76  3437.9  143.55    3470  142.87
  3487.9   142.1  3497.9  141.68    3520  140.73    3540  140.86  3557.9  138.64
    3560  138.38  3567.9  137.65  3597.9  134.88    3600  134.69  3627.9  134.27
    3720  132.89    3730  133.29    3750  132.53  3767.9  132.69    3820  133.17
    3830  132.75    3950  133.14    4020  132.05    4040  132.25    4060  131.66
  4084.6  131.77    4090   131.8    4100  131.41  4165.1  131.34  4175.1  131.71
  4225.1  130.72  4255.1  131.84  4284.6  132.31  4345.1  133.27  4385.1  132.92
  4445.1  132.39  4455.1  131.63  4505.1  132.37  4535.1  131.94  4544.6  131.58
  4575.1  130.41  4625.1  131.58  4645.1  131.06  4745.1  131.58  4746.8  131.56
  4765.1   131.3  4775.1  131.59  4785.1  131.25  4795.1  130.35  4805.1  130.67
  4815.1  131.67  4835.1  131.56  4885.1   132.6  4906.8   131.4 4954.41  128.75
  4954.5  128.75    4961  128.39  4972.5  127.75  4975.5  124.75  5024.5  124.75
  5027.5  127.75    5039  130.02  5045.3  131.26 5045.39  131.26  5045.5  131.26
  5055.3  131.12  5075.3  132.63  5145.3  137.92  5165.2  140.19  5165.3   140.2
  5265.3   143.4  5275.2  143.22  5275.3  143.22  5285.3  144.17  5295.3  145.71
  5315.3   148.8
BR D #Mann= 3
 2517.90    0.14  4972.5   0.045  5027.5    0.14
BR D Banks=4972.50,5027.50

Type RM Length L Ch R = 1 ,16161.2,661.2,661.2,661.2
BEGIN DESCRIPTION:
Downstream Section of Bridge/Culvert/Weir
END DESCRIPTION:
#Sta/Elev= 30
  2517.9  147.52    2720  148.76    2880  146.45    3060  145.63    3240  143.38
    3410  144.13    3520  140.72    3540  140.85    3600  134.68    3750  132.52
    3950  133.13  4225.1  130.71  4345.1  133.26  4455.1  131.62  4505.1  132.36
  4575.1   130.4  4625.1  131.57  4775.1  131.58  4795.1  130.34  4815.1  131.66
  4885.1  132.59  4972.5  127.74  4975.5  124.74  5024.5  124.74  5027.5  127.74
  5045.3  131.25  5055.3  131.11  5165.3  140.19  5275.3  143.21  5315.3  148.79
#Mann= 3 , 1 , 0
 2517.90    0.14       0  4972.5   0.045       0  5027.5    0.14       0
#XS Ineff= 2 , 0
       0    4944  134.48    5056       0  137.41
Bank Sta=4972.50,5027.50
Exp/Cntr=0.5,0.3

Type RM Length L Ch R = 1 ,15500.0,1000,1000,1000
BEGIN DESCRIPTION:
Pig Basket Creek 30.0
END DESCRIPTION:
#Sta/Elev= 30
    2357  149.86    2827  145.31    3107  144.45    3137  142.98    3167  143.28
    3207   140.5    3257  142.14    3507   139.4    3527  140.91    3887  132.96
    3907  133.91    4137  132.06    4157     133    4287  131.61    4327  132.35
    4447   130.8    4607  131.96    4697  130.73    4757  132.32    4867  130.88
    4957  132.01    4965   130.7  4984.7  124.36  5015.2  124.36    5020  130.94
    5050   131.3    5080  130.11    5090  131.29    5130     143    5160  149.25
#Mann= 3 , 1 , 0
 2357.00    0.14       0    4965   0.045       0    5020    0.14       0
Bank Sta=4965.00,5020.00
Exp/Cntr=0.3,0.1

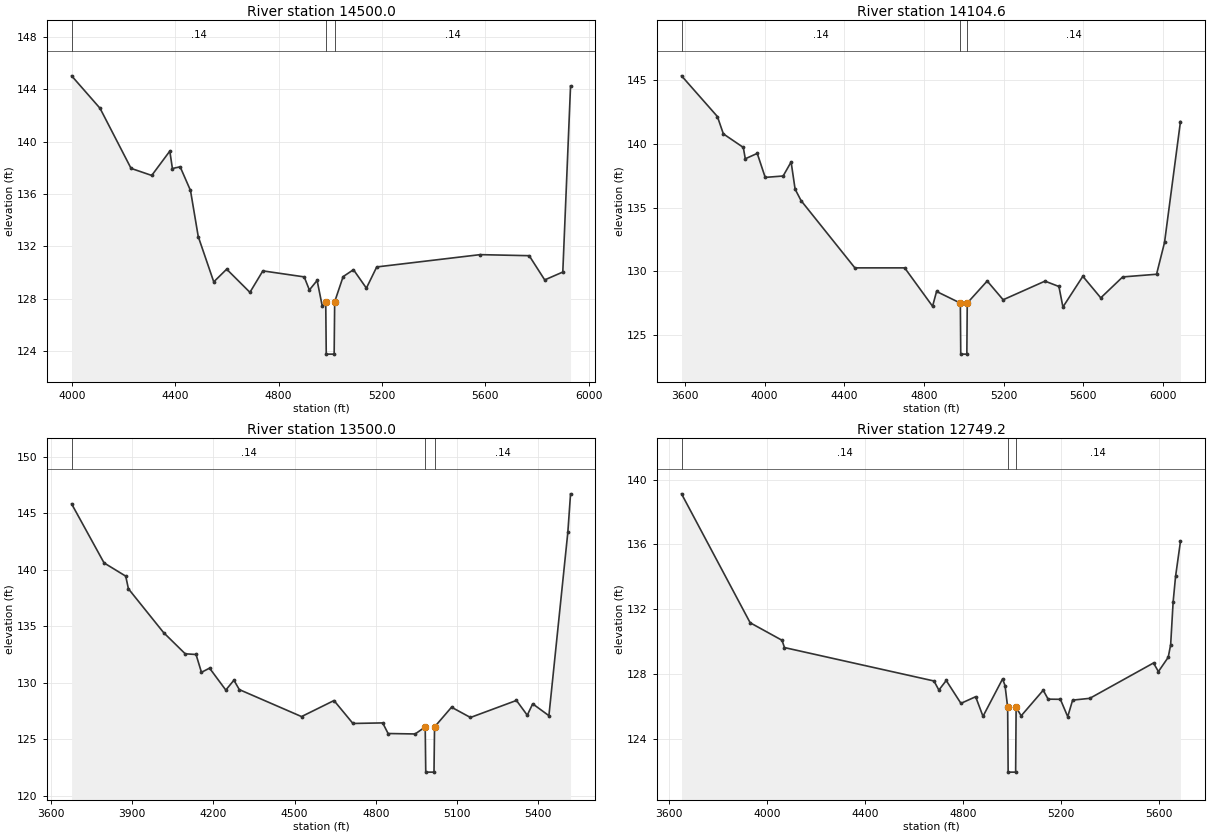
Type RM Length L Ch R = 1 ,14500.0,395.4,395.4,395.4
BEGIN DESCRIPTION:
Pig Basket Creek 28.0
END DESCRIPTION:
#Sta/Elev= 30
  3999.4  145.03  4109.4  142.55  4229.4  137.96  4309.4  137.42  4379.4  139.28
  4389.4  137.95  4419.4  138.08  4459.4  136.27  4489.4  132.75  4549.4  129.29
  4599.4  130.26  4689.4  128.49  4739.4  130.13  4899.4  129.67  4919.4  128.67
  4949.4   129.4  4969.4  127.42  4982.7  127.77  4984.7  123.77  5015.3  123.77
  5017.3  127.77    5050  129.69    5090  130.22    5140  128.81    5180  130.43
    5580  131.37    5770  131.29    5830  129.44    5900  130.04    5930  144.26
#Mann= 3 , 1 , 0
 3999.40    0.14       0  4982.7   0.045       0  5017.3    0.14       0
Bank Sta=4982.70,5017.30
Exp/Cntr=0.3,0.1

Type RM Length L Ch R = 1 ,14104.6,604.6,604.6,604.6
BEGIN DESCRIPTION:
Pig Basket Creek 27.0
END DESCRIPTION:
#Sta/Elev= 30
  3583.3  145.32  3763.3  142.13  3793.3  140.77  3893.3  139.71  3903.3  138.82
  3963.3  139.24  4003.3  137.36  4093.3  137.47  4133.3  138.57  4153.3  136.44
  4183.3  135.54  4453.3  130.27  4703.3  130.27  4843.3  127.26  4863.3  128.42
  4982.7  127.51  4984.7  123.51  5015.3  123.51  5017.3  127.51  5117.5  129.24
  5197.5  127.77  5407.5  129.23  5477.5  128.81  5497.5   127.2  5597.5  129.61
  5687.5  127.92  5797.5  129.56  5967.5  129.77  6007.5  132.26  6087.5  141.74
#Mann= 3 , 1 , 0
 3583.30    0.14       0  4982.7   0.045       0  5017.3    0.14       0
Bank Sta=4982.70,5017.30
Exp/Cntr=0.3,0.1

Type RM Length L Ch R = 1 ,13500.0,750.8,750.8,750.8
BEGIN DESCRIPTION:
Pig Basket Creek 26.0
END DESCRIPTION:
#Sta/Elev= 30
  3675.5  145.85  3795.5  140.62  3875.5  139.45  3885.5  138.33  4015.5  134.45
  4095.5  132.57  4135.5  132.51  4155.5  130.93  4185.5   131.3  4245.5  129.36
  4275.5  130.23  4295.5   129.4  4525.5  127.01  4645.5  128.43  4715.5   126.4
  4825.5  126.45  4845.5  125.51  4945.5  125.47  4982.7  126.09  4984.7  122.09
  5015.2  122.09  5017.2  126.09    5080  127.84    5150  126.93    5320  128.44
    5360  127.13    5380  128.14    5440  127.09    5510  143.34    5520  146.74
#Mann= 3 , 1 , 0
 3675.50    0.14       0  4982.7   0.045       0  5017.2    0.14       0
Bank Sta=4982.70,5017.20
Exp/Cntr=0.3,0.1

Type RM Length L Ch R = 1 ,12749.2,663.8,663.8,663.8
BEGIN DESCRIPTION:
Pig Basket Creek 25.0
END DESCRIPTION:
#Sta/Elev= 30
  3652.1  139.12  3932.1  131.17  4062.1  130.09  4072.1  129.64  4682.1  127.58
  4702.1  127.02  4732.1  127.61  4792.1   126.2  4852.1  126.61  4882.1   125.4
  4962.1  127.71  4972.1  127.29  4982.7  125.96  4984.7  121.96  5015.3  121.96
  5017.3  125.96  5037.8  125.43  5127.8  127.01  5147.8  126.46  5197.8  126.45
  5227.8  125.38  5247.8   126.4  5317.8  126.51  5577.8  128.69  5597.8  128.16
  5637.8  129.04  5647.8  129.82  5657.8  132.44  5667.8  134.03  5687.8  136.19
#Mann= 3 , 1 , 0
 3652.10    0.14       0  4982.7   0.045       0  5017.3    0.14       0
Bank Sta=4982.70,5017.30
Exp/Cntr=0.3,0.1