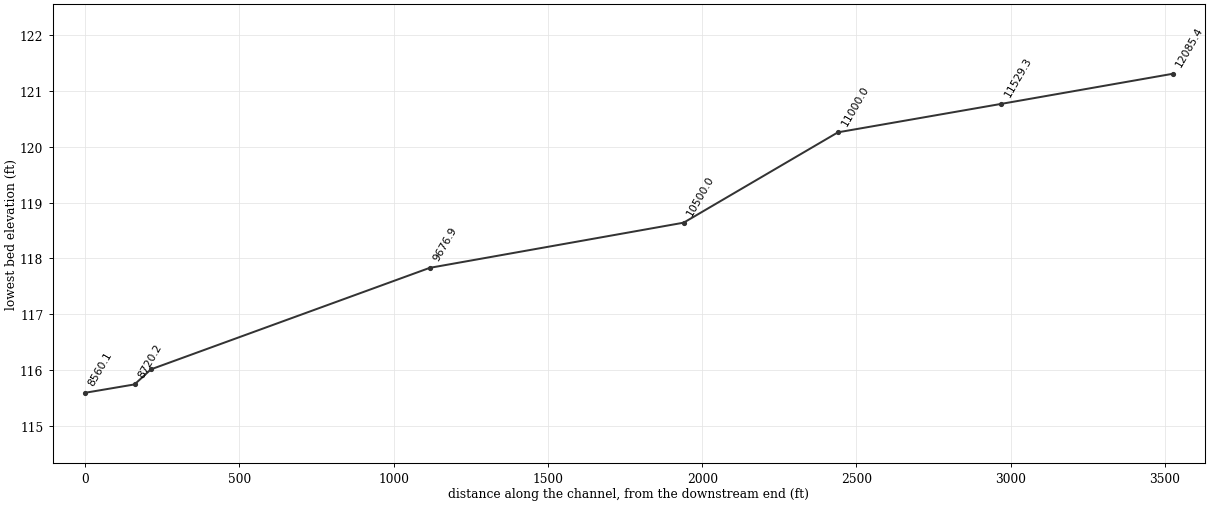
HEC-RAS study 020515_pig_basket_creek.prj: Pig Basket Creek-changed

--- 020515_pig_basket_creek.g01 (geometry) --- (continued)

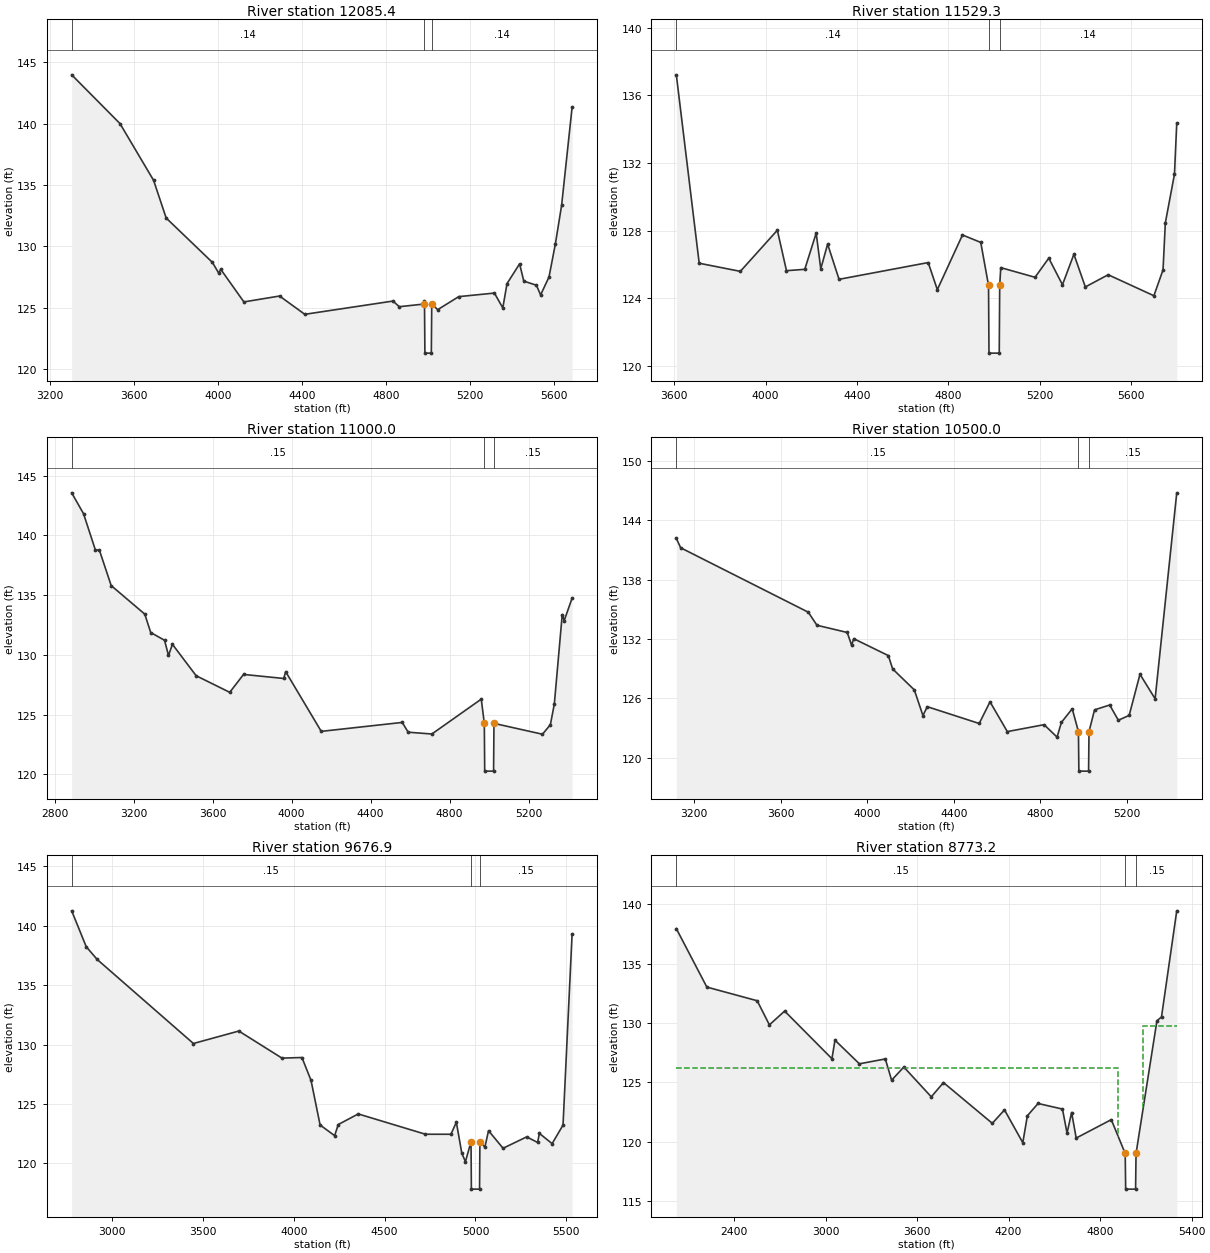
Type RM Length L Ch R = 1 ,12085.4,556.1,556.1,556.1
BEGIN DESCRIPTION:
Pig Basket Creek 24.0
END DESCRIPTION:
#Sta/Elev= 30
  3302.7  143.97  3532.7     140  3692.7  135.38  3752.7  132.31  3972.7   128.7
  4002.7  127.83  4012.7  128.13  4122.7  125.48  4292.7  125.96  4412.7  124.47
  4832.7  125.55  4862.7  125.09  4982.6  125.31  4982.7  125.53  4984.7  121.31
  5015.3  121.31  5017.3  125.31  5045.7  124.85  5145.7  125.91  5315.7   126.2
  5355.7  124.99  5375.7  126.97  5435.7  128.58  5455.7  127.17  5515.7  126.84
  5535.7  126.05  5575.7  127.51  5605.7  130.17  5635.7  133.34  5685.7  141.33
#Mann= 3 , 1 , 0
 3302.70    0.14       0  4982.6   0.045       0  5017.3    0.14       0
Bank Sta=4982.60,5017.30
Exp/Cntr=0.3,0.1

Type RM Length L Ch R = 1 ,11529.3,529.3,529.3,529.3
BEGIN DESCRIPTION:
Pig Basket Creek 22.0
END DESCRIPTION:
#Sta/Elev= 30
  3609.6  137.21  3709.6  126.08  3889.6   125.6  4051.5  128.03  4091.5  125.64
  4171.5  125.72  4221.5  127.86  4241.5  125.75  4271.5  127.21  4321.5  125.13
  4711.5  126.12  4751.5  124.52  4861.5  127.75  4941.5  127.31  4975.5  124.77
  4977.5  120.77  5022.4  120.77  5024.4  124.77    5029  125.82    5179  125.25
    5239  126.38    5299  124.81    5349  126.61    5399  124.68    5499   125.4
    5699  124.16    5739  125.69    5749  128.46    5789  131.34    5799  134.36
#Mann= 3 , 1 , 0
 3609.60    0.14       0  4975.5   0.045       0  5024.4    0.14       0
Bank Sta=4975.50,5024.40
Exp/Cntr=0.3,0.1

Type RM Length L Ch R = 1 ,11000.0,500,500,500
BEGIN DESCRIPTION:
Pig Basket Creek 21.0
END DESCRIPTION:
#Sta/Elev= 30
    2887  143.57    2947  141.82    3007  138.78    3027  138.78    3087   135.8
    3257  133.41    3287  131.87    3357  131.22    3377  129.95    3397  130.88
    3517  128.25    3687  126.86    3757  128.36  3960.2  128.02  3970.2  128.59
  4150.2  123.59  4560.2  124.34  4590.2  123.52  4710.2  123.37  4960.2  126.29
  4975.6  124.26  4977.6  120.26  5022.5  120.26  5024.5  124.26    5270  123.35
    5310  124.15    5330  125.88    5370  133.37    5380  132.87    5420  134.75
#Mann= 3 , 1 , 0
 2887.00    0.15       0  4975.6   0.045       0  5024.5    0.15       0
Bank Sta=4975.60,5024.50
Exp/Cntr=0.3,0.1

Type RM Length L Ch R = 1 ,10500.0,823.1,823.1,823.1
BEGIN DESCRIPTION:
Pig Basket Creek 20.0
END DESCRIPTION:
#Sta/Elev= 30
  3116.8  142.19  3136.8  141.24  3726.8  134.72  3766.8   133.4  3906.8  132.67
  3926.8  131.39  3936.8  132.04  4096.8  130.33  4116.8  128.98  4216.8  126.86
  4256.8  124.26  4276.8  125.16  4516.8  123.46  4566.8  125.65  4646.8  122.64
  4816.8  123.34  4876.8  122.08  4896.8  123.57  4946.8  124.95  4975.5  122.64
  4977.5  118.64  5022.4  118.64  5024.4  122.64    5050  124.84    5120  125.33
    5160  123.79    5210  124.28    5260  128.44    5330  125.96    5430   146.8
#Mann= 3 , 1 , 0
 3116.80    0.15       0  4975.5   0.045       0  5024.4    0.15       0
Bank Sta=4975.50,5024.40
Exp/Cntr=0.3,0.1

Type RM Length L Ch R = 1 ,9676.9,903.7,903.7,903.7
BEGIN DESCRIPTION:
Pig Basket Creek 18.0
END DESCRIPTION:
#Sta/Elev= 30
  2777.6  141.26  2857.6  138.24  2917.6  137.17  3447.6  130.09  3697.6  131.14
  3934.9  128.86  4044.9  128.91  4094.9  126.99  4144.9  123.23  4224.9  122.33
  4244.9  123.27  4354.9  124.16  4724.9  122.45  4864.9  122.45  4894.9  123.46
  4924.9  120.85  4944.9  120.14  4975.6  121.83  4977.6  117.83  5022.5  117.83
  5024.5  121.83    5052  121.37    5072  122.75    5152  121.27    5282  122.23
    5342  121.76    5352  122.52    5422  121.66    5482  123.22    5532  139.32
#Mann= 3 , 1 , 0
 2777.60    0.15       0  4975.6   0.045       0  5024.5    0.15       0
Bank Sta=4975.60,5024.50
Exp/Cntr=0.3,0.1

Type RM Length L Ch R = 1 ,8773.2,53,53,53
BEGIN DESCRIPTION:
Upstream Section of Bridge/Culvert/Weir
END DESCRIPTION:
#Sta/Elev= 30
    2022  137.94    2222  133.02    2552  131.87    2632  129.84    2732     131
    3042  126.99    3062  128.55    3222  126.56    3392  126.97  3433.2  125.18
  3513.2  126.29  3693.2  123.78  3773.2  124.98  4093.2  121.55  4173.2  122.68
  4293.2  119.92  4323.2  122.19  4393.2  123.22  4553.2  122.75  4583.2  120.73
  4613.2  122.46  4643.2  120.31  4873.2  121.86  4964.5  119.01  4967.5  116.01
  5032.5  116.01  5035.5  119.01  5172.4  130.18  5202.4  130.51  5302.4  139.44
#Mann= 3 , 1 , 0
 2022.00    0.15       0  4964.5   0.045       0  5035.5    0.15       0
#XS Ineff= 2 , 0
       0    4919  126.19    5082       0  129.77
Bank Sta=4964.50,5035.50
Exp/Cntr=0.5,0.3

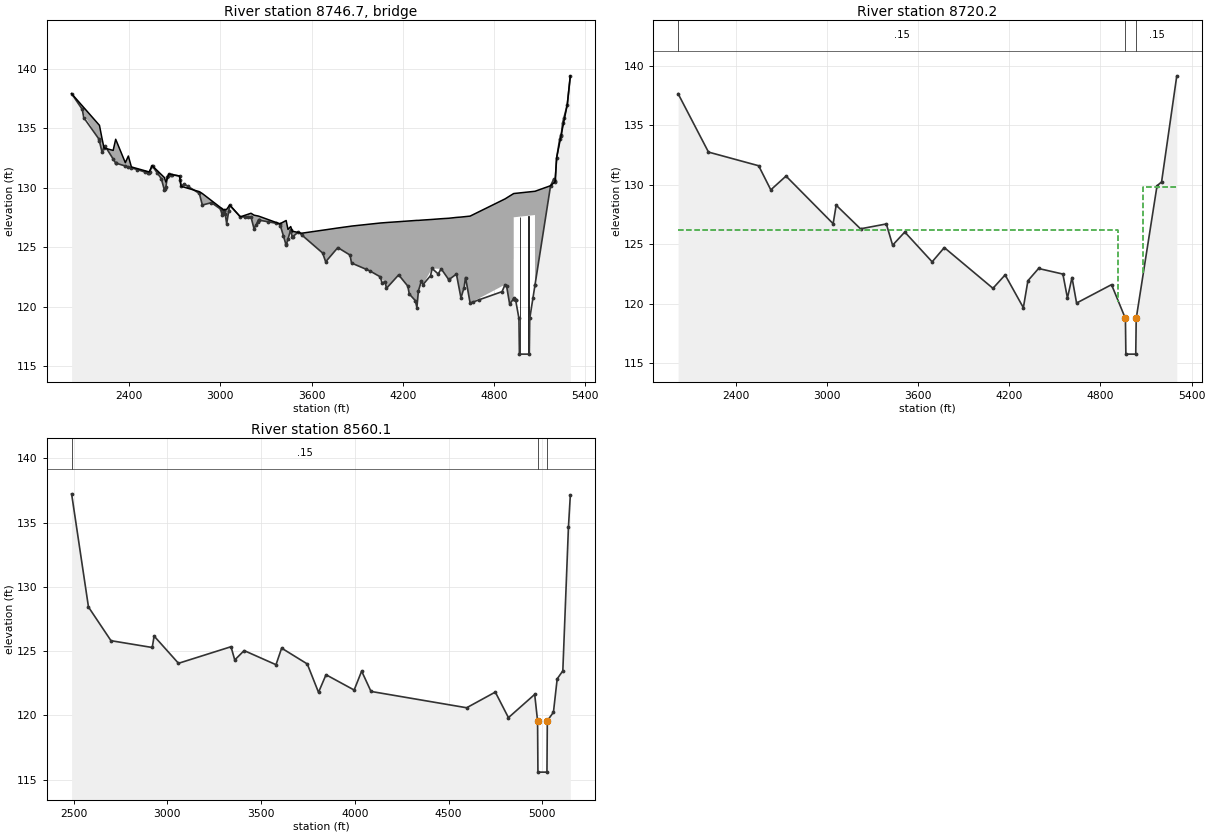
Type RM Length L Ch R = 3 ,8746.7,,,
BEGIN DESCRIPTION:
Red Oak Rd-TOR
Structure ID: Red Oak Rd-Bridge
Approximate Survey Structure
END DESCRIPTION:
Bridge Culvert--1,0,-1,-1, 0
Deck Dist Width WeirC Skew NumUp NumDn MinLoCord MaxHiCord MaxSubmerge Is_Ogee
10,33,2.6,, 60, 60,,,0.95,0,1,1,,
    2022  2205.3    2222  2235.3  2295.3    2312  2375.3  2395.3  2415.3    2532
    2552    2632    2642    2662    2732    2742    2862    2882    3022    3042
    3062    3132    3202    3222    3252    3392  3433.2  3445.3  3463.2  3473.2
  3535.3  3693.2  3773.2  3853.2  3863.2  4053.2  4093.2  4173.2  4293.2  4303.2
  4323.2  4333.2  4393.2  4453.2  4503.2  4553.2  4583.2  4613.2  4643.2  4873.2
  4903.2 4929.91    4930 5069.89    5070  5172.4  5202.4  5212.4  5282.4  5302.4
  137.93  135.26  134.16  133.36  133.15  134.09  132.12  132.68  131.76  131.34
  131.87  130.87  130.49  131.16     131  130.13  129.68  129.52  128.14  128.19
  128.55  127.56  127.86   127.7  127.62  126.97  127.25   126.5  126.74  126.35
  126.18  126.47  126.62  126.76  126.78  127.04  127.08  127.15  127.26  127.26
  127.28  127.29  127.34   127.4  127.44  127.51  127.54  127.58  127.62  129.07
  129.31  129.52  129.52  129.71  129.71  130.18  130.51  132.53  137.01  139.43
  137.93  133.92  133.01  133.35  132.42  132.08  131.84  131.76  131.68  131.23
  131.86  129.83  130.06  131.15  130.99  130.12  129.53  128.55  128.13  126.98
  128.54  127.55  127.54  126.55  127.29  126.96  125.17  125.69  126.46  125.85
  126.04  123.77  124.97  124.34  123.67   122.5  121.54  122.67  119.91  121.32
  122.18  121.85  123.21  123.18  122.26  122.74  120.72  122.45   120.3  121.85
  120.22  120.66  127.52  127.71  121.81  130.17   130.5  132.52     137  139.43
    2022  2205.3    2222  2235.3  2295.3    2312  2375.3  2395.3  2415.3    2532
    2552    2632    2642    2662    2732    2742    2862    2882    3022    3042
    3062    3132    3202    3222    3252    3392  3433.2  3445.3  3463.2  3473.2
  3535.3  3693.2  3773.2  3853.2  3863.2  4053.2  4093.2  4173.2  4293.2  4303.2
  4323.2  4333.2  4393.2  4453.2  4503.2  4553.2  4583.2  4613.2  4643.2  4873.2
  4903.2 4929.91    4930 5069.89    5070  5172.4  5202.4  5212.4  5282.4  5302.4
  137.93  135.26  134.16  133.36  133.15  134.09  132.12  132.68  131.76  131.34
  131.87  130.87  130.49  131.16     131  130.13  129.68  129.52  128.14  128.19
  128.55  127.56  127.86   127.7  127.62  126.97  127.25   126.5  126.74  126.35
  126.18  126.47  126.62  126.76  126.78  127.04  127.08  127.15  127.26  127.26
  127.28  127.29  127.34   127.4  127.44  127.51  127.54  127.58  127.62  129.07
  129.31  129.52  129.52  129.71  129.71  130.18  130.51  132.53  137.01  139.43
  137.68  133.67  132.76   133.1  132.17  131.83  131.59  131.51  131.43  130.98
  131.61  129.58  129.81   130.9  130.74  129.87  129.28   128.3  127.88  126.73
  128.29   127.3  127.29   126.3  127.04  126.71  124.92  125.44  126.21   125.6
  125.79  123.52  124.72  124.09  123.42  122.25  121.29  122.42  119.66  121.07
  121.93   121.6  122.96  122.93  122.01  122.49  120.47   122.2  120.05   121.6
  119.97  120.41  127.27  127.46  121.56  129.92  130.25  132.27  136.75  139.18
Pier Skew, UpSta & Num, DnSta & Num=,4971.5, 2 ,4971.5, 2 , 0 , 0 , 0 ,,
       3       3
     115  128.59
       3       3
  114.75  128.34
Pier Skew, UpSta & Num, DnSta & Num=,5028.5, 2 ,5028.5, 2 , 0 , 0 , 0 ,,
       3       3
     115  128.66
       3       3
  114.75  128.41
Abutment Skew #Up #Dn=, 2 , 2
 4929.80 4943.00
  127.52  120.52
 4929.80 4943.00
  127.27  120.27
Abutment Skew #Up #Dn=, 2 , 2
 5057.00 5070.09
  120.75  127.71
 5057.00 5070.09
  120.50  127.46
BR Coef= 1 , 1 , 0 ,1.25, 0 ,,,0.8,0,2,0,
Wspro=,,,, 1 ,,,, 0 ,,,, 0 ,,,,-1 ,-1 ,-1 , 0 , 0 , 0 , 0 , 0
BC Design=,, 0 ,, 0 ,,,,,,
BR U #Sta/Elev= 132
    2022  137.93    2092  136.61    2102  135.91    2202   134.1  2205.3  133.92
    2222  133.01  2235.3  133.35    2242  133.52  2295.3  132.42    2312  132.08
  2315.3  132.07  2375.3  131.84  2395.3  131.76  2415.3  131.68  2455.3  131.53
  2505.3  131.33  2525.3  131.26    2532  131.23  2535.3  131.33    2552  131.86
  2555.3   131.8  2585.3  131.26    2612  130.77    2632  129.83  2635.3  129.91
    2642  130.06    2652  130.91  2655.3  130.99    2662  131.15  2675.3  131.12
  2685.3   131.1    2732  130.99  2735.3   130.7    2742  130.12    2762  130.33
  2785.3  130.14    2862  129.53    2882  128.55    2942  128.75    3002  128.21
    3012   127.7  3015.3  127.84    3022  128.13  3025.3  128.03    3032  127.83
    3042  126.98  3055.3  128.02    3062  128.54    3132  127.55  3165.3  127.55
  3185.3  127.54    3202  127.54    3222  126.55  3235.3  126.88  3245.3  127.12
    3252  127.29  3255.3  127.28  3315.3  127.14  3365.3  127.02    3392  126.96
  3395.3  126.82  3415.3  125.95  3433.2  125.17  3435.3  125.26  3445.3  125.69
  3463.2  126.46  3465.3  126.33  3473.2  125.85  3475.3  125.87  3513.2  126.28
  3535.3  126.04  3673.2  124.51  3693.2  123.77  3773.2  124.97  3853.2  124.34
  3863.2  123.67  3961.2  123.13  3983.2  123.01  4053.2   122.5  4063.2  121.99
  4083.2  122.11  4093.2  121.54  4173.2  122.67  4233.2  121.73  4243.2  121.06
  4283.2   120.5  4293.2  119.91  4303.2  121.32  4323.2  122.18  4333.2  121.85
  4383.2  122.61  4393.2  123.21  4433.2  122.75  4453.2  123.18  4501.2   122.3
  4503.2  122.26  4553.2  122.74  4583.2  120.72  4603.2   121.6  4613.2  122.45
  4643.2   120.3  4661.2  120.38  4701.2  120.57  4853.2  121.26  4873.2  121.85
  4883.2  121.73  4903.2  120.22 4929.91  120.66    4930  120.66  4931.2  120.68
  4933.2  120.71    4943  120.52  4943.2  120.52  4964.5     119  4967.5     116
  5032.5     116  5035.5     119    5057  120.75 5069.89  121.81    5070  121.81
  5172.4  130.17  5192.4  130.71    5200  130.55  5202.4   130.5  5212.4  132.52
  5232.4   134.1    5240  134.37  5242.4  134.45  5252.4   135.5    5260  135.88
  5282.4     137  5302.4  139.43
BR U #Mann= 3
 2022.00    0.15  4964.5   0.045  5035.5    0.15
BR U Banks=4964.50,5035.50
BR D #Sta/Elev= 132
    2022  137.68    2092  136.36    2102  135.66    2202  133.85  2205.3  133.67
    2222  132.76  2235.3   133.1    2242  133.27  2295.3  132.17    2312  131.83
  2315.3  131.82  2375.3  131.59  2395.3  131.51  2415.3  131.43  2455.3  131.28
  2505.3  131.08  2525.3  131.01    2532  130.98  2535.3  131.08    2552  131.61
  2555.3  131.55  2585.3  131.01    2612  130.52    2632  129.58  2635.3  129.66
    2642  129.81    2652  130.66  2655.3  130.74    2662   130.9  2675.3  130.87
  2685.3  130.85    2732  130.74  2735.3  130.45    2742  129.87    2762  130.08
  2785.3  129.89    2862  129.28    2882   128.3    2942   128.5    3002  127.96
    3012  127.45  3015.3  127.59    3022  127.88  3025.3  127.78    3032  127.58
    3042  126.73  3055.3  127.77    3062  128.29    3132   127.3  3165.3   127.3
  3185.3  127.29    3202  127.29    3222   126.3  3235.3  126.63  3245.3  126.87
    3252  127.04  3255.3  127.03  3315.3  126.89  3365.3  126.77    3392  126.71
  3395.3  126.57  3415.3   125.7  3433.2  124.92  3435.3  125.01  3445.3  125.44
  3463.2  126.21  3465.3  126.08  3473.2   125.6  3475.3  125.62  3513.2  126.03
  3535.3  125.79  3673.2  124.26  3693.2  123.52  3773.2  124.72  3853.2  124.09
  3863.2  123.42  3961.2  122.88  3983.2  122.76  4053.2  122.25  4063.2  121.74
  4083.2  121.86  4093.2  121.29  4173.2  122.42  4233.2  121.48  4243.2  120.81
  4283.2  120.25  4293.2  119.66  4303.2  121.07  4323.2  121.93  4333.2   121.6
  4383.2  122.36  4393.2  122.96  4433.2   122.5  4453.2  122.93  4501.2  122.05
  4503.2  122.01  4553.2  122.49  4583.2  120.47  4603.2  121.35  4613.2   122.2
  4643.2  120.05  4661.2  120.13  4701.2  120.32  4853.2  121.01  4873.2   121.6
  4883.2  121.48  4903.2  119.97 4929.91  120.41    4930  120.41  4931.2  120.43
  4933.2  120.46    4943  120.27  4943.2  120.27  4964.5  118.75  4967.5  115.75
  5032.5  115.75  5035.5  118.75    5057   120.5 5069.89  121.56    5070  121.56
  5172.4  129.92  5192.4  130.46    5200   130.3  5202.4  130.25  5212.4  132.27
  5232.4  133.85    5240  134.12  5242.4   134.2  5252.4  135.25    5260  135.63
  5282.4  136.75  5302.4  139.18
BR D #Mann= 3
 2022.00    0.15  4964.5   0.045  5035.5    0.15
BR D Banks=4964.50,5035.50

Type RM Length L Ch R = 1 ,8720.2,160.1,160.1,160.1
BEGIN DESCRIPTION:
Downstream Section of Bridge/Culvert/Weir
END DESCRIPTION:
#Sta/Elev= 30
    2022  137.67    2222  132.75    2552   131.6    2632  129.57    2732  130.73
    3042  126.72    3062  128.28    3222  126.29    3392   126.7  3433.2  124.91
  3513.2  126.02  3693.2  123.51  3773.2  124.71  4093.2  121.28  4173.2  122.41
  4293.2  119.65  4323.2  121.92  4393.2  122.95  4553.2  122.48  4583.2  120.46
  4613.2  122.19  4643.2  120.04  4873.2  121.59  4964.5  118.74  4967.5  115.74
  5032.5  115.74  5035.5  118.74  5172.4  129.91  5202.4  130.24  5302.4  139.17
#Mann= 3 , 1 , 0
 2022.00    0.15       0  4964.5   0.045       0  5035.5    0.15       0
#XS Ineff= 2 , 0
       0    4919  126.19    5082       0  129.77
Bank Sta=4964.50,5035.50
Exp/Cntr=0.5,0.3

Type RM Length L Ch R = 1 ,8560.1,0,0,0
BEGIN DESCRIPTION:
Pig Basket Creek 0.1
END DESCRIPTION:
#Sta/Elev= 30
  2489.2  137.25  2579.2  128.44  2699.2  125.82  2919.2  125.29  2929.2  126.18
  3059.2  124.06  3339.2  125.35  3359.2  124.32  3409.2  125.05  3579.2  123.95
  3609.2  125.24  3745.9  124.01  3805.9   121.8  3845.9  123.17  3995.9  121.98
  4035.9  123.45  4085.9  121.87  4595.9   120.6  4748.7  121.82  4818.7  119.83
  4958.7  121.64    4974  119.59    4976  115.59  5024.1  115.59  5026.1  119.59
  5058.7  120.25  5078.7  122.85  5108.7  123.47  5138.7  134.66  5148.7  137.13
#Mann= 3 , 1 , 0
 2489.20    0.15       0    4974   0.045       0  5026.1    0.15       0
Bank Sta=4974.00,5026.10
Exp/Cntr=0.3,0.1

Chan Stop Cuts=-1